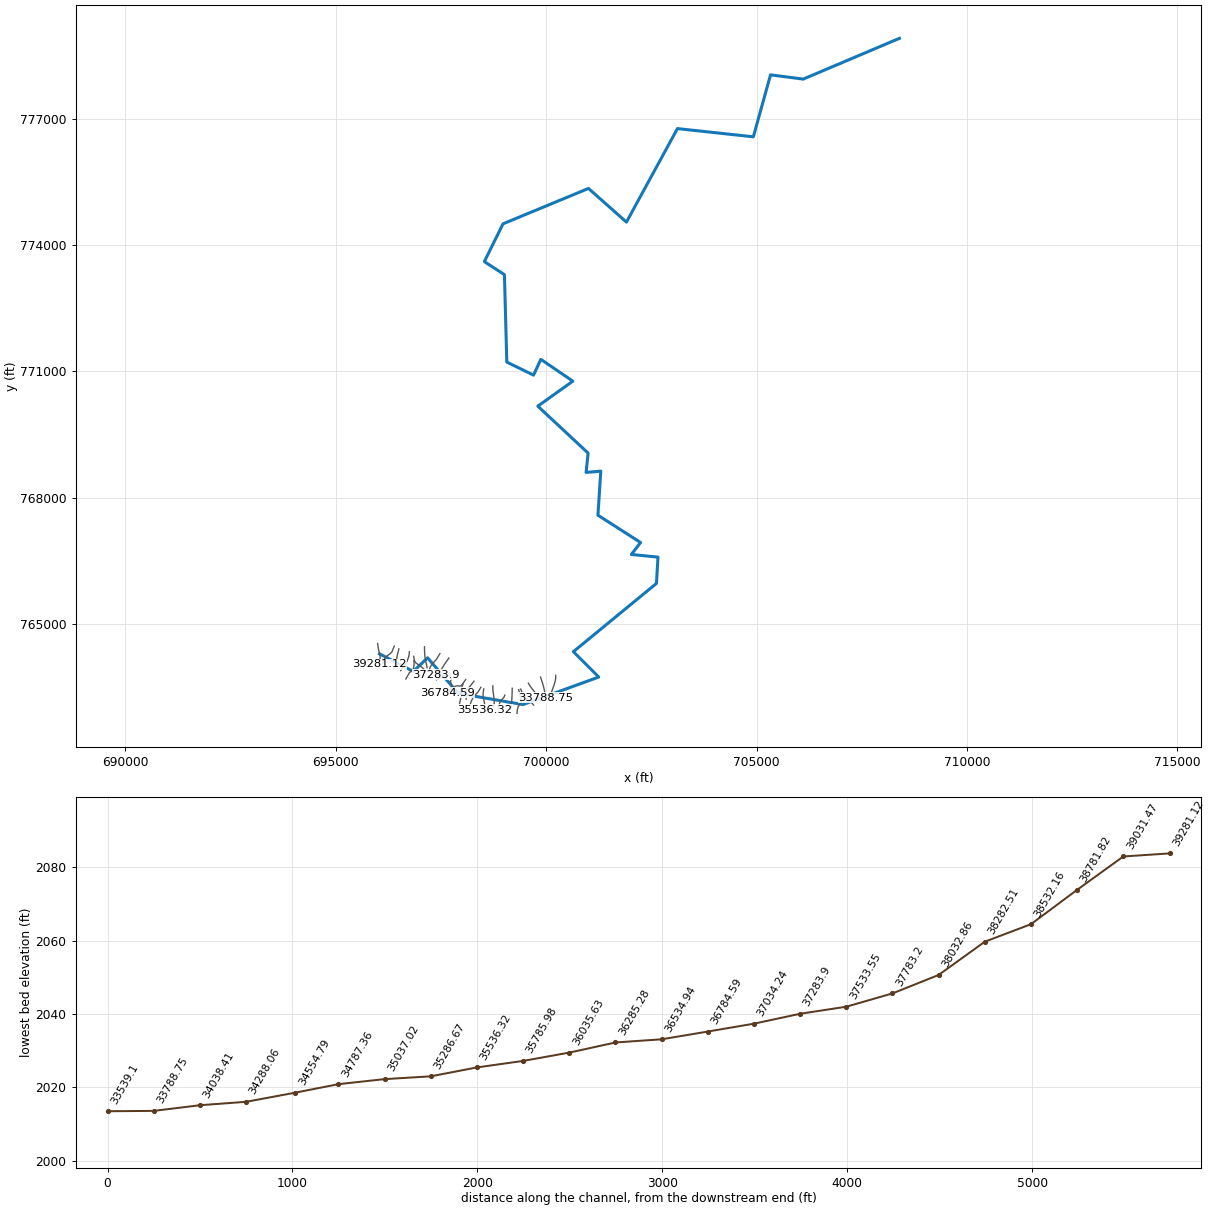
--- 14441_ras.prj (project) ---

Proj Title=14441
Current Plan=p01
Default Exp/Contr=0.3,0.1
English Units
Geom File=g01
Flow File=f01
Plan File=p01
Y Axis Title=Elevation
X Axis Title(PF)=Main Channel Distance
X Axis Title(XS)=Station
BEGIN DESCRIPTION:
RFD model 14441 exported to HEC-RAS
END DESCRIPTION:

--- 14441_ras.p01 (plan) ---

Plan Title=Plan 01
Program Version=4.10
Short Identifier=Plan 01
Geom File=g01
Flow File=f01
Subcritical Flow
Calc Critical at every XS
Secant Critical Depth

--- 14441_ras.f01 (steady flow) ---

Flow Title=Flow 01
Program Version=5.01
Number of Profiles= 6
Profile Names=10yr,25yr,50yr,100yr,100plus,500yr
River Rch & RM=14441,158,39281.12
  833.86 1400.77 1954.83 2486.31 3630.01 5269.66
River Rch & RM=14441,158,39031.47
  837.08 1406.26 1962.56 2496.23 3644.49 5288.07
River Rch & RM=14441,158,38781.82
  860.86 1446.72 2019.56 2569.21 3751.05 5422.72
River Rch & RM=14441,158,38532.16
  865.88 1455.28 2031.63  2584.7 3773.66 5451.31
River Rch & RM=14441,158,38282.51
  869.48 1461.45 2040.35 2595.89 3790.01 5472.06
River Rch & RM=14441,158,38032.86
   871.3 1464.55 2044.72  2601.5  3798.2 5482.43
River Rch & RM=14441,158, 37783.2
  876.99 1474.25 2058.41 2619.05 3823.82 5514.78
River Rch & RM=14441,158,37533.55
  885.37 1488.56  2078.6 2644.96 3861.64 5562.51
River Rch & RM=14441,158, 37283.9
  889.42 1495.49 2088.38 2657.51 3879.97 5585.67
River Rch & RM=14441,158,37034.24
  891.88 1499.69 2094.33 2665.16 3891.14 5599.81
River Rch & RM=14441,158,36784.59
  978.35 1648.58 2305.63 2937.57 4288.85  6103.6
River Rch & RM=14441,158,36534.94
  986.52 1662.64 2325.57 2963.27 4326.37 6150.72
River Rch & RM=14441,158,36285.28
  993.54 1674.74 2342.78 2985.47 4358.79 6191.53
River Rch & RM=14441,158,36035.63
   994.6 1676.58 2345.38 2988.83 4363.69  6197.7
River Rch & RM=14441,158,35785.98
 1000.79 1687.24 2360.52 3008.35 4392.19 6233.46
River Rch & RM=14441,158,35536.32
 1013.29  1708.8 2391.16 3047.89 4449.92 6305.95
River Rch & RM=14441,158,35286.67
 1018.39 1717.59 2403.63 3063.98 4473.41 6335.35
River Rch & RM=14441,158,35037.02
 1023.25 1725.97 2415.54 3079.35 4495.85 6363.47
River Rch & RM=14441,158,34787.36
 1052.37 1775.97 2486.39 3170.54 4628.99 6528.78
River Rch & RM=14441,158,34554.79
 1055.51 1781.39 2494.09 3180.49 4643.51 6546.91
River Rch & RM=14441,158,34288.06
  1057.6    1785 2499.23 3187.12 4653.19 6558.99
River Rch & RM=14441,158,34038.41
 1063.47 1795.13 2513.62 3205.69  4680.3 6592.76
River Rch & RM=14441,158,33788.75
 1068.49 1803.78 2525.92 3221.57 4703.49 6621.65
River Rch & RM=14441,158, 33539.1
 1070.79 1807.75 2531.56 3228.85 4714.12 6634.87
River Rch & RM=14441,158,33282.67
 1073.92 1813.15 2539.24 3238.76  4728.6 6652.89
River Rch & RM=14441,158,33039.79
 1130.24 1910.91 2678.71 3419.37 4992.28 6982.25
River Rch & RM=14441,158,32747.49
 1136.81 1922.26 2694.86 3440.23 5022.74 7019.91
River Rch & RM=14441,158,32540.49
 1141.34 1930.08 2705.97 3454.58 5043.68 7045.75
River Rch & RM=14441,158, 32322.4
 1141.95 1931.14 2707.48 3456.53 5046.54 7049.27
River Rch & RM=14441,158,32041.18
  1288.4 2184.88 3069.14 3924.43 5729.67 7887.96
River Rch & RM=14441,158,31791.53
 1292.64 2192.18 3079.51 3937.81  5749.2 7911.53
River Rch & RM=14441,158,31541.87
 1293.85 2194.27 3082.47 3941.63 5754.78 7918.26
River Rch & RM=14441,158,31292.22
 1336.72 2267.92  3186.9 4076.08 5951.08 8153.46
River Rch & RM=14441,158,30792.91
 1338.12 2270.34 3190.33 4080.51 5957.54 8161.21
River Rch & RM=14441,158,30543.26
 1433.79 2434.34 3422.55  4379.1 6393.49 8677.81
River Rch & RM=14441,158,30293.61
 1435.77 2437.74 3427.38 4385.33 6402.59 8688.62
River Rch & RM=14441,158,30106.72
 1448.35 2459.44 3458.23 4425.14  6460.7  8757.7
River Rch & RM=14441,158, 29794.3
 1459.72 2479.06 3486.12 4461.13 6513.25 8820.11
River Rch & RM=14441,158,29544.65
 1462.28 2483.47 3492.39 4469.21 6525.05 8834.08
River Rch & RM=14441,158,   29295
 1502.26  2552.2 3589.88 4594.77 6708.37 9049.99
River Rch & RM=14441,158,29045.34
 1504.41 2555.91 3595.15 4601.56 6718.28 9061.69
River Rch & RM=14441,158,28795.69
  1508.1 2562.27  3604.2 4613.25 6735.35 9081.88
River Rch & RM=14441,158,28546.04
 1513.35 2571.33 3617.08 4629.87 6759.61 9110.55
River Rch & RM=14441,158,28296.38
 1523.09 2588.13 3640.96 4660.67 6804.58 9163.54
River Rch & RM=14441,158,28046.73
 2007.31 3424.61 4831.48 6198.13 9049.2811758.97
River Rch & RM=14441,158,27801.78
 2007.86 3425.55 4832.83 6199.88 9051.8211761.85
River Rch & RM=14441,158,27297.77
 2079.45 3549.19  5008.8 6427.08 9383.5412136.71
River Rch & RM=14441,158,26852.63
 2082.36 3554.21 5015.94  6436.3    939712151.87
River Rch & RM=14441,158,26445.36
 2096.94 3579.36 5051.71 6482.44 9464.3612227.58
River Rch & RM=14441,158,26049.51
 2099.12 3583.12 5057.06 6489.34 9474.4412238.92
River Rch & RM=14441,158,25799.85
 2112.91 3606.92 5090.92 6533.05 9538.2512310.65
River Rch & RM=14441,158, 25550.2
  2121.6 3621.93 5112.28 6560.62  9578.512355.87
River Rch & RM=14441,158,25300.55
 2127.62  3632.3 5127.01 6579.61 9606.2412386.92
River Rch & RM=14441,158,25050.89
 2131.26 3638.57 5135.93 6591.12 9623.0312405.73
River Rch & RM=14441,158,24795.11
 2131.99 3639.83 5137.72 6593.42 9626.3912409.49
River Rch & RM=14441,158,24551.59
 2142.74 3658.35 5164.03 6627.35 9675.9312464.88
River Rch & RM=14441,158,24052.28
 2195.37 3748.96 5292.75 6793.22 9918.1112734.86
River Rch & RM=14441,158,23802.63
 2198.63 3754.58 5300.73 6803.52 9933.13 12751.6
River Rch & RM=14441,158,23552.97
  2206.4 3767.96 5319.76 6828.06 9968.9712791.56
River Rch & RM=14441,158,23181.56
 2208.57  3771.7 5325.08 6834.92 9978.98 12802.7
River Rch & RM=14441,158,22786.03
 2230.47 3809.34 5378.48 6903.6710079.3512913.91
River Rch & RM=14441,158,22554.36
 2254.38 3850.58 5437.12 6979.3110189.7913036.73
River Rch & RM=14441,158,22304.71
 2257.08 3855.23 5443.73 6987.8410202.2413050.55
River Rch & RM=14441,158,22055.05
 2265.87 3870.39  5465.3 7015.6610242.8613095.67
River Rch & RM=14441,158, 21805.4
 2286.04 3905.06 5514.47 7078.9510335.2713197.65
River Rch & RM=14441,158,21555.75
 2290.53 3912.79 5525.47 7093.1310355.9713220.57
River Rch & RM=14441,158, 21306.1
 2293.44 3917.78 5532.55 7102.2410369.2713235.24
River Rch & RM=14441,158,21056.44
 2294.16 3919.03 5534.32 7104.52 10372.6 13238.9
River Rch & RM=14441,158,20806.79
 2299.08 3927.46 5546.28 7119.9110395.0613263.63
River Rch & RM=14441,158,20557.14
 2301.44 3931.52 5552.04 7127.3110405.8813275.53
River Rch & RM=14441,158,20307.48
 2303.99 3935.89 5558.23 7135.2910417.5213288.34
River Rch & RM=14441,158,20057.83
  2305.8 3939.01 5562.65 7140.9810425.8313297.49
River Rch & RM=14441,158,19808.18
 2328.96 3979.06 5619.71  7214.710533.4613417.09
River Rch & RM=14441,158,19558.52
  2331.8 3983.97 5626.69 7223.7110546.6113431.67
River Rch & RM=14441,158,19308.87
 2335.03 3989.52 5634.58 7233.8810561.4713448.06
River Rch & RM=14441,158,19059.22
 2342.42 4002.32 5652.82 7257.4510595.8813486.29
River Rch & RM=14441,158,18636.48
  2358.9 4030.78 5693.33 7309.7410672.2313570.77
River Rch & RM=14441,158,18310.26
 2361.79 4035.74 5700.37 7318.8110685.4613585.29
River Rch & RM=14441,158, 18060.6
  2364.5 4040.39 5706.97  7327.310697.8513598.89
River Rch & RM=14441,158,17810.95
 3195.71 5452.39 7695.74 9869.3514409.2617510.84
River Rch & RM=14441,158, 17561.3
 3199.76 5459.36 7705.65 9882.1314427.9217530.53
River Rch & RM=14441,158,17311.65
 3213.44 5482.84 7738.95 9924.9614490.4417596.13
River Rch & RM=14441,158,17061.99
 3217.62 5490.06 7749.23 9938.2114509.79 17616.6
River Rch & RM=14441,158,16812.34
 3223.56 5500.28 7763.73 9956.8914537.0517645.26
River Rch & RM=14441,158,16562.69
 3230.53 5512.33 7780.91 9979.0814569.4517679.62
River Rch & RM=14441,158,16313.03
 3245.11  5537.4  7816.510024.8914636.34 17749.9
River Rch & RM=14441,158,16063.38
 3258.26 5560.04 7848.6710066.3414696.8617813.54
River Rch & RM=14441,158,15813.73
 3263.22 5568.62  7860.910082.1514719.94   17838
River Rch & RM=14441,158,15564.07
  3265.2 5572.05  7865.810088.4714729.1717847.77
River Rch & RM=14441,158,15314.42
 3271.17 5582.45 7880.6910107.7814757.3617877.91
River Rch & RM=14441,158,15064.77
 3274.11 5587.55 7887.9710117.2114771.1217892.56
River Rch & RM=14441,158,14815.11
 3282.05 5601.29 7907.55 10142.514808.0517931.62
River Rch & RM=14441,158, 14553.5
 3284.38  5605.3 7913.2710149.8814818.83   17943
River Rch & RM=14441,158,14315.81
 3386.43 5780.89 8162.6710471.0615287.7518433.91
River Rch & RM=14441,158,14066.15
 3388.88 5785.12 8168.7210478.8815299.1718445.98
River Rch & RM=14441,158, 13816.5
 4696.25 8029.3511352.3414572.6821276.1224512.42
River Rch & RM=14441,158,13566.85
 4698.01 8032.4411356.7814578.4621284.5524521.05
River Rch & RM=14441,158,13318.69
 4700.35 8036.5311362.6814586.1421295.7624532.56
River Rch & RM=14441,158, 13209.7
 4721.57 8074.0411416.8914657.0221399.2524639.61
River Rch & RM=14441,158,13067.55
 4722.58 8075.8211419.4614660.3721404.1424644.63
River Rch & RM=14441,158,12827.04
 4734.17 8096.1311448.6614698.3621459.6124701.31
River Rch & RM=14441,158,12586.54
 4737.93 8102.75 11458.2 14710.821477.7724719.95
River Rch & RM=14441,158,12346.03
 4742.69 8111.1411470.2914726.5721500.7924743.61
River Rch & RM=14441,158,12245.93
 4768.68 8156.5811535.5314811.3621624.5924869.61
River Rch & RM=14441,158, 12110.4
 4769.98 8158.8711538.8214815.6621630.8624876.05
River Rch & RM=14441,158,11942.48
 4778.16 8173.3611559.79 14843.121670.9224917.52
River Rch & RM=14441,158,11700.43
 4781.43 8179.1311568.1414854.0121686.8524933.95
River Rch & RM=14441,158,11458.37
    4782 8180.1411569.5914855.9121689.6224936.81
River Rch & RM=14441,158,11216.31
 4787.18 8189.3411582.9214873.3721715.1124963.24
River Rch & RM=14441,158,10974.26
    4791  8196.111592.6914886.1521733.7824982.52
River Rch & RM=14441,158, 10732.2
 4792.56 8198.8611596.6814891.3621741.3924990.37
River Rch & RM=14441,158,10590.93
 4794.41 8202.1211601.3914897.5221750.3924999.65
River Rch & RM=14441,158,10490.14
 4795.26 8203.6211603.5714900.3721754.5425003.93
River Rch & RM=14441,158,10152.91
 4839.77 8281.7211715.9415046.6921968.1725221.96
River Rch & RM=14441,158,9906.538
 4933.24 8445.8311952.1615354.38 22417.425679.82
River Rch & RM=14441,158,9660.169
 4934.36 8447.8211955.0415358.1422422.8925685.47
River Rch & RM=14441,158,  9413.8
 4935.62 8450.0511958.2615362.3722429.0625691.83
River Rch & RM=14441,158,9167.432
 4948.45 8472.8711991.37 15405.822492.4725757.47
River Rch & RM=14441,158,8921.063
 4955.82 8485.9412010.3115430.61 22528.725794.85
River Rch & RM=14441,158,8674.695
  4959.3 8492.1112019.2415442.3222545.7825812.47
River Rch & RM=14441,158,8428.326
 4974.94 8519.9612059.69 15495.422623.2925892.77
River Rch & RM=14441,158,8181.958
 4978.06 8525.54 12067.815506.0722638.8625908.96
River Rch & RM=14441,158,8036.916
 4979.68 8528.4412072.0215511.6322646.9725917.41
River Rch & RM=14441,158,7935.589
 4980.76 8530.3712074.8415515.3322652.3825923.04
River Rch & RM=14441,158,7834.217
 4981.71 8532.06 12077.315518.5622657.1125927.96
River Rch & RM=14441,158,7689.221
 4982.79    853412080.1115522.2722662.5125933.59
River Rch & RM=14441,158,7442.852
 4984.41  8536.912084.3315527.8222670.6225942.04
River Rch & RM=14441,158,7299.995
 4984.95 8537.8612085.7415529.6722673.3225944.85
River Rch & RM=14441,158,7196.484
 4998.57 8562.2212121.2115576.3622741.4826015.86
River Rch & RM=14441,158,6950.115
 5000.19 8565.1212125.4315581.9122749.5826024.29
River Rch & RM=14441,158,6703.747
 5023.87 8607.7112187.6515664.0222869.4726149.93
River Rch & RM=14441,158,6457.378
 5027.21  8613.712196.3915675.5322886.2726167.46
River Rch & RM=14441,158,6211.009
 5034.29 8626.4712215.0715700.2122922.3126205.31
River Rch & RM=14441,158,5964.641
 5041.22 8638.9112233.2115724.1222957.2126241.74
River Rch & RM=14441,158,5718.272
 5044.02 8643.9312240.5315733.77 22971.326256.44
River Rch & RM=14441,158,5471.904
 5046.56 8648.4712247.16 15742.522984.0526269.74
River Rch & RM=14441,158,5225.535
  5101.8 8746.5812389.3915928.9423256.2626549.86
River Rch & RM=14441,158,4979.167
 5106.03 8754.19 12400.515943.5923277.6426572.16
River Rch & RM=14441,158,4732.798
 8329.9214326.5220344.4226196.7638247.27 40817.4
River Rch & RM=14441,158, 4486.43
  8335.914337.3320360.2826217.7538277.9140847.43
River Rch & RM=14441,158,4240.061
 8337.75 14340.720365.22 26224.338287.4840856.84
River Rch & RM=14441,158,4094.461
 8338.4414341.9620367.0726226.7538291.0640860.38
River Rch & RM=14441,158,3993.692
 8346.3814356.3320388.1726254.6938331.8440900.38
River Rch & RM=14441,158,3747.324
 8347.6514358.6320391.5626259.1938338.4240906.85
River Rch & RM=14441,158,3500.955
 8350.0814363.0520398.0526267.7938350.9740919.21
River Rch & RM=14441,158,3315.023
10544.43 18207.9 25929.233462.0748854.6350602.07
River Rch & RM=14441,158,3000.076
10546.6318211.8925935.0733469.86   4886650612.89
Boundary for River Rch & Prof#=14441,158,1
Up Type= 0
Dn Type= 2
Boundary for River Rch & Prof#=14441,158,2
Up Type= 0
Dn Type= 2
Boundary for River Rch & Prof#=14441,158,2
Up Type= 0
Dn Type= 2
Boundary for River Rch & Prof#=14441,158,2
Up Type= 0
Dn Type= 2
Boundary for River Rch & Prof#=14441,158,2
Up Type= 0
Dn Type= 2
Boundary for River Rch & Prof#=14441,158,2
Up Type= 0
Dn Type= 2

--- 14441_ras.g01 (geometry) ---

Geom Title=14441
Program Version=4.10

River Reach=14441,158
Reach XY= 30
696039.193701178764287.160316154696841.560828209 763868.86211054
 697181.83860597764192.056555018697910.171939284763347.056555003
699447.394161522763080.389888346701249.710831642763735.177143067
700646.699717075764337.889888316702621.501150668765960.407208145
702657.810828179766585.528777227702025.033050388766648.306555003
702243.366383761766932.750999451 701230.58860597767581.639888346
701298.366383731768628.862110555700949.001437783768598.212450102
700997.612884551769057.414039195699801.807777911770172.623586297
700634.272852063770767.241885185 699874.07903108771285.248966277
699700.235327214770910.941421747699064.828320384771220.366349161
699008.404790491773298.491460592698530.974496871773608.387575179
 698975.58860597774506.500999466701005.685099274775347.391830787
701908.462980181774547.044758826703120.206661522776769.521832779
704924.364881754776574.338971317705332.706661522778046.605166137
 706109.63441363777945.916458338 708395.90110594778914.660721689

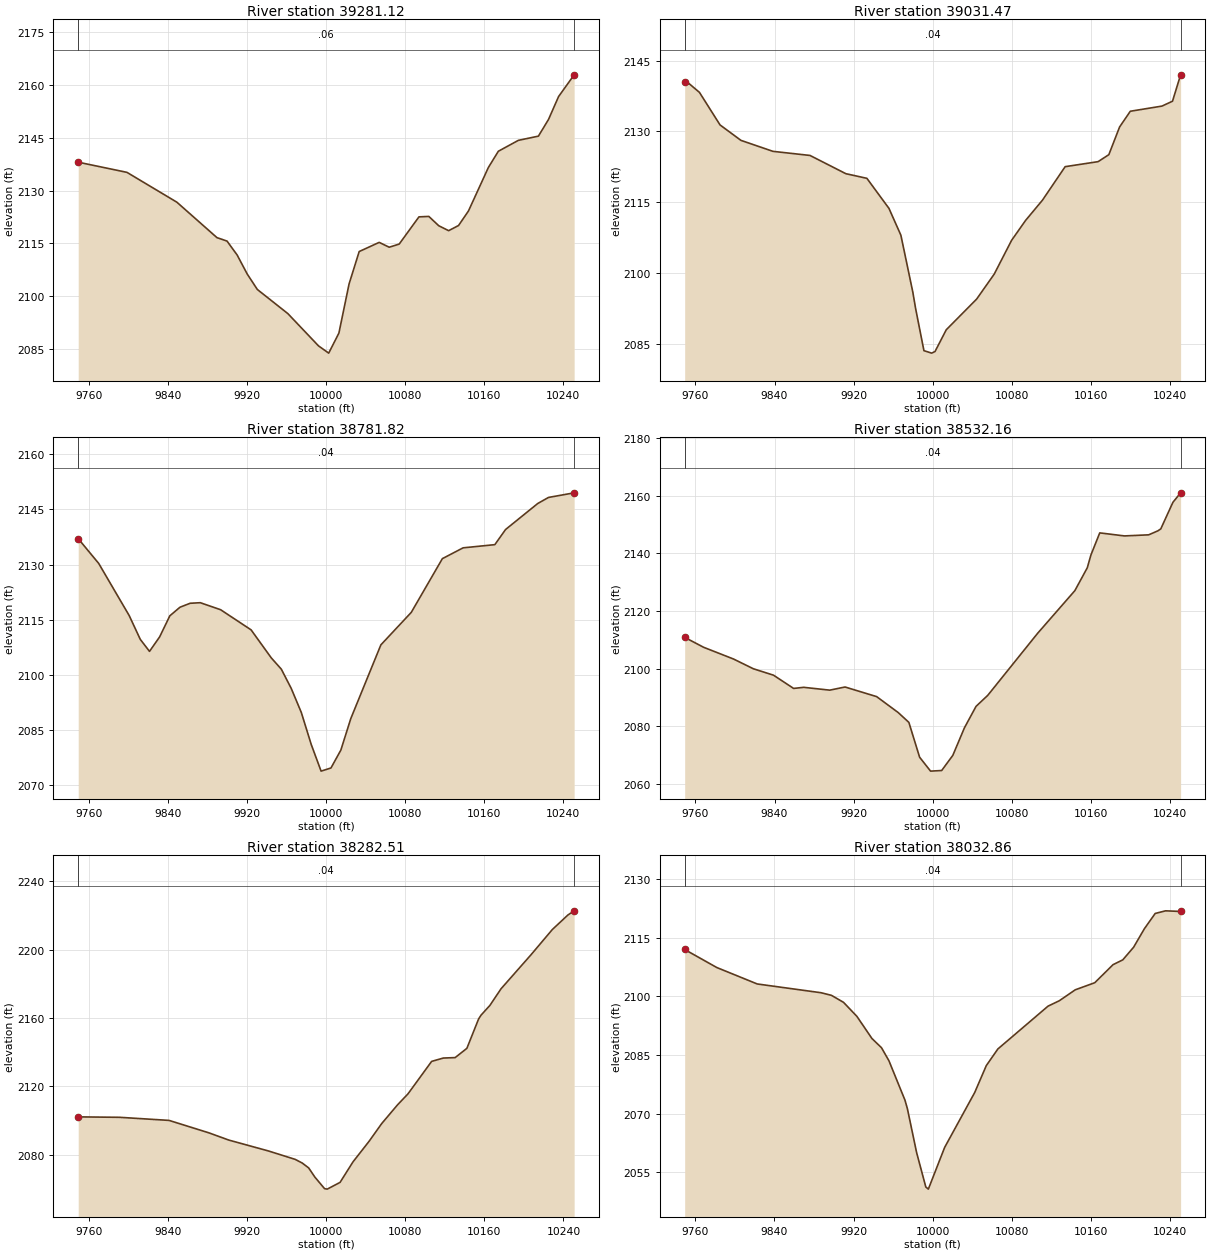
Type RM Length L Ch R = 1 ,39281.12,249.653200,249.653200,249.653200
XS GIS Cut Line= 6
695994.557239912764533.929049054696014.162630641764397.224829927
696047.211567792764259.645802254696054.052660542 764216.09144255
696052.584653116764134.147612458696035.771067874764039.574317581
#Sta/Elev= 30
9749.0182138.0869798.3382135.1989848.8642126.7189889.4182116.653 9899.642115.664
9909.8612111.7169920.0822106.3029930.3042101.9169961.152 2095.079992.174  2085.9
10002.52 2083.8310012.842089.51710023.152103.50310033.382112.69610053.622115.299
10063.752113.92610073.862114.81610093.86 2122.5510103.872122.67310113.872120.031
 10123.92118.62510133.92 2120.0910143.952124.21210164.082136.558 10174.22141.193
10194.432144.28810214.752145.48810224.96 2150.2210235.172156.73410250.92 2162.91
#Mann= 3 , 0 , 0
9749.018    0.06       09749.018    0.06       010250.92    0.06       0
#XS Ineff= 2 , 0
       0                               0
Bank Sta=9749.018,10250.92
Exp/Cntr=0.3,0.1

Type RM Length L Ch R = 1 ,39031.47,249.653100,249.653100,249.653100
XS GIS Cut Line= 6
696390.492858114764469.374299891696334.886858384764334.091592356
696296.066069691 764290.55019975696193.009782058764220.728995523
696155.462383399764158.371421388696119.201685142764067.308707814
#Sta/Elev= 30
9749.125 2140.399753.681 2140.129764.097 2138.279784.9282131.3689806.0822128.099
9838.4442125.7729875.9362124.9039912.1932121.0359933.4622120.0549955.7862113.686
 9967.852108.0049979.9142095.9549982.7862092.4269991.174 2083.52    99992082.992
 10002.42083.33610013.782087.94610044.492094.44810062.28 2099.74 10079.92106.917
10094.032111.12910111.132115.43310134.072122.52610167.372123.58710178.26 2125.07
10189.142130.94510199.962134.27310231.982135.36710242.662136.40210250.872141.997
#Mann= 3 , 0 , 0
9749.125    0.04       09749.125    0.04       010250.87    0.04       0
#XS Ineff= 2 , 0
       0                               0
Bank Sta=9749.125,10250.87
Exp/Cntr=0.3,0.1

Type RM Length L Ch R = 1 ,38781.82,249.653200,249.653200,249.653200
XS GIS Cut Line= 6
696499.586646362764405.170770448696455.315716797 764219.73944791
696447.305403087764128.437718269696437.968538975764080.879104362
696416.000269595764011.796210451696377.627147593763921.073921587
#Sta/Elev= 30
9749.0432137.0599769.7812130.3249800.6242116.1689811.8572109.6979821.186 2106.43
9831.4672110.3839841.7482116.0919852.0292118.427 9862.31  2119.59872.5912119.655
9893.1532117.7499923.9962112.2749944.4742104.6459954.5762101.6049964.679 2096.33
9974.7822089.8529984.8032081.1819994.8122073.90210004.822074.75910014.842079.628
10024.862088.16410055.322108.20310086.072117.02510117.552131.62310138.54 2134.56
10170.632135.42410181.492139.53510214.062146.60410224.922148.248 10250.92149.504
#Mann= 3 , 0 , 0
9749.043    0.04       09749.043    0.04       0 10250.9    0.04       0
#XS Ineff= 2 , 0
       0                               0
Bank Sta=9749.043,10250.9
Exp/Cntr=0.3,0.1

Type RM Length L Ch R = 1 ,38532.16,249.653100,249.653100,249.653100
XS GIS Cut Line= 6
696749.052000433764334.155567902696742.811340013764268.542164013
696731.958190403764211.747380731696692.604518535764105.671621991
696658.998298644764045.680866705696541.728463033763888.624849584
#Sta/Elev= 30
9749.085 2110.919768.3272107.4549798.4622103.4059818.6012100.0179838.9632097.795
9859.3252093.2019869.5052093.581 9895.922092.6029911.3542093.6959943.3572090.359
9965.0872084.8579975.952 2081.439986.8312069.3549997.9072064.52410009.152064.734
10020.432069.98310032.16 2079.5210043.942086.98310055.782090.79610106.162112.273
10143.942127.10810156.53 2135.0510160.212139.48810169.132147.13310194.162146.081
10218.65 2146.4610227.992147.848 10230.92148.52410243.152157.72310250.962161.024
#Mann= 3 , 0 , 0
9749.085    0.04       09749.085    0.04       010250.96    0.04       0
#XS Ineff= 2 , 0
       0                               0
Bank Sta=9749.085,10250.96
Exp/Cntr=0.3,0.1

Type RM Length L Ch R = 1 ,38282.51,249.653100,249.653100,249.653100
XS GIS Cut Line= 6
 696857.36768795764126.754453085 696861.42090013764030.843328473
696843.871231789763932.761575517696830.569204973763913.558657624
696746.755040357763832.714716381696664.814390621763689.411054247
#Sta/Elev= 30
9749.1732102.0379791.0622101.7869841.0922099.9769881.3732092.698 9901.532088.458
9941.481 2082.119968.602 2077.189975.7262075.0459982.3262072.1549988.5192066.846
9998.3612060.03810001.072059.74410014.082063.69510027.092075.64810043.642087.908
10056.172098.10310072.332109.15910082.722115.469 10106.72134.52210118.582136.486
10130.472136.73510142.362142.16410154.252159.39510156.742161.61710165.652167.297
10176.932177.03410207.192196.90910228.832211.72410244.582220.22610250.882222.662
#Mann= 3 , 0 , 0
9749.173    0.04       09749.173    0.04       010250.88    0.04       0
#XS Ineff= 2 , 0
       0                               0
Bank Sta=9749.173,10250.88
Exp/Cntr=0.3,0.1

Type RM Length L Ch R = 1 ,38032.86,249.653200,249.653200,249.653200
XS GIS Cut Line= 6
 696850.28842578764227.061691246696869.173978826764132.887193798
696892.779841813764079.859131099697072.745406165763947.317274162
697107.485519002763899.804862227 697130.33943675763840.398921574
#Sta/Elev= 30
9749.1542111.9949781.6932107.3769822.5452103.1749887.2192100.927 9897.652100.261
9909.8432098.4729923.3672094.8899938.6132089.2159948.2772086.8589955.8152083.516
9971.9742073.4719974.4592071.2749983.822    20609993.1042051.2229995.6712050.668
10012.162061.34510042.572075.39110054.292082.27310066.012086.538 10116.82097.502
10128.132098.87210144.292101.67510164.032103.49110182.522108.10910192.372109.341
10203.312112.56610214.242117.31110225.18 2121.2210235.662121.89110250.892121.732
#Mann= 3 , 0 , 0
9749.154    0.04       09749.154    0.04       010250.89    0.04       0
#XS Ineff= 2 , 0
       0                               0
Bank Sta=9749.154,10250.89
Exp/Cntr=0.3,0.1

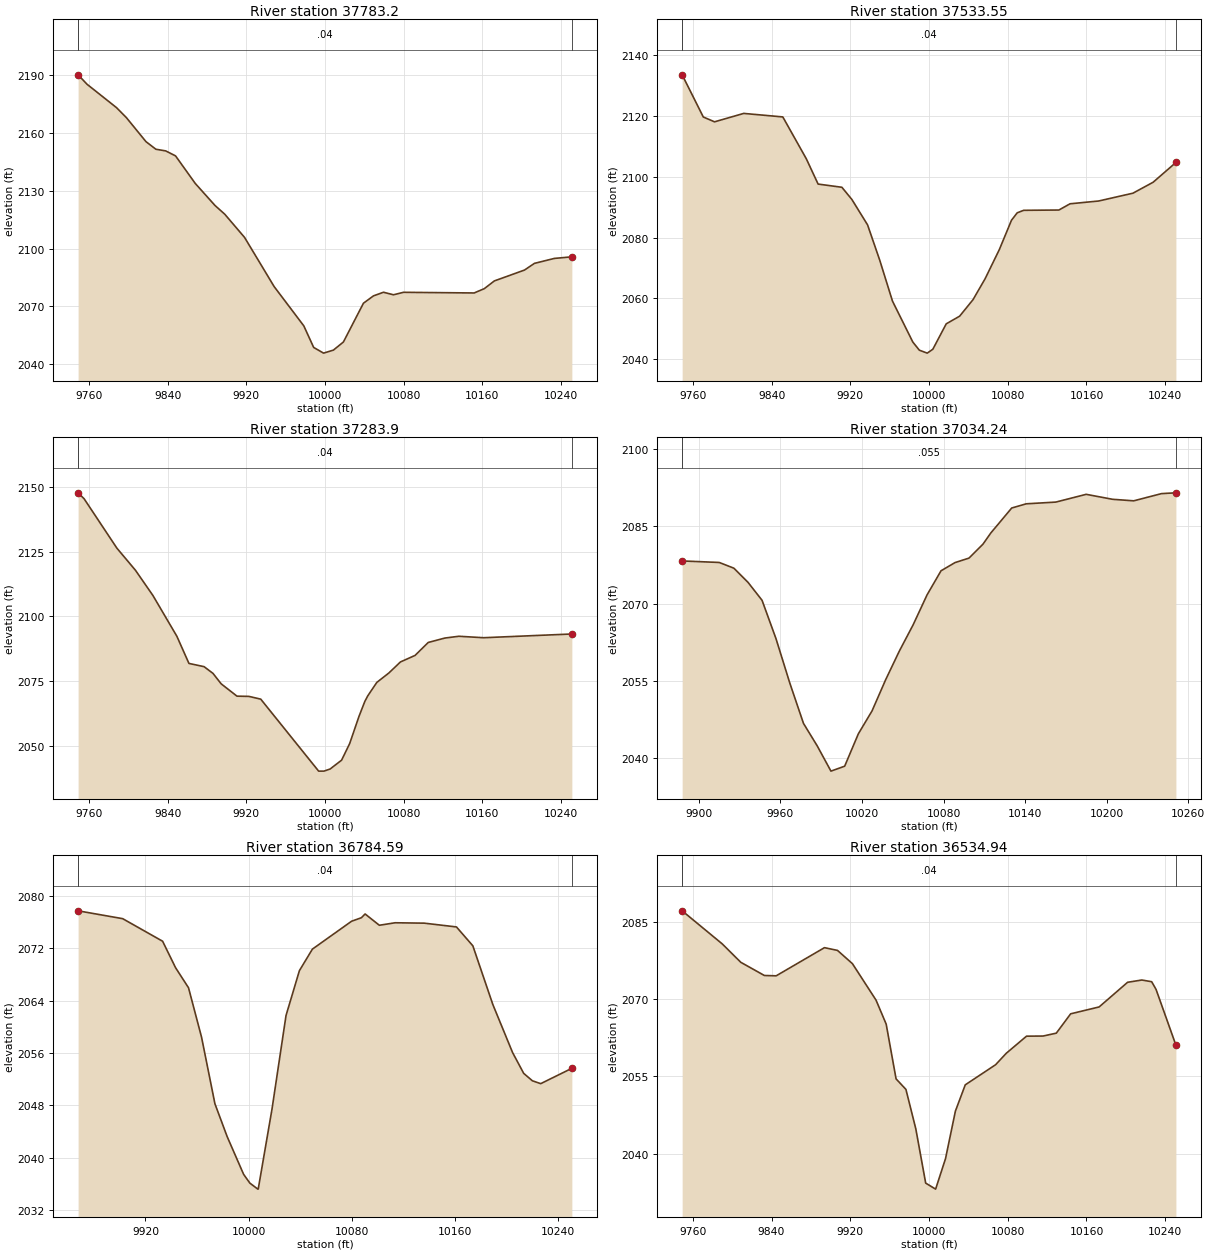
Type RM Length L Ch R = 1 , 37783.2,249.653100,249.653100,249.653100
XS GIS Cut Line= 6
697108.238109633764454.033053286697110.135833303764336.085344224
697121.397062702764195.294068606697134.856218873764124.891823206
697158.952301337764020.395267502697169.828083368763957.558185578
#Sta/Elev= 30
9749.0612190.3379758.0952185.4579788.0992173.278  9798.1 2168.119818.1032155.568
9828.1042151.6549838.1052150.7829848.1072148.1989868.1132133.8889888.1822122.432
9898.2172117.8259918.2862105.7899948.391  2080.29978.4952059.8189988.5292048.596
9998.5642045.63410008.58  2047.210018.762051.42910039.122071.58910049.31  2075.4
10059.492077.28510069.672075.97410079.852077.25710151.682076.91510161.952079.152
10172.21 2083.1810202.822088.82210212.97 2092.3110233.272094.88610250.97  2095.7
#Mann= 3 , 0 , 0
9749.061    0.04       09749.061    0.04       010250.97    0.04       0
#XS Ineff= 2 , 0
       0                               0
Bank Sta=9749.061,10250.97
Exp/Cntr=0.3,0.1

Type RM Length L Ch R = 1 ,37533.55,249.653200,249.653200,249.653200
XS GIS Cut Line= 6
697475.305292259764293.815747717697393.890056667764158.099233579
 697288.72900867764039.200855805697259.165022303763998.490251827
697235.681639838763950.322950173697215.075919951763872.387009872
#Sta/Elev= 30
9749.062 2133.519770.5662119.6459781.9942118.0599811.6592120.8219851.3742119.668
 9875.282105.8929887.2332097.5939911.4162096.5389921.5992092.5159937.5312084.168
9949.9522072.5039962.835 2059.129983.504 2045.669990.162 2042.979998.1782042.008
10003.852043.28110017.472051.638 10031.12054.15810044.732059.59910057.022066.487
10071.452076.058 10083.82085.70210089.622088.14110096.162088.96310131.992089.057
 10143.32091.10610172.462092.02910207.242094.59110227.742098.18710250.912104.689
#Mann= 3 , 0 , 0
9749.062    0.04       09749.062    0.04       010250.91    0.04       0
#XS Ineff= 2 , 0
       0                               0
Bank Sta=9749.062,10250.91
Exp/Cntr=0.3,0.1

Type RM Length L Ch R = 1 , 37283.9,249.653100,249.653100,249.653100
XS GIS Cut Line= 6
697688.479177249764187.281765328697585.949754931764040.949323099
697530.175905225763949.880740194697511.925030616763923.882736166
697470.756123468763877.684641221697381.386651393763793.460787491
#Sta/Elev= 30
9749.019 2147.879755.0822145.5949788.4362126.4489807.363 2117.869825.0672108.119
9849.4882092.2699861.6982081.7939877.0712080.5439886.1192077.9429894.498 2073.88
 9910.542069.116 9922.752069.0229934.6982067.9569993.543 2040.08    99992040.089
10005.232040.90810016.882044.32810025.082050.74610034.492061.21310040.452067.033
 10043.52069.24910052.672074.43910064.892078.07510076.662082.35710091.552084.896
10104.942089.91110121.762091.61410136.042092.31510161.212091.75110250.942093.195
#Mann= 3 , 0 , 0
9749.019    0.04       09749.019    0.04       010250.94    0.04       0
#XS Ineff= 2 , 0
       0                               0
Bank Sta=9749.019,10250.94
Exp/Cntr=0.3,0.1

Type RM Length L Ch R = 1 ,37034.24,249.653100,249.653100,249.653100
XS GIS Cut Line= 6
697729.394144258 763782.49650542697667.311688922763758.981672092
697562.663984127763745.288041804697509.467251756763732.582914156
697446.872180414763706.073934143697389.825365462763668.848749654
#Sta/Elev= 30
9887.7152078.2859914.9762077.9899925.7462076.8789936.1472074.1239946.4882070.627
9956.7732063.1369966.8722054.5429976.9712046.6649987.0712042.289 9997.172037.378
10007.252038.33710017.322044.634 10027.42049.10310037.482055.20910047.552060.785
10057.632065.85410067.862071.67810078.142076.36910088.422077.96310098.712078.839
10108.99 2081.5510114.682083.69810130.122088.582 10140.82089.40410162.582089.739
10184.91 2091.2510204.312090.28410219.862089.98410240.392091.39210250.912091.542
#Mann= 3 , 0 , 0
9887.715   0.055       09887.715   0.055       010250.91   0.055       0
#XS Ineff= 2 , 0
       0                               0
Bank Sta=9887.715,10250.91
Exp/Cntr=0.3,0.1

Type RM Length L Ch R = 1 ,36784.59,249.653200,249.653200,249.653200
XS GIS Cut Line= 6
697748.367564939763706.602822822697725.744458017763628.333590698
697756.239602318763543.043367373697751.243338123763497.584019484
  697723.6309677763448.747089429697655.009574694763366.696457423
#Sta/Elev= 30
9867.7432077.7099902.3192076.5139933.3052073.0679943.3422069.031  9953.42065.962
9963.4972058.4369973.8922048.255 9983.382043.2459996.1252037.495   100012036.147
10007.182035.23110007.47 2035.2410018.172047.45910029.042061.73410039.422068.577
 10049.52071.86410079.892076.11910087.53 2076.6610090.382077.22910101.422075.505
10113.662075.88610136.292075.82710161.262075.24910173.972072.36610189.472063.408
 10204.82056.07110213.41  2052.910220.132051.77110226.61 2051.3310250.762053.669
#Mann= 3 , 0 , 0
9867.743    0.04       09867.743    0.04       010250.76    0.04       0
#XS Ineff= 2 , 0
       0                               0
Bank Sta=9867.743,10250.76
Exp/Cntr=0.3,0.1

Type RM Length L Ch R = 1 ,36534.94,249.653100,249.653100,249.653100
XS GIS Cut Line= 6
698087.436652117763674.717362625697988.214268886763536.019684038
697953.028718611763521.767984218697874.005239066763526.632634774
697833.722255827763515.679009086 697711.06833326763397.218524589
#Sta/Elev= 30
9749.1812087.1449789.8922080.7299808.7632077.1519832.732 2074.599844.7162074.527
 9893.782079.9939907.0072079.4619922.2122076.883 9946.182069.8089956.4782065.155
9966.5392054.5219976.5412052.4789986.5792044.8389996.6372034.28410006.722033.118
 10016.82039.05310026.832048.26910036.832053.36210067.662057.26710078.492059.487
10099.092062.81210115.912062.83610129.352063.39810143.932067.15110172.862068.485
10201.782073.27210216.252073.71310226.252073.38110230.712071.88410250.862061.073
#Mann= 3 , 0 , 0
9749.181    0.04       09749.181    0.04       010250.86    0.04       0
#XS Ineff= 2 , 0
       0                               0
Bank Sta=9749.181,10250.86
Exp/Cntr=0.3,0.1

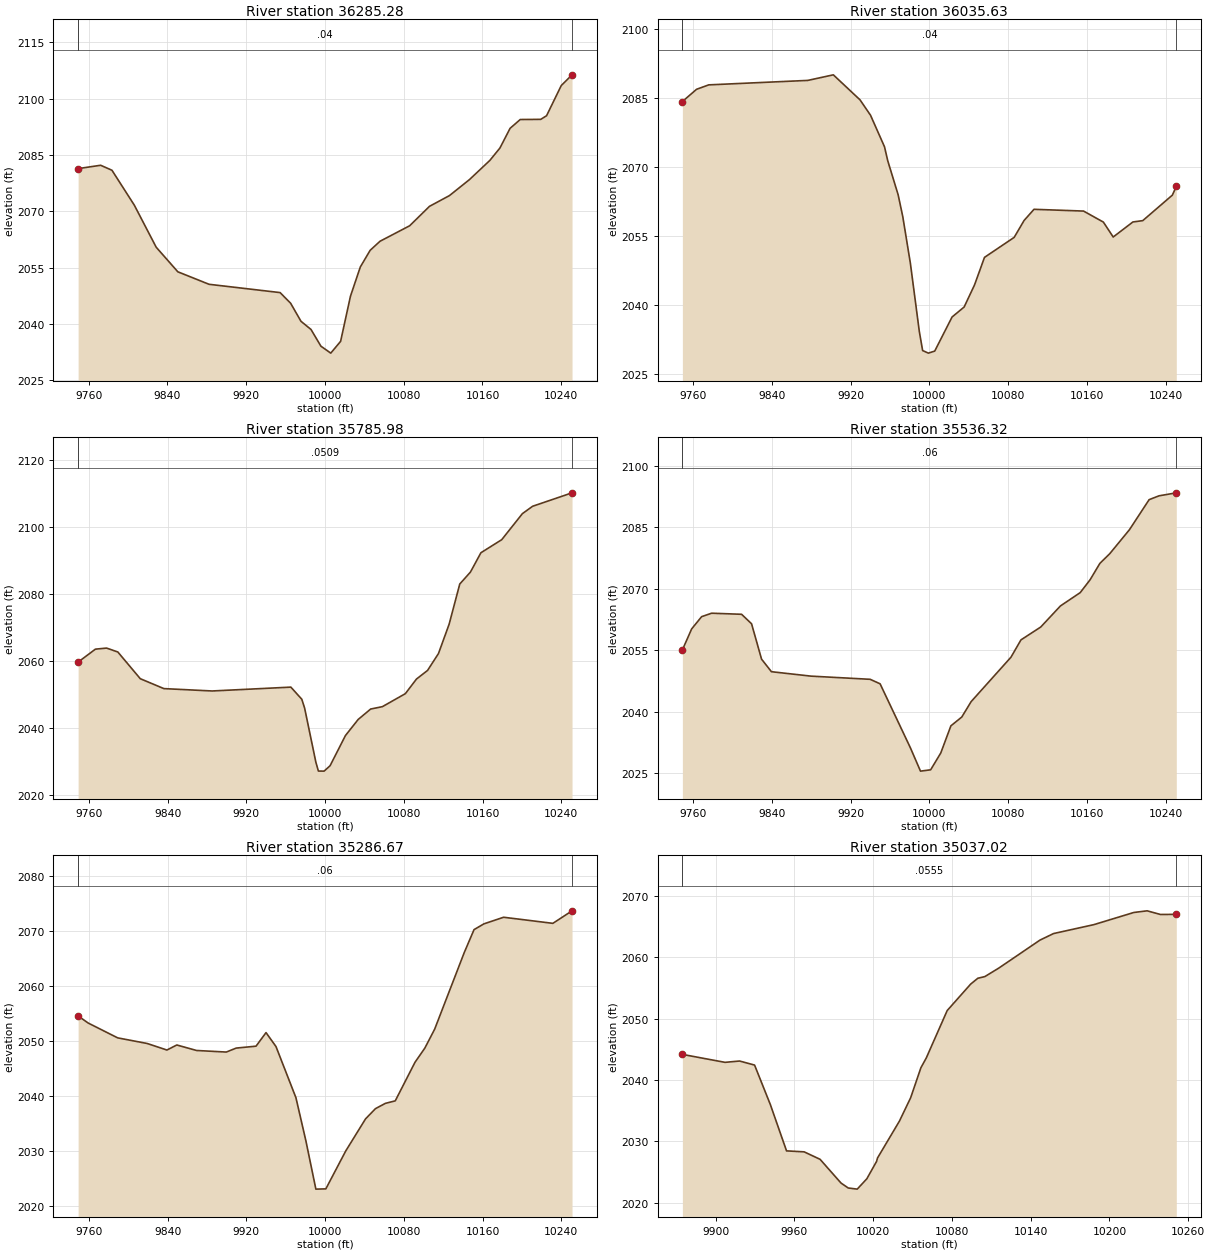
Type RM Length L Ch R = 1 ,36285.28,249.653200,249.653200,249.653200
XS GIS Cut Line= 6
698024.752116777763564.925850497697962.796013753763424.299352129
697960.814206246 763394.21654867 697977.61924978763341.561115591
697976.605497431763263.058486293697937.735302434763084.476770164
#Sta/Elev= 30
9749.2082081.3679772.1082082.2629783.601 2080.939806.3212071.634 9828.532060.441
9850.5282053.8959882.2142050.5719954.4132048.3629965.1072045.5229975.5952040.729
9985.7932038.5429995.8692034.09710005.872032.24610015.872035.38610025.872047.399
10035.882055.17710045.892059.62410055.892062.02710086.022066.15610106.162071.326
10126.492074.19710146.842078.46210167.442083.54510177.742086.86310188.042092.101
10198.342094.44210219.172094.48410225.08 2095.4510240.012103.48110250.97 2106.34
#Mann= 3 , 0 , 0
9749.208    0.04       09749.208    0.04       010250.97    0.04       0
#XS Ineff= 2 , 0
       0                               0
Bank Sta=9749.208,10250.97
Exp/Cntr=0.3,0.1

Type RM Length L Ch R = 1 ,36035.63,249.653100,249.653100,249.653100
XS GIS Cut Line= 6
698284.090068092763636.606242399698182.853903347763505.372155233
698093.113870838 763422.80235881698089.286628734763394.830129823
698101.613861468763290.273278972698099.625138583763210.983433779
#Sta/Elev= 30
9749.0942084.184  9763.52086.8439775.9122087.8079876.5322088.7779902.431 2089.99
9929.5162084.5569940.2342081.1989954.4252074.3389957.7042071.3139968.2652063.914
9972.9652059.1799980.6992049.0169989.7922034.1679993.1332030.046    99992029.484
10005.432029.92910023.062037.34310035.282039.50410045.842044.30510055.982050.303
10086.132054.649 10096.22058.32410106.272060.75210156.612060.36910176.722057.974
10186.722054.73310206.722057.99710216.742058.289 10246.82063.83210250.822065.735
#Mann= 3 , 0 , 0
9749.094    0.04       09749.094    0.04       010250.82    0.04       0
#XS Ineff= 2 , 0
       0                               0
Bank Sta=9749.094,10250.82
Exp/Cntr=0.3,0.1

Type RM Length L Ch R = 1 ,35785.98,249.653100,249.653100,249.653100
XS GIS Cut Line= 6
698447.398436889763490.415326908698384.080976414 763385.36159101
698282.217350988763272.677934894698254.556087014763233.784350269
698220.436602672763160.507866902698191.535313907763066.489307623
#Sta/Elev= 30
9749.0712059.7279766.6442063.5889778.043 2063.919789.442 2062.749812.2412054.777
9836.2372051.8239885.2522051.1179965.2442052.2669976.3722048.6429979.2312046.001
9990.6752029.8459993.2192027.236    99992027.21610005.072028.817 10020.72037.821
10033.642042.622 10046.32045.72810058.252046.44310081.562050.31310092.862054.669
10104.152057.24910115.232062.28110126.052071.02710136.872083.017 10147.72086.572
10158.372092.34310179.49 2096.2310200.492103.99610210.892106.20110250.952110.208
#Mann= 3 , 0 , 0
9749.071  0.0509       09749.071  0.0509       010250.95  0.0509       0
#XS Ineff= 2 , 0
       0                               0
Bank Sta=9749.071,10250.95
Exp/Cntr=0.3,0.1

Type RM Length L Ch R = 1 ,35536.32,249.653200,249.653200,249.653200
XS GIS Cut Line= 6
698518.181532449763454.267847064 698504.39179588763374.770732855
698500.823705952763301.203791818698506.479610713763250.583307243
698535.584200449763111.233654373698540.327808114762957.375775485
#Sta/Elev= 30
9749.1052055.0369758.5112060.177 9768.662063.175 9778.81 2064.029809.2582063.758
9819.4072061.4389829.5562052.7979839.5942049.7299879.705 2048.659939.9312047.871
9949.9932046.7729980.7472031.1539991.0312025.44210001.342025.76110011.63 2029.87
10021.922036.50710032.982038.65410042.482042.41910082.972053.277 10093.12057.501
10113.192060.64610133.242065.80110153.292069.04710163.322072.17910173.322076.203
10183.32 2078.5610203.322084.41410223.322091.75810233.322092.69610250.94 2093.43
#Mann= 3 , 0 , 0
9749.105    0.06       09749.105    0.06       010250.94    0.06       0
#XS Ineff= 2 , 0
       0                               0
Bank Sta=9749.105,10250.94
Exp/Cntr=0.3,0.1

Type RM Length L Ch R = 1 ,35286.67,249.653100,249.653100,249.653100
XS GIS Cut Line= 6
698732.577869441 763525.20270794698732.877020114763461.375582693
 698736.95336302763402.514887999698765.121002765763196.390378145
698765.856292138 763137.21066698698760.134634142763025.539136423
#Sta/Elev= 30
9749.0262054.5689759.2292053.2729789.2292050.5689819.2452049.5439839.2922048.351
9849.316 2049.279869.364 2048.27 9899.592047.982 9909.672048.7069929.8432049.055
9939.9762051.5269950.1082048.9879970.3742039.6699980.5062031.7999990.6392023.012
10000.772023.059   100212029.97110041.172035.82210051.212037.67610061.262038.635
10071.312039.09410091.352046.11310101.352048.69710111.352052.15210141.362066.082
10151.372070.28610161.392071.33510181.41 2072.5410231.482071.43110250.962073.711
#Mann= 3 , 0 , 0
9749.026    0.06       09749.026    0.06       010250.96    0.06       0
#XS Ineff= 2 , 0
       0                               0
Bank Sta=9749.026,10250.96
Exp/Cntr=0.3,0.1

Type RM Length L Ch R = 1 ,35037.02,249.653100,249.653100,249.653100
XS GIS Cut Line= 6
699018.704677277763305.111055283698994.269065299763251.391170985
 698923.85527745763172.206654243698895.080792283763120.274418648
698874.789397143763053.204879309698860.869697427 762973.11084408
#Sta/Elev= 30
9874.678 2044.179907.1532042.8769918.2682043.0919929.673 2042.439941.6782036.015
9954.0222028.4729967.4362028.3159979.5812027.0979995.4892023.244   100012022.435
10007.85 2022.2510015.152023.92610022.612026.76210023.312027.31310039.99 2033.31
10048.552037.11310056.362041.99910060.442043.58110076.392051.30110094.242055.599
10099.722056.55610105.072056.82810115.682058.20810147.072062.76510157.412063.829
10188.092065.27710218.542067.25710228.692067.52610238.842066.933 10250.92066.951
#Mann= 3 , 0 , 0
9874.678  0.0555       09874.678  0.0555       0 10250.9  0.0555       0
#XS Ineff= 2 , 0
       0                               0
Bank Sta=9874.678,10250.9
Exp/Cntr=0.3,0.1

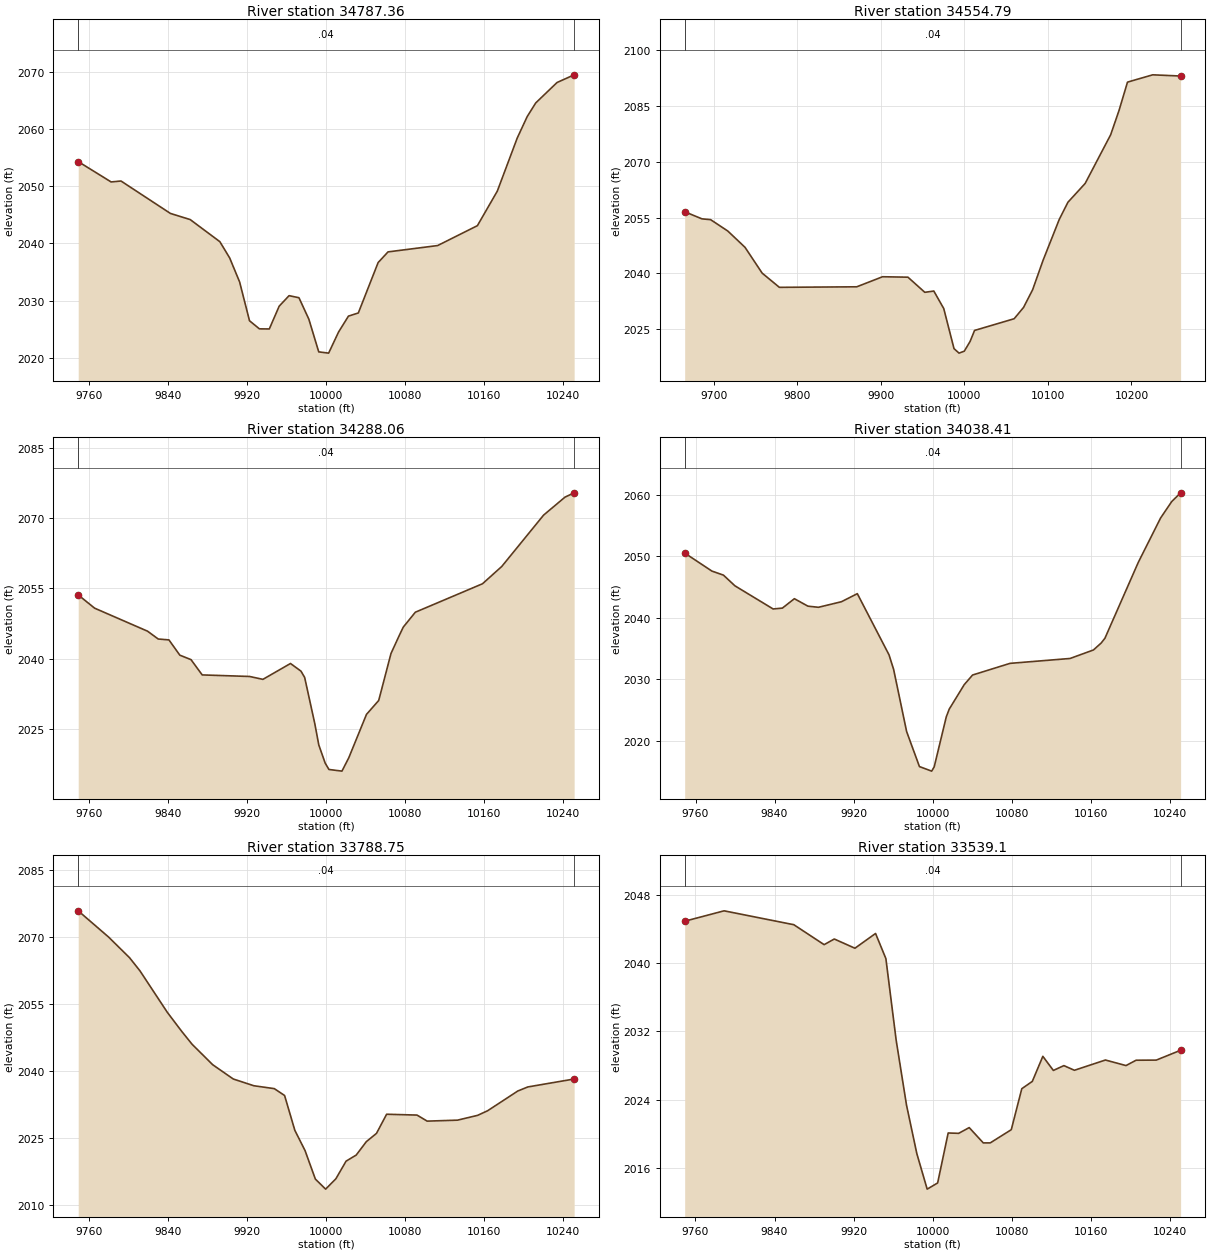
Type RM Length L Ch R = 1 ,34787.36,232.575300,232.575300,232.575300
XS GIS Cut Line= 6
699193.495183505763468.307888643699191.522164504763358.243958291
699185.257402628763218.482701946699181.524039193763157.265966048
 699174.76323472763084.363615038699160.164524999762967.831860569
#Sta/Elev= 30
9749.0172054.288 9782.332050.7369792.332  2050.9 9842.342045.2449862.3462044.173
9892.3762040.3199902.3862037.4589912.3962033.2869922.4062026.5189932.416 2025.11
9942.4262025.0889952.4362029.0669962.4462030.8989972.4562030.5379982.4662026.796
9992.476 2021.0910002.492020.87310012.512024.54310022.532027.32710032.552027.882
10052.582036.67110062.612038.53410112.822039.63910153.062043.10810173.222049.136
10193.372058.39110203.452062.13310212.092064.51810233.692068.08710250.992069.424
#Mann= 3 , 0 , 0
9749.017    0.04       09749.017    0.04       010250.99    0.04       0
#XS Ineff= 2 , 0
       09965.341                       0
Bank Sta=9749.017,10250.99
Exp/Cntr=0.3,0.1

Type RM Length L Ch R = 1 ,34554.79,266.731000,266.731000,266.731000
XS GIS Cut Line= 6
699347.807406068  763435.1455414699407.973395914763165.790500179
699400.847191066 763142.26108095699332.360035837763026.738774762
699315.884011894762956.889836222699307.485693693 762871.70085682
#Sta/Elev= 30
9665.2842056.5949686.0152054.6739696.3052054.4629716.8862051.4049737.4672047.028
9758.0472040.0699778.6282036.2569871.2422036.401 9902.112039.1079932.4752038.987
9952.6632034.9189963.4372035.2619975.3222030.5529987.6182019.7719993.6262018.561
9999.914 2019.0910006.872021.707 10012.22024.66410059.582027.80910070.832030.853
10081.762035.64110094.022043.43210113.532054.50610123.912059.13310144.542064.194
10175.07 2077.2910185.152083.86510195.222091.45410225.412093.417 10258.82093.094
#Mann= 3 , 0 , 0
9665.284    0.04       09665.284    0.04       0 10258.8    0.04       0
#XS Ineff= 2 , 0
       0                               0
Bank Sta=9665.284,10258.8
Exp/Cntr=0.3,0.1

Type RM Length L Ch R = 1 ,34288.06,249.653200,249.653200,249.653200
XS GIS Cut Line= 6
  699394.4807482763450.658851394699430.198179857763358.363614862
699468.373616869 763295.75950189699528.815886532763233.661425681
 699636.99502611763147.963570539699703.612035696763067.636234596
#Sta/Elev= 30
9749.0992053.6099765.7172050.7869819.2252045.8859830.0662044.2169840.9072044.024
9851.9092040.7759863.2292039.8219874.5482036.5649922.582 2036.239935.9642035.616
9963.8952038.996 9974.492037.3689978.2162036.0319988.4592026.2079992.5372021.631
    99992017.76710002.772016.41310015.952016.05910022.922018.92810040.762028.143
10053.162031.12110065.572041.12510073.622044.81410077.972046.74310090.222049.927
 10158.22055.993 10177.72059.68510220.012070.62510241.672074.455 10250.92075.369
#Mann= 3 , 0 , 0
9749.099    0.04       09749.099    0.04       0 10250.9    0.04       0
#XS Ineff= 2 , 0
       0                               0
Bank Sta=9749.099,10250.9
Exp/Cntr=0.3,0.1

Type RM Length L Ch R = 1 ,34038.41,249.653100,249.653100,249.653100
XS GIS Cut Line= 6
 699577.58881307763588.581021556699611.935801978763531.598207464
699657.229627144763466.080131483699790.437233606763302.867753654
699824.697109718763248.939959982699862.023200092763177.031937925
#Sta/Elev= 30
9749.0452050.5079776.5782047.5819788.2552046.9259799.9312045.1869838.5532041.433
9847.9142041.5749860.0712043.0999873.7232041.8929884.3852041.7059907.7052042.608
 9923.762043.916 9955.872033.982 9960.522031.6159973.6532021.5479986.6222015.865
    99992015.12810001.552015.81910013.792023.93810016.742025.17710031.922029.151
10040.372030.71710078.272032.60910139.032033.40210162.722034.78310170.562035.914
10174.342036.68910208.142049.01210230.682056.19710241.952058.86410250.922060.274
#Mann= 3 , 0 , 0
9749.045    0.04       09749.045    0.04       010250.92    0.04       0
#XS Ineff= 2 , 0
       0                               0
Bank Sta=9749.045,10250.92
Exp/Cntr=0.3,0.1

Type RM Length L Ch R = 1 ,33788.75,249.653100,249.653100,249.653100
XS GIS Cut Line= 6
 699866.29991528763734.254330499699906.257483287763615.153632567
699940.415338424763493.507410322699944.519069237 763478.43200314
699969.369676694763369.679020638699991.551842955763248.897425827
#Sta/Elev= 30
9749.0242075.9429779.8812070.0459800.9762065.4399811.5242062.4979839.2562053.186
9853.7152048.9559864.263 2046.059885.1952041.4529905.9672038.2629926.7392036.752
9947.5112036.1019957.8982034.5669968.2842026.766 9978.672022.1929989.0562015.836
9999.4442013.58610009.822015.90510020.142019.854 10030.4 2021.2210040.662024.227
10050.922026.07510061.182030.36510091.952030.17710102.212028.82310132.94 2029.04
10153.272030.11610163.442031.15210193.942035.56910204.112036.48210250.982038.262
#Mann= 3 , 0 , 0
9749.024    0.04       09749.024    0.04       010250.98    0.04       0
#XS Ineff= 2 , 0
       0                               0
Bank Sta=9749.024,10250.98
Exp/Cntr=0.3,0.1

Type RM Length L Ch R = 1 , 33539.1,256.431600,256.431600,256.431600
XS GIS Cut Line= 6
700227.801723875763774.842056735700226.646636398763705.613391702
700212.439671397763628.290557235700184.856687494763536.409124241
700130.274300568763386.520625527 700107.00430607763290.912933833
#Sta/Elev= 30
 9749.062044.9499788.9372046.1719859.5052044.5429890.1832042.1999900.4792042.861
9921.3612041.7799942.2432043.5129952.6842040.5619963.1252030.9539973.5652023.356
9984.0062017.6589994.4662013.48910005.072014.21410015.722020.08110026.362020.041
10037.012020.71410051.252018.919 10058.32018.91910079.59 2020.4710090.242025.283
10100.882026.14110111.532029.08310122.182027.42610132.822027.99410143.472027.447
10174.88 2028.6510195.692027.99910205.912028.62710226.342028.64110250.962029.797
#Mann= 3 , 0 , 0
 9749.06    0.04       0 9749.06    0.04       010250.96    0.04       0
#XS Ineff= 2 , 0
       0                               0
Bank Sta=9749.06,10250.96
Exp/Cntr=0.3,0.1