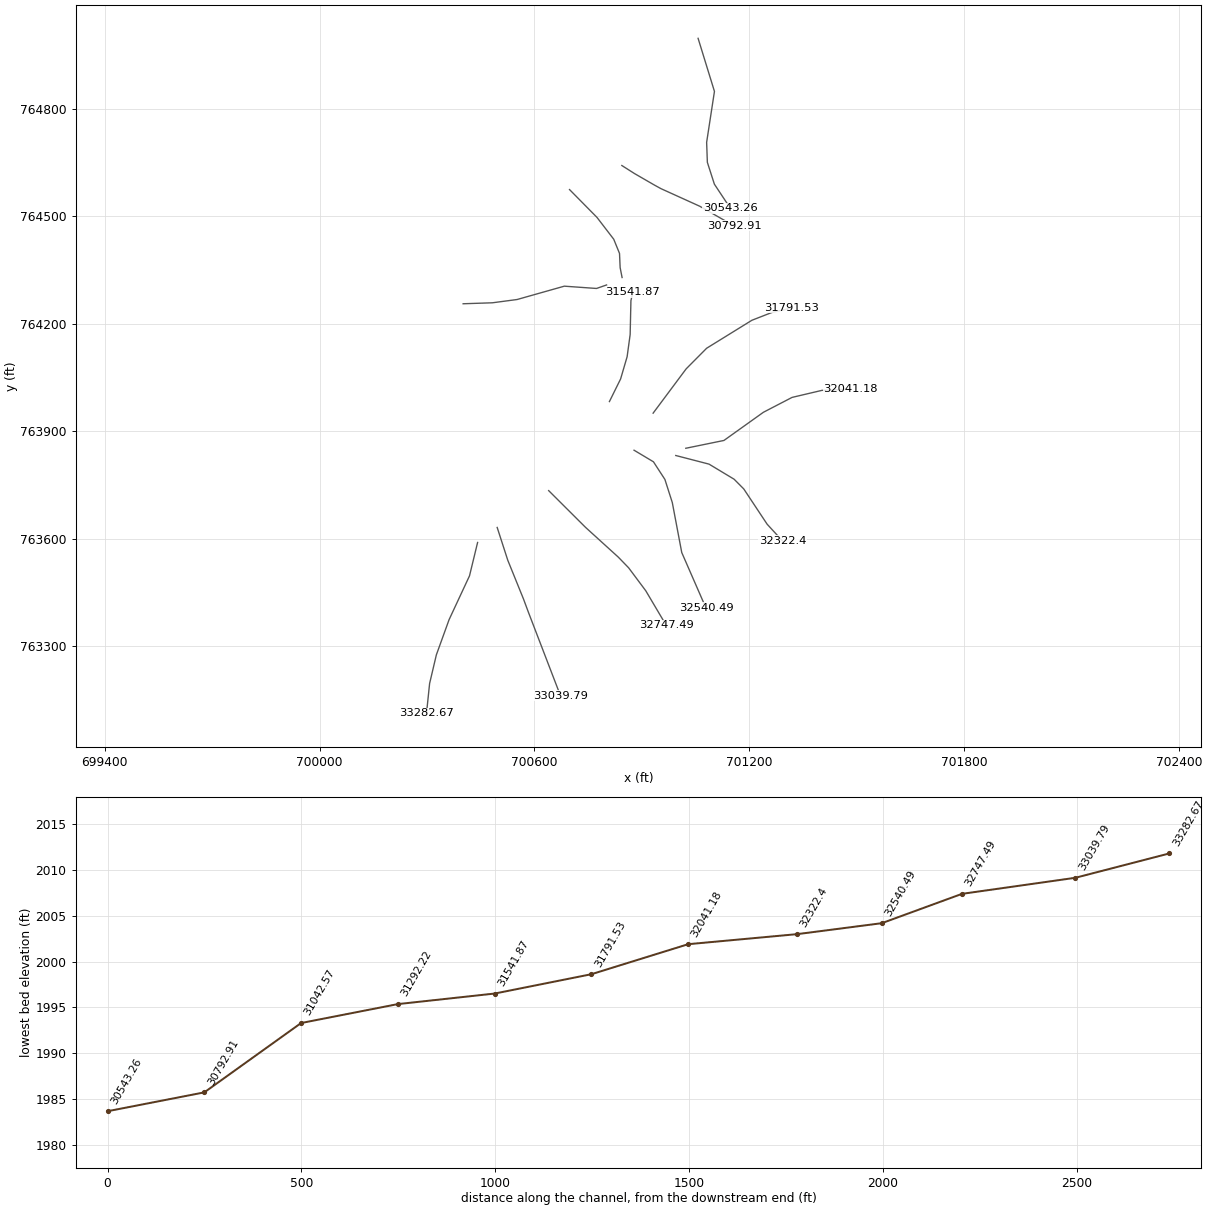
HEC-RAS study 14441_ras.prj: 14441

--- 14441_ras.g01 (geometry) --- (continued)

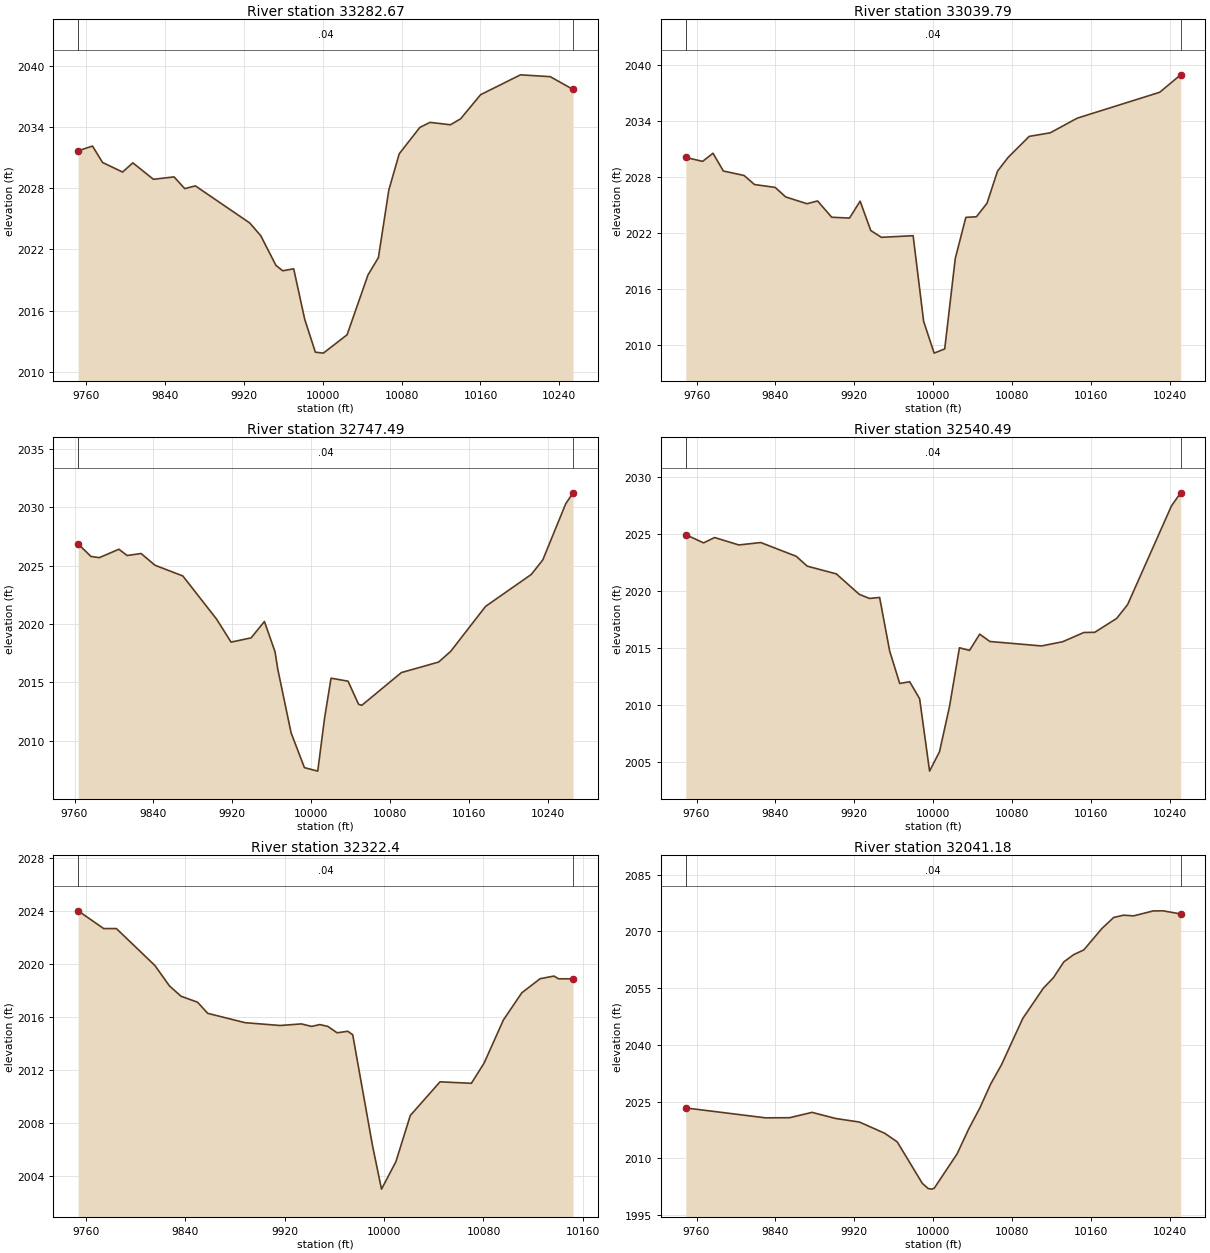
Type RM Length L Ch R = 1 ,33282.67,242.874700,242.874700,242.874700
XS GIS Cut Line= 6
700441.253839435763589.330490154700418.651345666763496.124477776
700361.655216834763373.854317597700326.070823219763275.487642418
700307.235082704 763195.51444282700298.503480717763111.974064909
#Sta/Elev= 30
9752.0032031.6629766.5662032.1229776.7282030.5159797.0532029.5749807.4872030.476
 9828.362028.8639849.2752029.1019860.0872027.9519870.8992028.2189926.0942024.578
9937.2242023.3279952.6192020.4189959.4832019.8969970.6132020.0879981.7432015.147
9992.5772011.91610000.672011.82110024.742013.62110045.952019.49110056.512021.188
10067.062027.80810077.612031.36310098.51 2033.9510108.862034.44710129.562034.211
 10139.82034.78910160.192037.16110200.632039.10710230.812038.92610253.892037.674
#Mann= 3 , 0 , 0
9752.003    0.04       09752.003    0.04       010253.89    0.04       0
#XS Ineff= 2 , 0
       0                               0
Bank Sta=9752.003,10253.89
Exp/Cntr=0.3,0.1

Type RM Length L Ch R = 1 ,33039.79,292.299300,292.299300,292.299300
XS GIS Cut Line= 6
700495.966685518763631.259874122700525.513779746763539.833080084
 700569.47255157763431.353369594700582.311371209763396.821210547
700583.001426738 763394.94402559700672.631407299763161.584359888
#Sta/Elev= 30
9749.0282030.1029766.116 2029.689776.625 2030.559787.1342028.6479808.1532028.171
9818.6622027.203 9839.682026.8949850.3252025.8769871.9052025.1479882.6952025.443
9896.9962023.7029915.064 2023.619925.8542025.4219936.6442022.2789947.4342021.551
9979.6052021.7279990.2742012.55810000.942009.15810011.652009.61110022.362019.283
10033.082023.68910043.792023.751 10054.52025.18910065.212028.63710075.93  2030.1
10097.352032.35410118.77 2032.7410146.032034.304 10229.72037.07510250.982038.942
#Mann= 3 , 0 , 0
9749.028    0.04       09749.028    0.04       010250.98    0.04       0
#XS Ineff= 2 , 0
       0                               0
Bank Sta=9749.028,10250.98
Exp/Cntr=0.3,0.1

Type RM Length L Ch R = 1 ,32747.49,207.007000,207.007000,207.007000
XS GIS Cut Line= 6
700639.800866687763734.158029755 700742.40518409763631.869081256
700834.388679765763548.284901245 700863.12716719763518.573921751
700911.033369064 763454.37533094700967.705068839763358.621779228
#Sta/Elev= 30
9763.6642026.8679776.6362025.7969785.1262025.6949804.9642026.4129813.3672025.877
9827.4882026.0489841.6082025.0429869.8492024.1249904.1112020.4219918.7572018.457
9939.0842018.822  9952.62020.2249963.351 2017.639966.1152016.1439979.6312010.688
9993.1472007.70610006.662007.40610013.652011.98310020.152015.369 10037.42015.111
 10048.1 2013.1310051.322013.04310091.562015.85110129.252016.748 10141.42017.655
10176.842021.51410223.322024.25910234.942025.50410258.182030.31110265.592031.246
#Mann= 3 , 0 , 0
9763.664    0.04       09763.664    0.04       010265.59    0.04       0
#XS Ineff= 2 , 0
       0                               0
Bank Sta=9763.664,10265.59
Exp/Cntr=0.3,0.1

Type RM Length L Ch R = 1 ,32540.49,218.087100,218.087100,218.087100
XS GIS Cut Line= 6
700878.256904684763847.046907777 700932.47219459763814.676308772
 700964.46194478763765.414737191700985.092281783763700.876416971
701011.483710503 763561.26990349701079.032176307763406.567277044
#Sta/Elev= 30
9749.1192024.9549767.1632024.2359778.3362024.7039802.9262024.0529825.0882024.264
 9861.042023.0589872.287 2022.199901.7642021.5129925.0392019.7169935.4022019.357
 9945.662019.4429955.8452014.7459966.0292011.8979976.1622012.0449986.2392010.553
9996.3152004.20110006.412005.91110016.512009.86710026.612015.02710036.832014.797
10047.142016.22310057.462015.57910109.732015.18910131.222015.55610152.822016.369
 10163.82016.38410186.022017.60210197.132018.81510241.572027.47610250.932028.626
#Mann= 3 , 0 , 0
9749.119    0.04       09749.119    0.04       010250.93    0.04       0
#XS Ineff= 2 , 0
       0                               0
Bank Sta=9749.119,10250.93
Exp/Cntr=0.3,0.1

Type RM Length L Ch R = 1 , 32322.4,281.219200,281.219200,281.219200
XS GIS Cut Line= 6
700994.835500731763832.268390921701087.664287366763808.196004146
701157.776292333763766.020115874701184.715061494763738.917208078
701249.995980101 763640.40498504701292.884214841763593.724788358
#Sta/Elev= 30
9753.9122024.0339774.4672022.692 9784.662022.6949815.7052019.898 9827.352018.363
9836.6782017.5799849.9582017.132 9858.162016.2889888.2012015.5839916.4132015.369
9933.507 2015.499941.7692015.302 9948.352015.439 9954.742015.3059962.2512014.819
 9970.842014.9339974.811 2014.679990.669 2006.339997.9722003.00710009.552005.079
10021.152008.57110045.062011.11510070.282011.00310080.482012.52310096.082015.792
10110.862017.84110125.642018.90710136.762019.10310140.422018.89710152.072018.896
#Mann= 3 , 0 , 0
9753.912    0.04       09753.912    0.04       010152.07    0.04       0
#XS Ineff= 2 , 0
       0                               0
Bank Sta=9753.912,10152.07
Exp/Cntr=0.3,0.1

Type RM Length L Ch R = 1 ,32041.18,249.653100,249.653100,249.653100
XS GIS Cut Line= 6
701022.794644085763852.493119523701129.369264142763874.312846905
701239.654320835763953.072460858701319.648668686763994.567401526
701403.009626359764014.214547363701482.831008303764017.645698385
#Sta/Elev= 30
9749.1132023.3519829.7742020.7419854.379 2020.779877.1052022.1839900.9152020.576
9925.3112019.6149950.7712016.6679963.5012014.3949988.9612003.4229994.8862002.068
9998.6632001.90910001.072002.16610024.26 2011.2510035.862017.74510047.372023.404
10058.282029.68810069.182034.73710090.732046.96610111.552054.94410121.962057.789
10132.362061.91310142.512063.86510152.662065.08110170.932070.72110182.98 2073.66
10193.022074.26310203.06 2074.0810223.062075.38610233.062075.41310250.892074.589
#Mann= 3 , 0 , 0
9749.113    0.04       09749.113    0.04       010250.89    0.04       0
#XS Ineff= 2 , 0
       0                               0
Bank Sta=9749.113,10250.89
Exp/Cntr=0.3,0.1

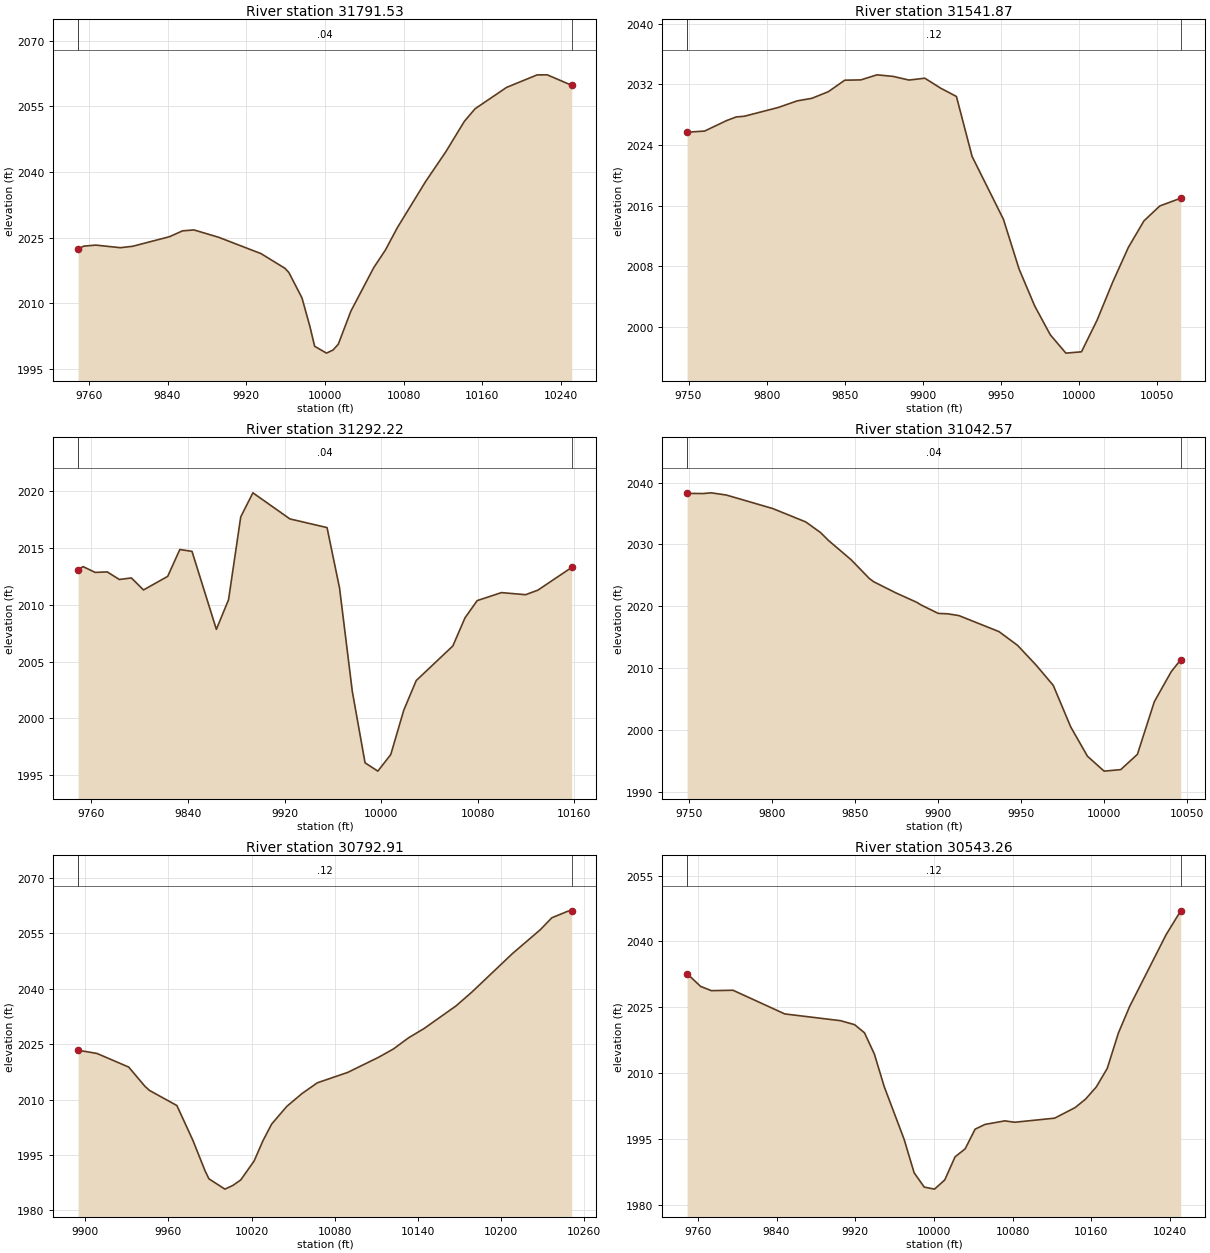
Type RM Length L Ch R = 1 ,31791.53,249.653200,249.653200,249.653200
XS GIS Cut Line= 6
 700931.54609982763950.579682177701023.860928452  764074.3409951
701081.088514789764131.928270252701207.416524349 764210.01335347
701262.699171353764231.604140475701319.292249639764244.669050832
#Sta/Elev= 30
9749.0912022.4389754.8672023.0739767.0812023.3129792.0322022.7199804.5072023.037
9841.9342025.2229855.2192026.5639866.8852026.7759891.8362025.1069935.0342021.367
 9959.262018.0289963.3152017.068 9976.672011.2539984.8012004.6739989.5452000.202
10001.611998.63310008.211999.33710013.592000.66710026.362008.21210049.542018.127
10061.522022.193 10073.52027.24610102.222037.78310123.012044.66710141.712051.569
10152.622054.45210184.662059.33510215.712062.19310225.982062.20710250.912059.812
#Mann= 3 , 0 , 0
9749.091    0.04       09749.091    0.04       010250.91    0.04       0
#XS Ineff= 2 , 0
       0                               0
Bank Sta=9749.091,10250.91
Exp/Cntr=0.3,0.1

Type RM Length L Ch R = 1 ,31541.87,249.653100,249.653100,249.653100
XS GIS Cut Line= 6
700809.487701802763982.949824765700840.723760011764046.117178945
 700858.88945756764108.149030291700867.389014946764170.177155674
700869.525682914764264.696584999700874.794774411764287.876945699
#Sta/Elev= 30
9749.0682025.6719760.2642025.8229774.4022027.2089780.5742027.6879785.7122027.777
9807.5152028.9379819.6342029.8079829.0112030.1439839.5682031.0179850.1092032.536
9860.4292032.5759870.7492033.2449881.0682033.0389891.2682032.5539901.4142032.798
9911.5592031.483 9921.672030.3869931.7172022.469 9951.79 2014.189961.7922007.632
9971.7952002.7589981.7971998.9479991.799 1996.52 10001.81996.695 10011.82000.874
10021.812005.89210031.812010.45910041.822013.96910051.97 2015.94 10065.42016.964
#Mann= 3 , 0 , 0
9749.068    0.12       09749.068    0.12       0 10065.4    0.12       0
#XS Ineff= 2 , 0
       0                               0
Bank Sta=9749.068,10065.4
Exp/Cntr=0.3,0.1

Type RM Length L Ch R = 1 ,31292.22,249.653100,249.653100,249.653100
XS GIS Cut Line= 6
 700400.85893816 764256.13148863700482.610688768764258.834718434
700551.668396334764268.008122509700683.480444452764305.267528135
700773.422149916764298.852470194700801.533740313764308.649096385
#Sta/Elev= 30
9749.0772013.1019753.2192013.3659763.2192012.856 9773.22  2012.9 9783.222012.233
 9793.222012.3689803.2362011.3129823.2782012.5079833.315 2014.879843.4032014.707
9863.5792007.8459873.6672010.4539883.7552017.7419893.8422019.8589924.4852017.562
9955.2352016.7999965.5892011.4789976.1552002.384 9986.72  1996.19997.2861995.369
10008.01 1996.8310018.762000.72710029.09 2003.3410059.412006.38510069.48 2008.86
10079.562010.37310099.642011.07810119.672010.89510129.77 2011.2910157.872013.295
#Mann= 3 , 0 , 0
9749.077    0.04       09749.077    0.04       010157.87    0.04       0
#XS Ineff= 2 , 0
       0                               0
Bank Sta=9749.077,10157.87
Exp/Cntr=0.3,0.1

Type RM Length L Ch R = 1 ,31042.57,249.653200,249.653200,249.653200
XS GIS Cut Line= 6
700698.042277761764575.095383906700774.775693275764497.292601985
700821.509726013  764436.3805015700837.665837039764396.744130913
700839.433261773 764357.08511553700844.830617472764329.430893821
#Sta/Elev= 30
9749.1032038.2629758.7912038.2359763.6112038.3519772.7162037.9959800.5652035.815
9820.5292033.6419829.4172031.9259834.2032030.6449847.8762027.5069858.766 2024.49
9861.3882023.9649874.4662022.1919887.3312020.6299890.1672020.1669900.3032018.831
9906.0112018.765 9912.712018.4799936.8092015.8889947.9982013.6679959.1432010.472
9969.0472007.3249969.5942007.1229979.9822000.4669990.0741995.71410000.091993.301
 10010.11993.54410020.141996.02410030.312004.53810040.492009.40210046.212011.337
#Mann= 3 , 0 , 0
9749.103    0.04       09749.103    0.04       010046.21    0.04       0
#XS Ineff= 2 , 0
       0                               0
Bank Sta=9749.103,10046.21
Exp/Cntr=0.3,0.1

Type RM Length L Ch R = 1 ,30792.91,249.653100,249.653100,249.653100
XS GIS Cut Line= 6
700844.177522573764642.266398444700879.419833707764619.872520517
700935.245635886764587.626711052700953.476050064764577.630041091
701061.933485076764528.451933584701157.468569353764473.772694141
#Sta/Elev= 30
9894.7752023.3639908.3242022.4989931.2942018.7979942.9732013.604 9946.282012.472
9966.0632008.3789977.6081998.948  9986.31990.7639989.1531988.53110000.711985.731
10006.461986.73510012.121988.21910021.791993.36410028.161998.85510034.442003.367
10045.422008.171 10056.42011.64210067.382014.53510089.342017.359 10111.32021.398
10122.282023.70310133.262026.74210144.412029.24510167.45 2035.3710178.982039.145
10208.222049.56910228.352056.04310236.59 2059.2510248.112061.02110250.95 2061.13
#Mann= 3 , 0 , 0
9894.775    0.12       09894.775    0.12       010250.95    0.12       0
#XS Ineff= 2 , 0
       0                               0
Bank Sta=9894.775,10250.95
Exp/Cntr=0.3,0.1

Type RM Length L Ch R = 1 ,30543.26,249.653200,249.653200,249.653200
XS GIS Cut Line= 6
701057.158420779764997.526908257701102.835517581764849.301309839
701081.013653074764706.970936998701083.048792551764651.124113396
701102.644765701764590.194996306701147.048668765 764523.14198164
#Sta/Elev= 30
9749.1012032.6939762.8482029.7839773.8212028.8189795.768 2028.91 9848.382023.525
9905.1052021.9869919.4112021.0769929.4142019.2299939.4382014.4029949.4812006.979
 9969.651995.0259979.8651987.3899990.1571984.12910000.591983.67210011.011985.773
10021.43 1991.0110031.711992.83610041.861997.31910051.991998.397   100721999.197
10082.011998.885 10122.71999.81510143.462002.21710154.232004.173   10165 2006.92
 10176.12011.11910187.492019.19310198.892025.21910235.952041.55110250.822046.976
#Mann= 3 , 0 , 0
9749.101    0.12       09749.101    0.12       010250.82    0.12       0
#XS Ineff= 2 , 0
       0                               0
Bank Sta=9749.101,10250.82
Exp/Cntr=0.3,0.1