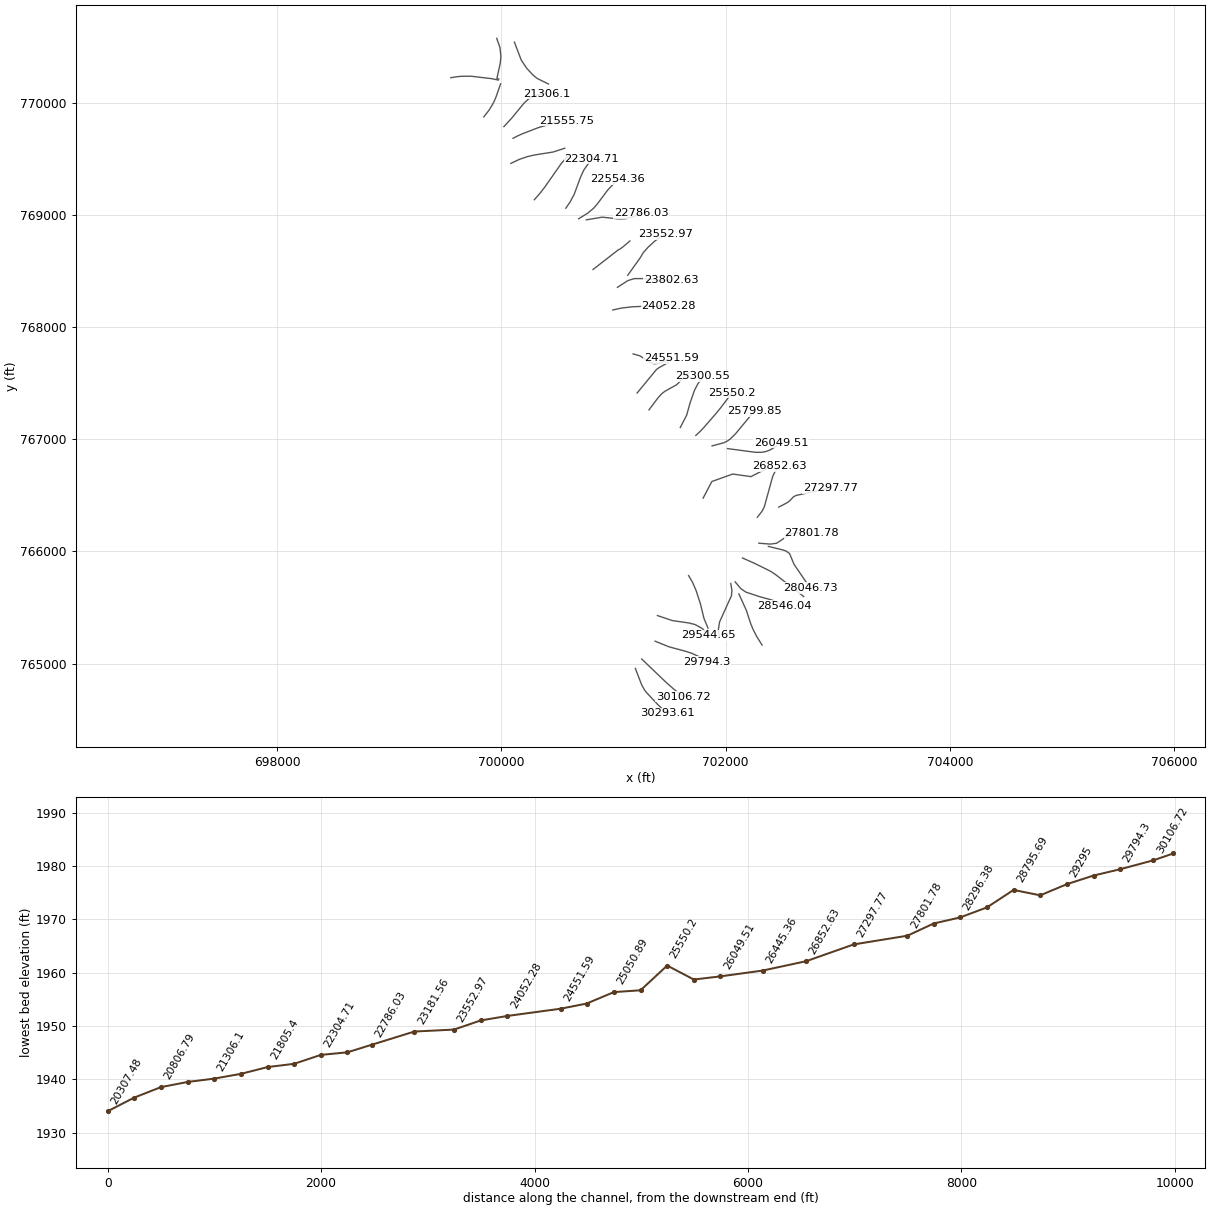
HEC-RAS study 14441_ras.prj: 14441

--- 14441_ras.g01 (geometry) --- (continued)

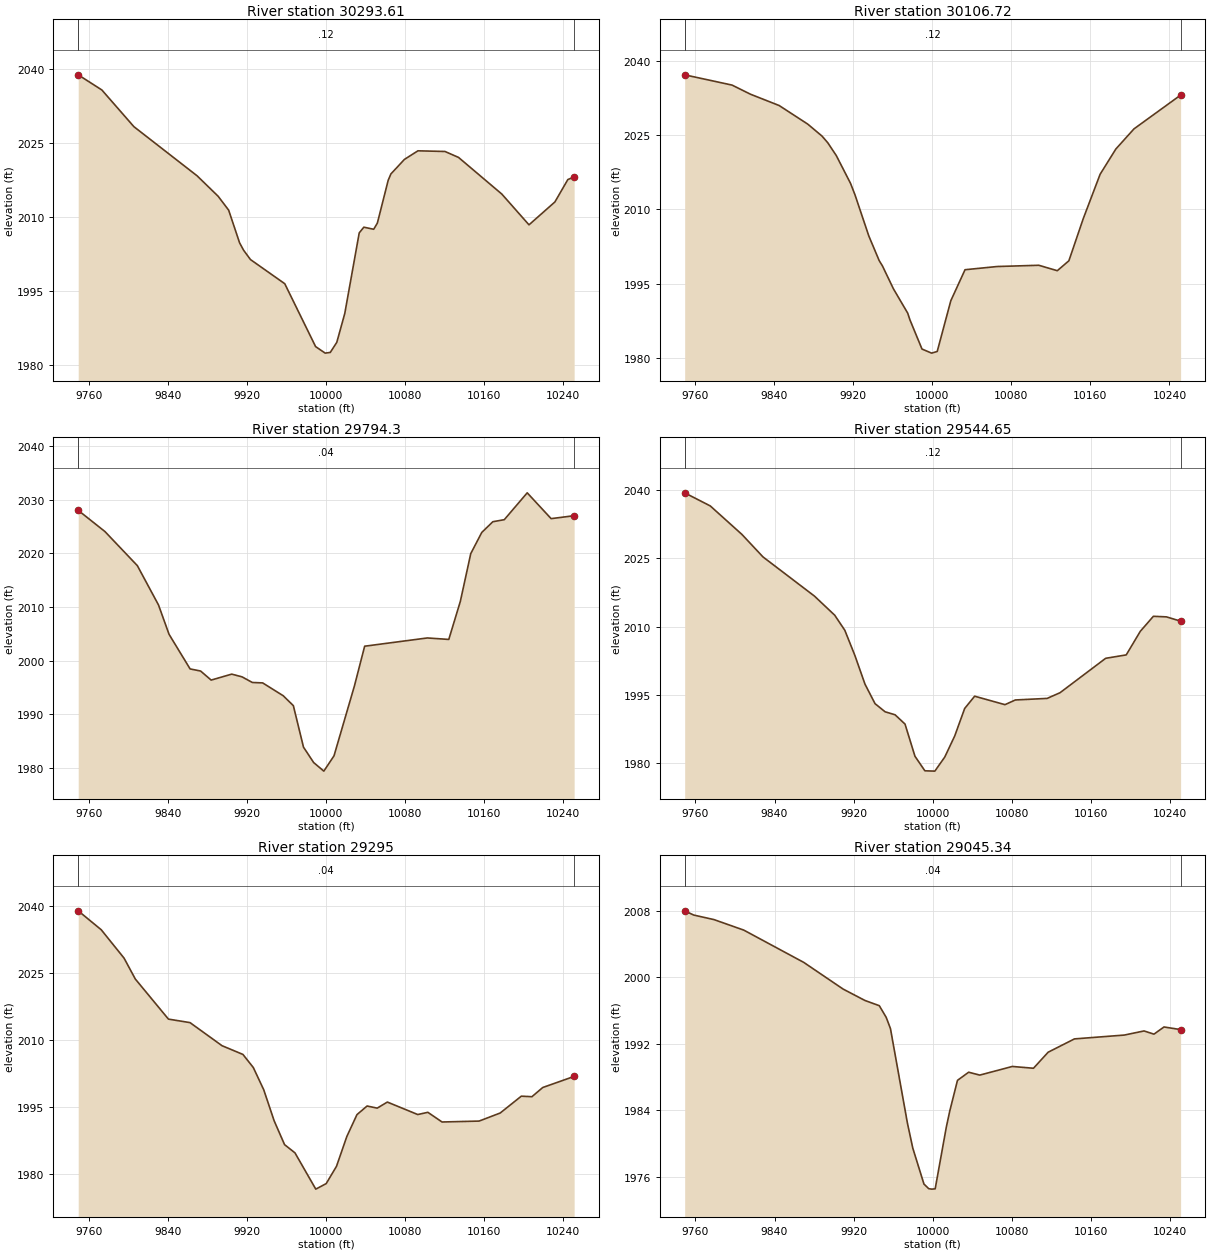
Type RM Length L Ch R = 1 ,30293.61,186.887800,186.887800,186.887800
XS GIS Cut Line= 6
701193.898467206764957.050028659701249.417347946764812.988367979
701275.527764544764764.667979145701294.816588411764740.650350919
701398.146192392764630.139395966701479.872587315764556.020074587
#Sta/Elev= 30
9749.0632038.7289772.9812035.6629805.4182028.2289869.3682018.273 9890.72 2014.12
9901.3422011.3099912.3392004.7169916.4432003.196 9923.422001.3019958.1031996.412
9989.2991983.678    99991982.34910004.171982.49210010.761984.53510018.821990.361
10033.462006.70310038.132007.86310048.112007.44210051.822008.69610062.76 2017.34
 10065.52018.64310079.19 2021.5910092.882023.33310120.25  2023.210133.942022.001
10177.822014.56410205.282008.33810231.492012.97310244.592017.50810250.982018.048
#Mann= 3 , 0 , 0
9749.063    0.12       09749.063    0.12       010250.98    0.12       0
#XS Ineff= 2 , 0
       0                               0
Bank Sta=9749.063,10250.98
Exp/Cntr=0.3,0.1

Type RM Length L Ch R = 1 ,30106.72,312.418400,312.418400,312.418400
XS GIS Cut Line= 6
701250.369586902765041.129414754701430.932468347764868.238177526
701432.364175885764866.841677069701479.104503859764822.647254971
 701538.47966428764770.961853857701621.770055873764703.887091739
#Sta/Elev= 30
9749.3152037.1229797.2612035.0559816.0152033.2079844.9342030.9399873.8522027.198
9888.3122024.7859894.1762023.4359902.7712020.859 9917.232015.2449921.8662012.855
9935.7112004.6569946.1491999.7219949.5561998.6039960.6081994.0199975.0681989.113
9977.2461987.7969989.5271981.8829999.3041981.06210004.931981.39610018.691991.618
10033.091997.86310065.631998.50810107.74 1998.7610126.481997.665 10138.21999.664
10152.722008.144 10169.82017.08410185.742022.17810204.082026.23310251.292033.039
#Mann= 3 , 0 , 0
9749.315    0.12       09749.315    0.12       010251.29    0.12       0
#XS Ineff= 2 , 0
       0                 10069.1       0
Bank Sta=9749.315,10251.29
Exp/Cntr=0.3,0.1

Type RM Length L Ch R = 1 , 29794.3,249.653200,249.653200,249.653200
XS GIS Cut Line= 6
701370.354134239 765199.67666213701494.824010004765149.326726425
701640.783115616765110.421581981701698.758611562765091.015829505
701763.977931632765060.929554268701834.272131161765016.029874377
#Sta/Elev= 30
 9749.042028.046 9776.04  2024.19808.9052017.7249830.3172010.3829840.9682004.916
9862.2721998.4559872.923 1998.069883.5711996.3719904.4241997.483 9914.851996.972
9925.2761995.9259935.7021995.8449956.4681993.4559966.7581991.6049977.047 1983.85
9987.3361980.9779997.6251979.38110007.911982.23610028.53 1995.2510038.932002.692
10102.392004.23310124.072003.95810135.742011.04710146.312019.97510157.47 2023.93
10168.662025.92410180.232026.30410203.442031.31710227.632026.50110250.942027.047
#Mann= 3 , 0 , 0
 9749.04    0.04       0 9749.04    0.04       010250.94    0.04       0
#XS Ineff= 2 , 0
       0                               0
Bank Sta=9749.04,10250.94
Exp/Cntr=0.3,0.1

Type RM Length L Ch R = 1 ,29544.65,249.653100,249.653100,249.653100
XS GIS Cut Line= 6
701390.786904227 765428.32674656 701524.27709986765383.609342518
701674.084448297765361.706900593701727.328988914765348.069989585
701791.431148647765312.320932475701847.127141008765254.144596144
#Sta/Elev= 30
9749.0722039.4279774.9432036.5479806.9972030.2729828.3012025.3269880.3152016.716
9900.8952012.4979911.0872009.1899921.2782003.648 9931.47 1997.359941.6621993.039
9951.8531991.2489961.955 1990.59 9972.011988.5479982.0661981.4669992.1211978.262
10002.171978.19310012.241981.299 10022.31985.93310032.361991.97710042.441994.678
10073.141992.81810083.611993.84910115.821994.19510128.831995.44310175.012003.015
10195.822003.76710210.092008.964 10223.32012.26110236.512012.13310250.852011.194
#Mann= 3 , 0 , 0
9749.072    0.12       09749.072    0.12       010250.85    0.12       0
#XS Ineff= 2 , 0
       0                               0
Bank Sta=9749.072,10250.85
Exp/Cntr=0.3,0.1

Type RM Length L Ch R = 1 ,   29295,249.653100,249.653100,249.653100
XS GIS Cut Line= 6
701668.995130584765784.722152479701704.397493784765723.873425334
701735.285416135 765652.74531759701773.415419766765535.951061202
701805.466024634765404.894062367701841.872829078765316.027601982
#Sta/Elev= 30
9749.0322038.9179772.3242034.6789795.4272028.3249806.8052023.6479840.352 2014.66
  9862.22013.8769894.6042008.7039915.7322006.7519926.2672003.8129936.8011998.831
9947.3351991.8869957.8691986.5479968.4041984.7049989.4721976.579   100001977.814
10010.451981.69610020.881988.35810031.141993.26310041.391995.19610051.641994.722
 10061.9 1996.0810092.661993.28610102.921993.78310117.251991.61610154.761991.822
10176.121993.62810197.481997.40110208.221997.28110219.181999.34110250.962001.829
#Mann= 3 , 0 , 0
9749.032    0.04       09749.032    0.04       010250.96    0.04       0
#XS Ineff= 2 , 0
       0                               0
Bank Sta=9749.032,10250.96
Exp/Cntr=0.3,0.1

Type RM Length L Ch R = 1 ,29045.34,249.653200,249.653200,249.653200
XS GIS Cut Line= 6
702045.119998961765713.887968377702055.448434714765651.116451839
702051.019134217765605.118241627701945.052964923765371.225299959
701934.250190929  765301.6915682701941.567077959 765238.48271422
#Sta/Elev= 30
9749.1122008.0159758.2672007.505 9778.752006.9599808.944 2005.699869.6432001.799
9909.4131998.5889931.5061997.2159946.0241996.5879953.0161995.1799957.3191993.825
9974.5261982.4119979.908 1979.439991.2031975.1029996.0361974.544    99991974.489
10002.561974.52310013.841981.96510017.381983.92810025.131987.59210036.421988.573
 10047.71988.225 10080.61989.26710102.02 1989.0510116.84 1990.9810143.471992.586
10193.851993.04710213.891993.54410223.921993.15910234.071994.02310250.891993.707
#Mann= 3 , 0 , 0
9749.112    0.04       09749.112    0.04       010250.89    0.04       0
#XS Ineff= 2 , 0
       0                               0
Bank Sta=9749.112,10250.89
Exp/Cntr=0.3,0.1

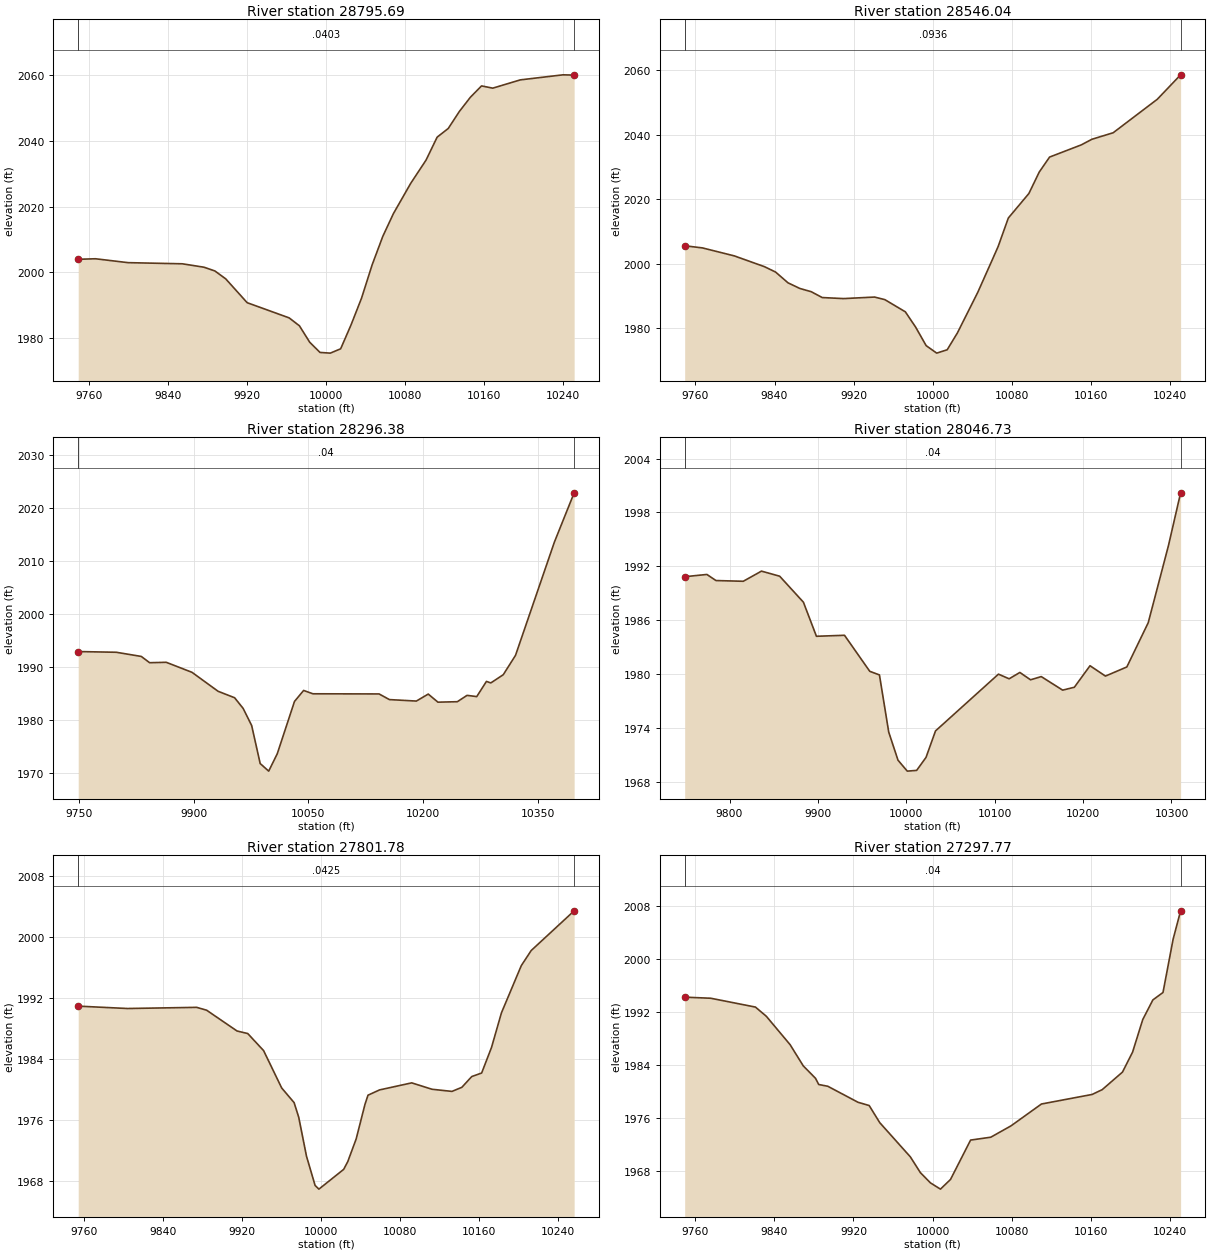
Type RM Length L Ch R = 1 ,28795.69,249.653100,249.653100,249.653100
XS GIS Cut Line= 6
702117.451157468765620.897867994702184.956400848765472.413309276
702221.073443912765360.889186072702241.996667968765308.892998852
702278.421554771765237.495155187702324.237743042765165.534693068
#Sta/Elev= 30
9749.0322003.9979766.4962004.1559799.4512002.9769854.3752002.6269876.345 2001.59
 9887.332000.4539898.3151998.0569920.0121990.8169962.4711986.208 9972.89  1983.8
 9983.311978.807 9993.731975.70610004.151975.49810014.631976.813 10025.11984.043
10035.761992.19610046.542002.35810057.322010.99310068.092017.91110085.462027.036
10101.052034.12210112.282041.09410123.512043.72410134.732048.88110145.962053.227
10157.182056.64910168.572055.97110196.482058.486 10239.72060.01810250.922059.933
#Mann= 3 , 0 , 0
9749.032  0.0403       09749.032  0.0403       010250.92  0.0403       0
#XS Ineff= 2 , 0
       0                               0
Bank Sta=9749.032,10250.92
Exp/Cntr=0.3,0.1

Type RM Length L Ch R = 1 ,28546.04,249.653200,249.653200,249.653200
XS GIS Cut Line= 6
702084.125219005765728.602913032 702136.13265318765666.966763035
702180.518357314765637.170116312702304.201159884765596.209597629
702413.678738596765566.323410607702526.103481115765515.426699889
#Sta/Elev= 30
9749.1042005.5259767.059 2004.869799.3642002.382 9829.881999.0359841.0721997.374
9853.6941994.0239865.6711992.2759877.1451991.2769888.316 1989.46 9909.911989.137
9941.1971989.6149951.5981988.8239972.3991985.0329982.8211980.2859993.4481974.547
10004.121972.22210014.731973.26210025.041978.47110045.671991.06410059.752000.752
 10066.32005.28710076.61 2014.13 10097.42021.73510107.872028.38110118.342033.035
10150.38 2036.8110161.152038.55410182.682040.57610227.36 2050.9710250.942058.547
#Mann= 3 , 0 , 0
9749.104  0.0936       09749.104  0.0936       010250.94  0.0936       0
#XS Ineff= 2 , 0
       0                               0
Bank Sta=9749.104,10250.94
Exp/Cntr=0.3,0.1

Type RM Length L Ch R = 1 ,28296.38,249.653100,249.653100,249.653100
XS GIS Cut Line= 6
702149.546797842765941.834889829702250.188688844 765897.25259164
702377.480982661765834.553163797702407.187717378765819.119863987
702450.409789175765789.269051552702695.463656068765597.905958056
#Sta/Elev= 30
9749.029 1992.919798.7421992.7789831.553 1991.999842.4911990.8069864.1971990.884
9897.9161988.9939932.0341985.4189953.6631984.1979964.8131982.1879975.9621978.968
9987.1121971.7899998.2611970.35310009.471973.62910032.01  1983.510043.971985.573
10056.121984.94410142.681984.91510156.271983.84710191.431983.57110207.021984.888
10219.711983.36210245.08 1983.4510257.771984.64710270.461984.41310283.151987.277
10288.911986.99510305.161988.54210321.211992.19610371.962013.51810397.922022.857
#Mann= 3 , 0 , 0
9749.029    0.04       09749.029    0.04       010397.92    0.04       0
#XS Ineff= 2 , 0
       0                               0
Bank Sta=9749.029,10397.92
Exp/Cntr=0.3,0.1

Type RM Length L Ch R = 1 ,28046.73,244.945400,244.945400,244.945400
XS GIS Cut Line= 6
 702380.58547577766045.011197565702511.122826251766013.220766098
702538.213008342766003.626119859 702568.92427557765982.125031288
702609.349943987765884.989451401702752.755322784765674.728874728
#Sta/Elev= 30
9749.2321990.843 9774.361991.0949784.6531990.415 9815.531990.3359836.1141991.465
9856.699  1990.99883.5851988.0059898.3071984.2139930.0791984.3239958.6461980.313
9969.601 1979.919980.0991973.5489990.596 1970.4210001.081969.203 10011.71969.285
10022.311970.73410033.041973.67910104.251979.99810116.36 1979.4810128.461980.186
10140.561979.36710152.671979.72610176.881978.21710190.111978.53910207.851980.934
 10225.31979.781 10249.51980.79810273.711985.72510296.591994.30410310.35 2000.18
#Mann= 3 , 0 , 0
9749.232    0.04       09749.232    0.04       010310.35    0.04       0
#XS Ineff= 2 , 0
       0                10062.21       0
Bank Sta=9749.232,10310.35
Exp/Cntr=0.3,0.1

Type RM Length L Ch R = 1 ,27801.78,504.014000,504.014000,504.014000
XS GIS Cut Line= 6
702295.461256336766073.564773474702398.500740262766065.661473745
702453.341014973766073.169015846702571.429320308766150.936560973
702620.673369057766169.231959688702768.138868809766164.320930166
#Sta/Elev= 30
9754.4371990.9249804.1831990.6129874.3261990.7649884.3611990.3899915.1291987.662
9925.968 1987.339942.0291985.084 9960.331980.1849972.8751978.2689977.5561976.346
 9985.421971.2349994.1181967.4029997.9651966.92110023.061969.51510027.211970.543
10035.671973.50710044.551978.03110047.651979.24310059.281979.93310091.841980.859
10112.43 1980.0210132.591979.73910142.611980.27710152.611981.68710162.61 1982.15
10172.631985.51710182.651990.044 10202.71996.22910212.741998.21610256.212003.425
#Mann= 3 , 0 , 0
9754.437  0.0425       09754.437  0.0425       010256.21  0.0425       0
#XS Ineff= 2 , 0
       0                               0
Bank Sta=9754.437,10256.21
Exp/Cntr=0.3,0.1

Type RM Length L Ch R = 1 ,27297.77,445.136300,445.136300,445.136300
XS GIS Cut Line= 6
702473.136483261766395.747734204702543.360175647766432.347434786
702567.762639306766448.707188839702603.977400714766487.229745367
  702628.3953777766499.780764817702932.395750704766566.273597502
#Sta/Elev= 30
9749.2181994.2679775.6231994.1029820.8051992.769 9831.83 1991.389855.9091987.089
9869.217 1983.899881.5771982.0189884.8361981.0819894.0281980.8129924.6311978.393
9935.8751977.9069946.5571975.3269977.5291970.1589987.6841967.777 9997.841966.232
   100081965.28310018.171966.741 10038.51972.68810058.91 1973.1210079.411974.838
10110.161978.13310161.411979.57610171.661980.30210192.161982.95110202.411985.977
10212.661990.87810222.911993.84910233.161994.97210243.412003.02110250.992007.301
#Mann= 3 , 0 , 0
9749.218    0.04       09749.218    0.04       010250.99    0.04       0
#XS Ineff= 2 , 0
       0                               0
Bank Sta=9749.218,10250.99
Exp/Cntr=0.3,0.1

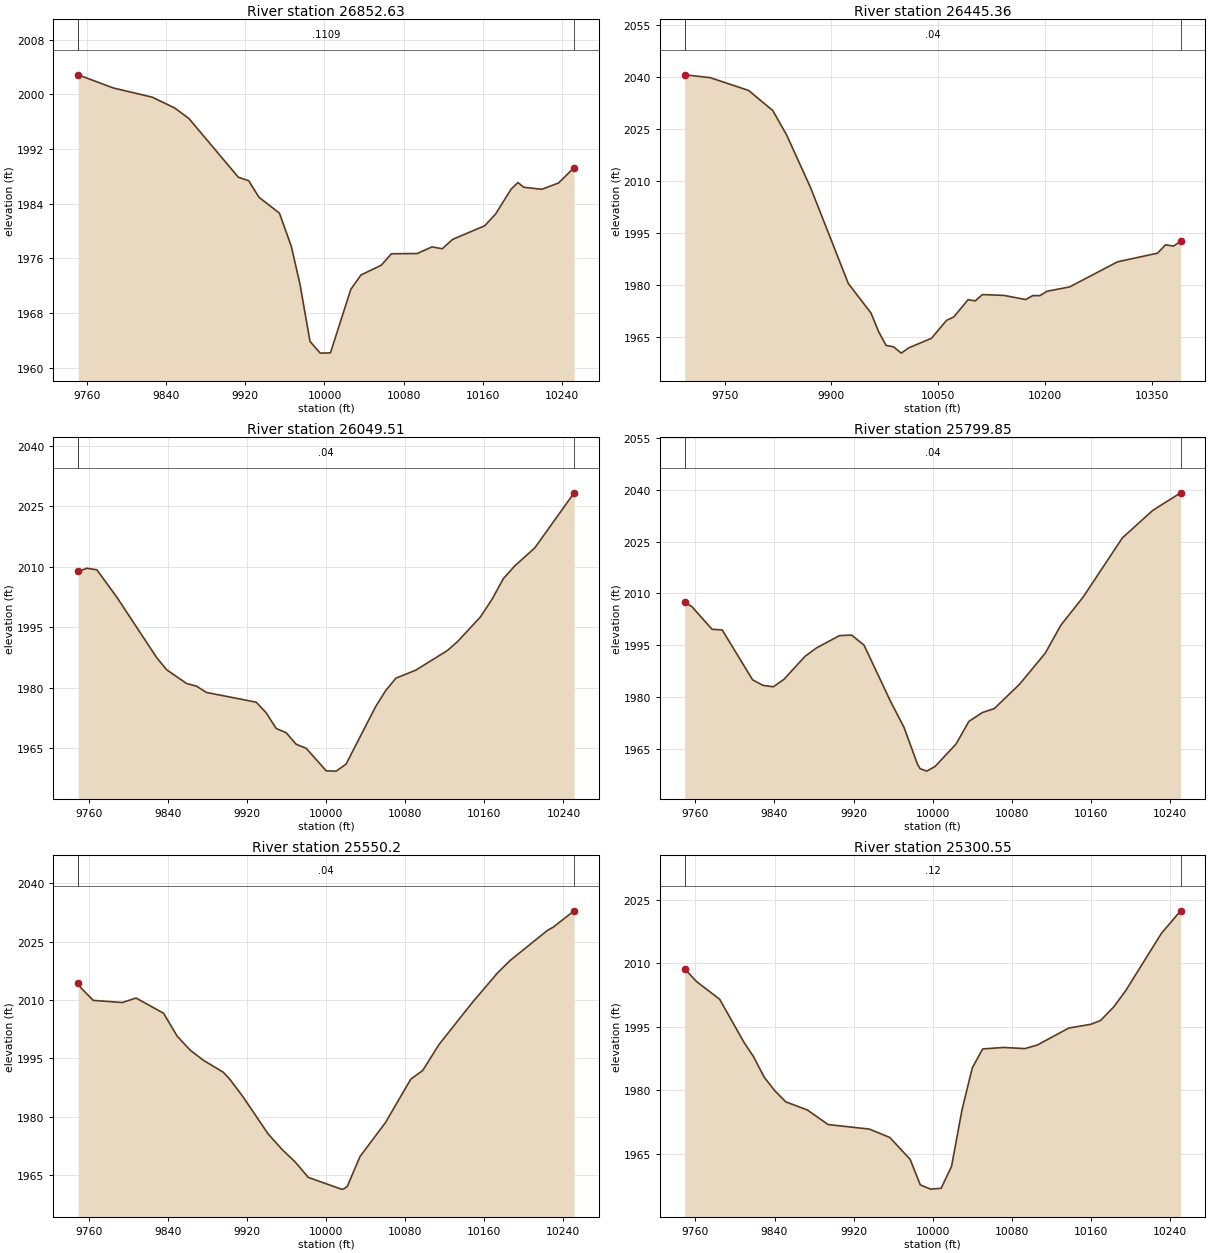
Type RM Length L Ch R = 1 ,26852.63,407.276900,407.276900,407.276900
XS GIS Cut Line= 6
702282.302341415766305.053844708702322.825621991766357.316710088
702344.086316335766397.728658612702418.344118447766667.366219181
702437.946993301766709.262410032702474.755683653766761.276174649
#Sta/Elev= 30
 9750.822002.8439786.3062000.9229825.7111999.574 9848.311998.0059862.6921996.477
9912.9061987.8589923.3541987.3549933.7561984.9289954.4131982.6189966.426 1977.77
9975.0711972.3379985.3991963.8529995.7281962.13710006.051962.17310026.651971.465
10036.911973.56810057.441974.98910067.711976.66810093.891976.70910108.791977.675
10119.251977.409 10129.71978.77510162.11 1980.7610173.15 1982.4810188.891986.125
10195.771987.08710201.711986.39710219.881986.10410236.73 1987.0110252.661989.272
#Mann= 3 , 0 , 0
 9750.82  0.1109       0 9750.82  0.1109       010252.66  0.1109       0
#XS Ineff= 2 , 0
       0                               0
Bank Sta=9750.82,10252.66
Exp/Cntr=0.3,0.1

Type RM Length L Ch R = 1 ,26445.36,395.852500,395.852500,395.852500
XS GIS Cut Line= 5
701798.328239441766475.510124728701876.453239441766623.947624728
702062.651156098766690.353874743          702225766667.428157941
702373.849072814766743.739291415
#Sta/Elev= 30
9693.7652040.6369729.5612039.8289783.5922036.1269817.4942030.3479836.9152023.318
 9870.582008.1249923.6651980.4479955.5161971.9369966.1331966.607 9976.751962.602
9987.3671962.1889997.9841960.384 10008.61961.91810040.451964.66310061.561969.829
10071.661970.79310091.861975.79610101.961975.45610112.06 1977.2710142.361977.025
10172.66 1975.8310182.751976.96710192.85 1976.9710202.951978.24210234.391979.466
10301.811986.718   103581989.20310369.241991.63410380.481991.24610390.421992.665
#Mann= 3 , 0 , 0
9693.765    0.04       09693.765    0.04       010390.42    0.04       0
#XS Ineff= 2 , 0
       0                               0
Bank Sta=9693.765,10390.42
Exp/Cntr=0.3,0.1

Type RM Length L Ch R = 1 ,26049.51,249.653200,249.653200,249.653200
XS GIS Cut Line= 6
702016.256811611766917.293790572702264.034334808766884.357447493
 702321.18415811766883.907284402702361.323992247766892.032331427
702400.260764076766907.298659329702493.661767413766968.463429437
#Sta/Elev= 30
9749.0222008.8039757.8362009.5999767.9162009.2039788.0762002.4299828.3971987.449
9838.4771984.4399858.637 1981.039868.717 1980.369878.7971978.8039929.1981976.382
9939.2781973.7339949.3581969.8629959.4611968.8169969.5911965.951 9979.721964.947
 9999.971959.36510009.991959.29310020.011961.02610050.061975.33410060.141979.259
10070.351982.32210090.75 1984.3510122.631989.21310132.73 1991.3810156.081997.549
10167.662001.86610179.232007.033 10190.82010.18710211.062014.66110250.822028.296
#Mann= 3 , 0 , 0
9749.022    0.04       09749.022    0.04       010250.82    0.04       0
#XS Ineff= 2 , 0
       0                               0
Bank Sta=9749.022,10250.82
Exp/Cntr=0.3,0.1

Type RM Length L Ch R = 1 ,25799.85,249.653100,249.653100,249.653100
XS GIS Cut Line= 6
701877.989064793766941.539168203701984.259196196766969.743905521
702015.371297102766985.248878723702042.503662131767004.540803307
702089.493018034767051.928856037 702253.45522899767249.750553395
#Sta/Elev= 30
9749.1152007.4049756.302 2006.249776.8051999.6589787.0561999.4749817.9311985.033
9828.4361983.4569838.9411983.0599849.4451985.1759870.9561991.8459882.345 1994.24
9905.7481997.8319918.0181997.9849930.6181995.0699957.434 1978.859971.0751971.333
9984.6291960.7469987.3661959.4139994.0211958.69910002.561960.05510023.831966.567
10036.691973.046 10050.31975.604 10062.41976.75510088.111983.81710113.951992.736
10129.86 2000.8610152.39 2008.9810192.052026.042 10222.72033.96810250.992039.058
#Mann= 3 , 0 , 0
9749.115    0.04       09749.115    0.04       010250.99    0.04       0
#XS Ineff= 2 , 0
       0                               0
Bank Sta=9749.115,10250.99
Exp/Cntr=0.3,0.1

Type RM Length L Ch R = 1 , 25550.2,249.653100,249.653100,249.653100
XS GIS Cut Line= 6
701733.192043844767034.654431901 701766.27235381767065.390551147
 701801.72809092767101.960300821701913.480564055767230.195508007
701952.619109135767278.440607546702058.062845868767416.426054064
#Sta/Elev= 30
9749.0162014.3529751.4842013.1949764.215 2009.889793.5972009.3389807.5562010.489
9835.4122006.5829849.1422000.6879862.415 1997.079875.6891994.4789895.7051991.415
9902.2351989.6699915.509 1985.199941.3271975.5069955.3291971.5389968.602 1968.32
9981.8761964.344 10015.2 1961.3210017.62 1961.3310021.391962.03110034.271969.721
10060.021978.43910085.581989.60410097.721991.85610114.191998.52810148.512009.521
10173.682017.02510186.272020.16210224.022027.90510229.482028.66710250.992032.926
#Mann= 3 , 0 , 0
9749.016    0.04       09749.016    0.04       010250.99    0.04       0
#XS Ineff= 2 , 0
       0                               0
Bank Sta=9749.016,10250.99
Exp/Cntr=0.3,0.1

Type RM Length L Ch R = 1 ,25300.55,249.653200,249.653200,249.653200
XS GIS Cut Line= 6
701594.464003609767104.968749407701651.324788582767214.928536195
701682.977532015767327.579650237701721.267216072767436.802196354
701750.874996403767493.618003048701796.236149899767560.548577174
#Sta/Elev= 30
9749.0642008.7099760.9732005.7429784.4412001.5439808.9551991.4059818.5811988.036
9829.5011983.1419840.4221979.8819851.3431977.3029873.1811975.3819894.2091971.939
9935.9571970.8669956.5831968.8999977.2091963.7229987.5221957.6819998.0621956.683
10008.631956.88510019.131962.05710029.641975.33610040.141985.35610050.651989.799
10071.791990.15410093.291989.87710105.971990.73110137.771994.73410160.321995.634
10170.041996.54310183.511999.79710195.342003.55910231.582017.13110250.932022.425
#Mann= 3 , 0 , 0
9749.064    0.12       09749.064    0.12       010250.93    0.12       0
#XS Ineff= 2 , 0
       0                               0
Bank Sta=9749.064,10250.93
Exp/Cntr=0.3,0.1

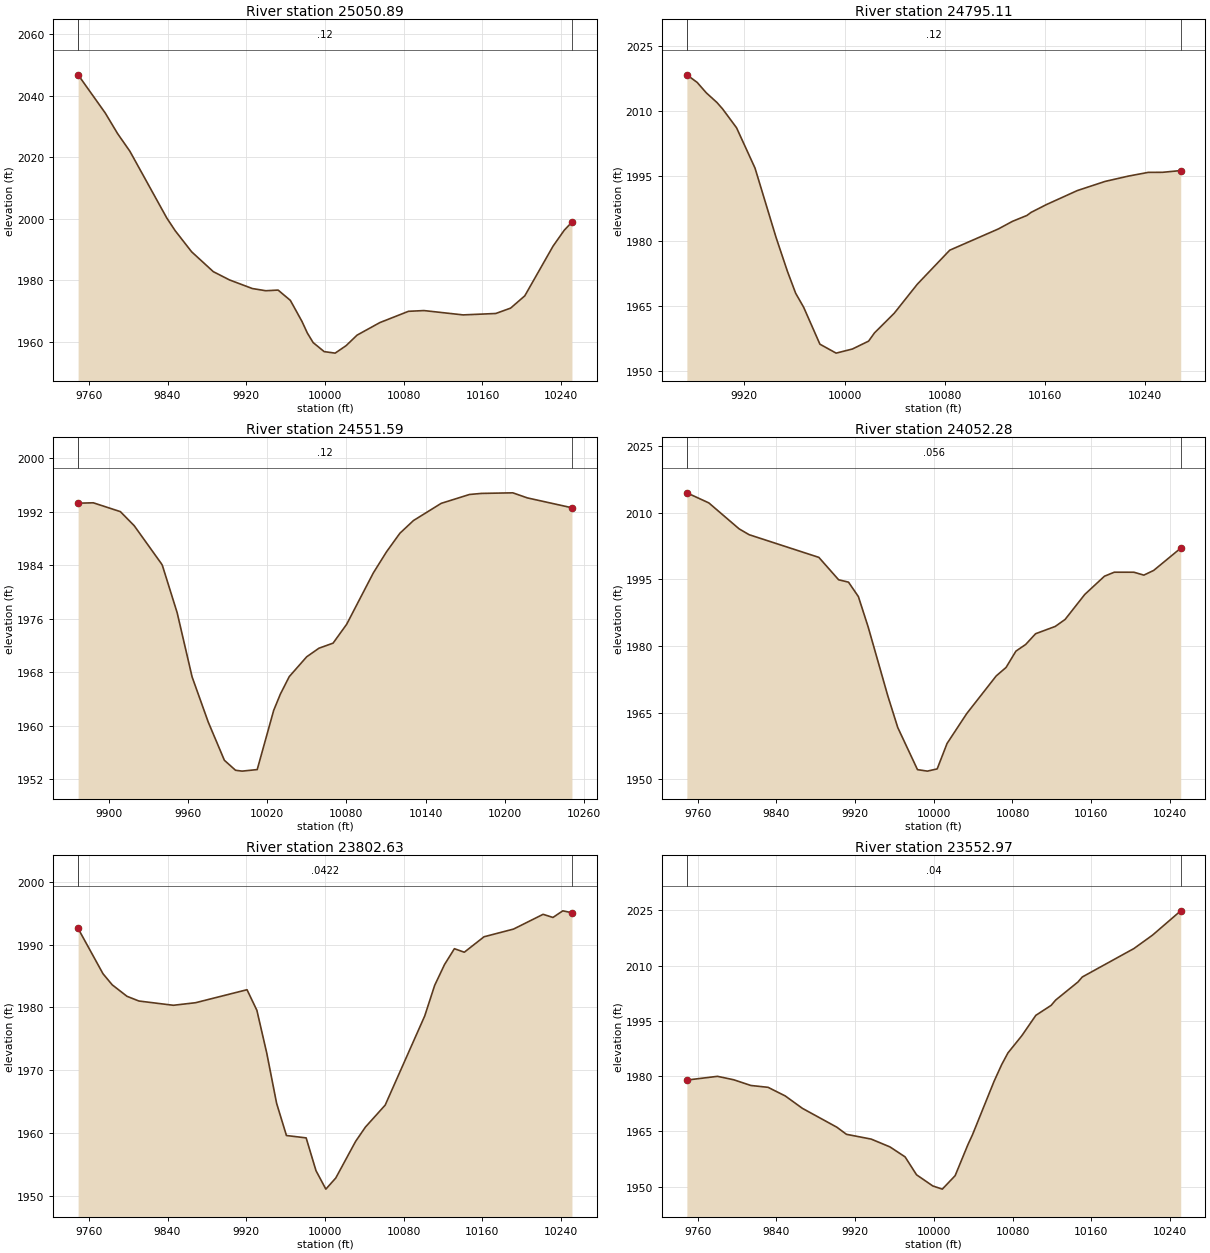
Type RM Length L Ch R = 1 ,25050.89,255.779100,255.779100,255.779100
XS GIS Cut Line= 6
701315.811617541767262.886961817701398.238582744767372.765513022
701430.120153052767407.726849538701460.243921324767430.098380432
701561.875010878767486.624556837 701678.31767021767600.635326714
#Sta/Elev= 30
9749.1362046.849 9776.782034.4049789.2812027.7249801.7822021.9779839.2852000.262
 9847.771996.1629864.4341989.3129886.4951982.8419903.0531980.1399926.2121977.344
9939.8891976.6329952.3451976.8469964.8011973.4969976.6841966.6059982.0271962.899
9987.9361959.7749999.183 1956.8310010.291956.34310021.411958.76310032.531962.182
10055.751966.27710084.841969.94510100.561970.18110140.281968.77410173.511969.232
 10188.61970.98310202.98 1974.9710231.751991.15510243.071996.30610250.911998.966
#Mann= 3 , 0 , 0
9749.136    0.12       09749.136    0.12       010250.91    0.12       0
#XS Ineff= 2 , 0
       0                               0
Bank Sta=9749.136,10250.91
Exp/Cntr=0.3,0.1

Type RM Length L Ch R = 1 ,24795.11,243.527200,243.527200,243.527200
XS GIS Cut Line= 4
701209.786572754767413.010124728701382.355476933 767622.58557165
701403.895532798767638.359222418701487.545858242767685.606063726
#Sta/Elev= 30
9874.1032018.4269882.3052016.6789889.6342014.2619898.0362012.0619902.5882010.568
9913.7682006.1999928.4961996.9059945.2321980.9559954.4041973.0429960.9631968.009
9967.3581964.7629980.3111956.2529993.2651954.19110006.221955.13810019.171956.961
10023.891958.86710039.621963.39310058.031970.08810083.941977.947 10122.8 1982.86
10134.011984.60710145.581985.97110148.861986.67110161.261988.49410185.79 1991.71
   102081993.82610226.451995.04410242.461995.91210253.941995.92610268.351996.329
#Mann= 3 , 0 , 0
9874.103    0.12       09874.103    0.12       010268.35    0.12       0
#XS Ineff= 2 , 0
       0                               0
Bank Sta=9874.103,10268.35
Exp/Cntr=0.3,0.1

Type RM Length L Ch R = 1 ,24551.59,499.306200,499.306200,499.306200
XS GIS Cut Line= 6
701173.768681751767761.694583977701234.243416737767744.701615433
701322.557640752767686.758498801701362.463098699767673.534543584
701414.715216097767680.062413805701515.463871315767724.180164246
#Sta/Elev= 30
 9876.771993.2859888.2751993.342 9908.771992.0249919.2481989.9239939.7141984.281
9940.5631984.001 9951.79 1976.919963.0911967.3239975.3281960.5649987.5661954.845
9995.9951953.355   100011953.22610012.421953.45810024.891962.30410029.941964.733
10036.671967.35210049.891970.31810059.181971.60310069.881972.36110080.141975.172
10100.34 1982.8510110.341986.01210120.461988.78610130.741990.68610151.761993.259
10173.181994.58610182.351994.74710205.991994.83410217.061994.074 10250.8  1992.6
#Mann= 3 , 0 , 0
 9876.77    0.12       0 9876.77    0.12       0 10250.8    0.12       0
#XS Ineff= 2 , 0
       0                               0
Bank Sta=9876.77,10250.8
Exp/Cntr=0.3,0.1

Type RM Length L Ch R = 1 ,24052.28,249.653200,249.653200,249.653200
XS GIS Cut Line= 6
700993.192787573768153.661881504701072.016754707768170.889542344
701161.669097012768181.514788223701245.630394199768185.572713194
701409.210115016768187.090337678701492.435318618768190.810872767
#Sta/Elev= 30
 9749.042014.4459771.3622012.178 9802.072006.3559812.3062005.0329883.1951999.929
9903.2861994.8929913.3321994.3589923.3661991.1169933.378 1984.239953.4031968.693
9963.4151961.661 9983.441952.2059993.4521951.87110003.461952.37110013.461958.079
10033.461964.80410063.461973.27910073.461975.18210083.461978.84610093.46 1980.36
10103.471982.76310123.471984.40710133.471985.97510153.471991.59710173.471995.697
10183.481996.598 10203.5 1996.5910213.51 1995.9410223.521996.99910250.992002.004
#Mann= 3 , 0 , 0
 9749.04   0.056       0 9749.04   0.056       010250.99   0.056       0
#XS Ineff= 2 , 0
       0                               0
Bank Sta=9749.04,10250.99
Exp/Cntr=0.3,0.1

Type RM Length L Ch R = 1 ,23802.63,249.653100,249.653100,249.653100
XS GIS Cut Line= 6
701034.181361468768355.268393014701126.391399355768415.247868986
701184.283019318768433.307121253701256.513454091768433.528818095
701420.651051386768417.633363005701514.305263695768416.980592008
#Sta/Elev= 30
9749.1211992.5559774.443 1985.349783.7821983.579 9798.771981.7539810.9331980.999
9845.9291980.3219868.4441980.7289920.771  1982.89930.7911979.518 9940.811972.713
9950.8291964.7049960.8361959.5689980.851 1959.199990.8591953.96710000.881951.026
10010.931952.79210031.03 1958.6110041.071960.91110061.171964.41510101.361978.624
10111.411983.47610121.461986.80910131.511989.33710141.561988.77410161.631991.237
10191.651992.46610221.661994.81510231.661994.31610241.661995.37110250.961995.066
#Mann= 3 , 0 , 0
9749.121  0.0422       09749.121  0.0422       010250.96  0.0422       0
#XS Ineff= 2 , 0
       0                               0
Bank Sta=9749.121,10250.96
Exp/Cntr=0.3,0.1

Type RM Length L Ch R = 1 ,23552.97,371.411500,371.411500,371.411500
XS GIS Cut Line= 6
 701126.18840601768463.180044619701236.906538397768618.347866059
701264.877290354768664.921399688701305.597695461 768711.08749875
701372.392339553768772.415699419701459.285969211  768830.3203971
#Sta/Elev= 30
9749.0651978.9319780.1781979.9449796.7171979.0069814.099 1977.469831.568 1976.96
9849.0371974.6219866.5061971.2449901.4441966.1349911.2381964.1999936.3831962.901
9955.4331960.7829970.8031958.0779982.4671953.208    99991950.17610008.631949.316
10021.671952.96610034.711961.42710039.181963.99410061.221978.58210069.011983.149
10075.34  1986.310089.461990.97910103.671996.50310119.281999.22510123.812000.651
10146.462005.55410150.89 2006.9210203.362014.64310222.25 2018.2810250.932024.885
#Mann= 3 , 0 , 0
9749.065    0.04       09749.065    0.04       010250.93    0.04       0
#XS Ineff= 2 , 0
       0                               0
Bank Sta=9749.065,10250.93
Exp/Cntr=0.3,0.1

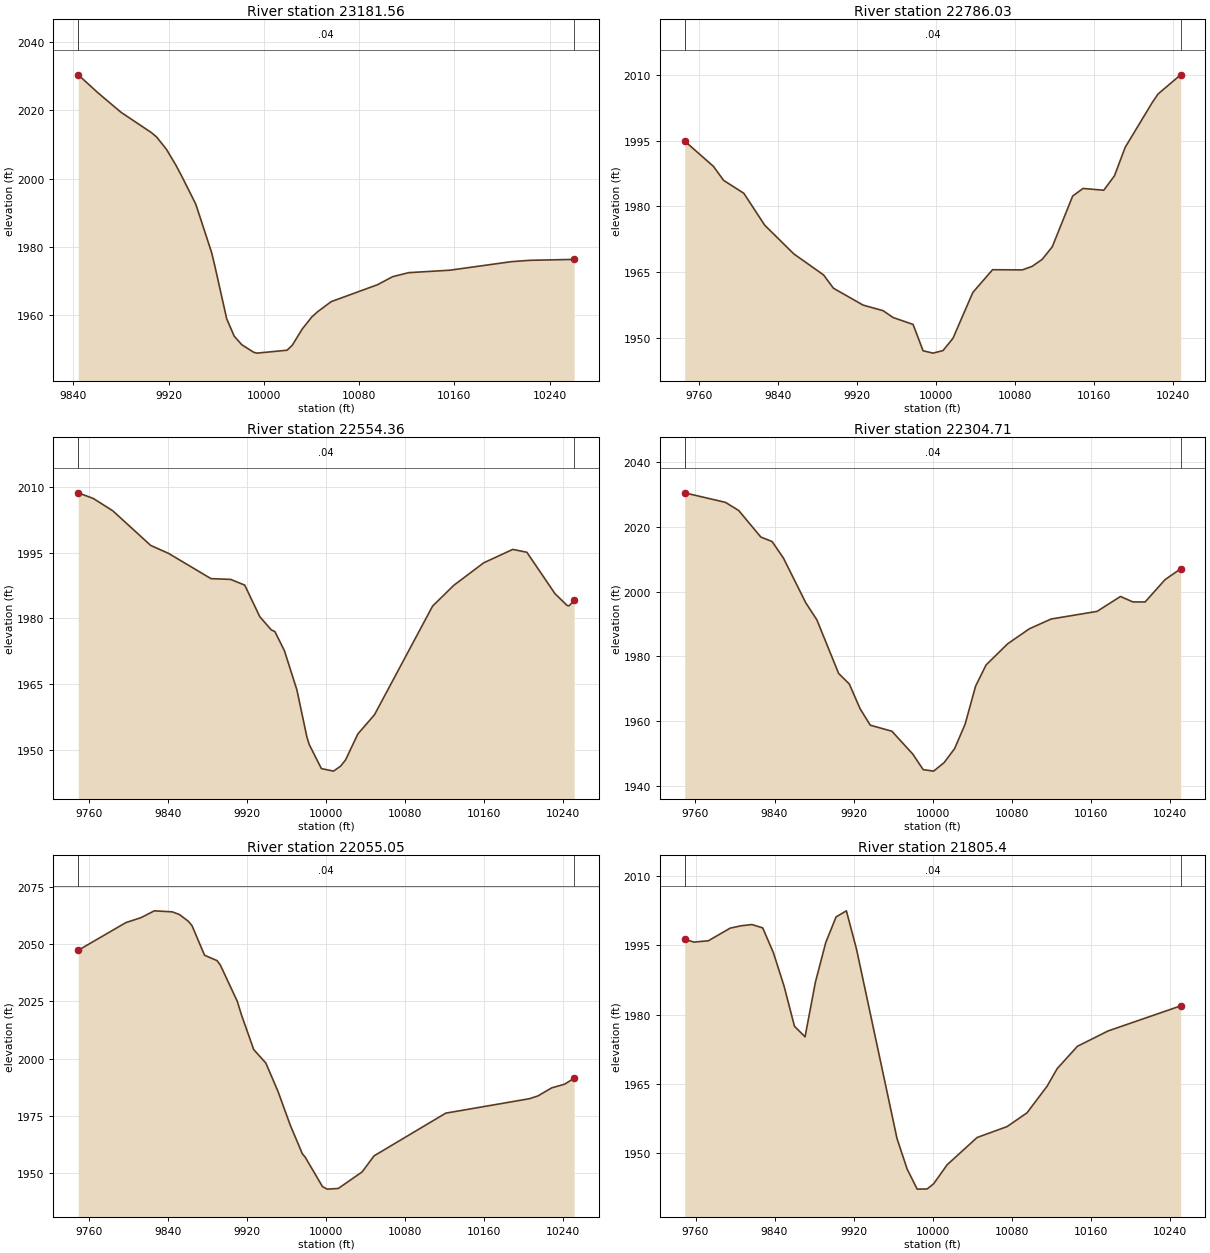
Type RM Length L Ch R = 1 ,23181.56,395.533200,395.533200,395.533200
XS GIS Cut Line= 5
700816.557406068768514.572624728 701039.22415901768687.771064476
701060.486286558768699.450154981701084.090139452 768716.93179095
 701145.73377268768769.027333119
#Sta/Elev= 30
 9844.182030.4179861.1642025.0319880.2142019.4289905.552 2013.529910.0262012.215
9918.2212008.6439926.3142003.911 9930.892000.8979942.6011992.7849943.5591991.875
9956.2281978.3689958.8891974.4949968.8971958.9719975.1761953.9129981.5661951.396
9991.4631949.2129994.2351948.94810019.57  1949.810024.041951.31210032.241955.988
10040.331959.53410044.911960.98510056.611964.02110095.591968.98910108.261971.337
10121.761972.50610156.15 1973.22 10207.91975.72310223.391976.11610260.621976.388
#Mann= 3 , 0 , 0
 9844.18    0.04       0 9844.18    0.04       010260.62    0.04       0
#XS Ineff= 2 , 0
       0                               0
Bank Sta=9844.18,10260.62
Exp/Cntr=0.3,0.1

Type RM Length L Ch R = 1 ,22786.03,231.667900,231.667900,231.667900
XS GIS Cut Line= 6
700756.739496908768957.478413514700899.298711806768981.361178642
701045.340741971768965.528091892701104.988909466768966.946753171
701173.639262622768984.498725569 701245.43157523769017.921880461
#Sta/Elev= 30
9745.8161994.9019774.9241989.1229785.2241985.9229805.6591982.9849826.8341975.685
9856.2991969.137 9886.371964.3449896.3851961.303 9926.411957.4539946.5981956.181
9956.7141954.6229976.9471953.0479987.0631947.0339997.1521946.49510007.211947.076
10017.27 1949.8610037.381960.33310057.391965.53510087.451965.49110097.481966.301
10107.651967.90510117.821970.77910138.451982.34810148.921984.07910169.921983.675
10180.751986.97310191.581993.46510218.752003.60110224.842005.63710247.682010.012
#Mann= 3 , 0 , 0
9745.816    0.04       09745.816    0.04       010247.68    0.04       0
#XS Ineff= 2 , 0
       0                               0
Bank Sta=9745.816,10247.68
Exp/Cntr=0.3,0.1

Type RM Length L Ch R = 1 ,22554.36,249.653100,249.653100,249.653100
XS GIS Cut Line= 6
700688.379312636768967.209746914700770.214737763769017.600780914
700821.442265252769060.664378972700854.268275207 769098.36226492
700947.300635708769222.598218475701038.545240714 769320.04376112
#Sta/Elev= 30
9749.065 2008.779764.3682007.4749784.0132004.6669822.4571996.7229840.5061994.905
 9883.451989.1239903.3841988.9519917.6071987.6369932.8351980.4149944.4581977.387
9948.0631977.0229957.7181972.6519970.3931963.6489980.382 1952.999982.773 1951.19
9995.1521945.63710007.411945.05510014.631946.19510019.721947.65210032.031953.552
10048.921957.97110107.741982.84710129.071987.57510159.311992.72810188.851995.818
10203.121995.16210231.65 1985.66 10243.91982.97310245.911982.90910250.971984.136
#Mann= 3 , 0 , 0
9749.065    0.04       09749.065    0.04       010250.97    0.04       0
#XS Ineff= 2 , 0
       0                               0
Bank Sta=9749.065,10250.97
Exp/Cntr=0.3,0.1

Type RM Length L Ch R = 1 ,22304.71,249.653100,249.653100,249.653100
XS GIS Cut Line= 6
700573.870747536769061.099825869700610.498405694769113.992471016
700648.537458457769184.905838704700706.052139331769340.337698915
700734.177147924769401.081507568700805.183322698769502.774053416
#Sta/Elev= 30
9749.0612030.5619790.2962027.6159803.7392025.1039826.0672016.9129837.5772015.497
9849.087 2010.359871.7041996.5339882.8561991.3019904.8331974.757 9915.661971.495
9926.4871963.9039936.8491958.7639958.7461956.8939979.8661949.8389990.4261945.029
10000.971944.56410011.591947.185 10022.21951.51410032.811959.03510043.431970.803
10054.04 1977.3710075.86  1983.9 10097.91988.55510119.941991.57510166.361993.925
10190.091998.53610202.551996.851   102151996.84110235.132003.72410250.922007.071
#Mann= 3 , 0 , 0
9749.061    0.04       09749.061    0.04       010250.92    0.04       0
#XS Ineff= 2 , 0
       0                               0
Bank Sta=9749.061,10250.92
Exp/Cntr=0.3,0.1

Type RM Length L Ch R = 1 ,22055.05,249.653200,249.653200,249.653200
XS GIS Cut Line= 6
700293.056740457769137.001109168700338.942490148 769188.89680477
700385.516798187769248.251439322700535.291049674769462.125347035
700568.881695198769500.401156925700601.344569552769531.782766625
#Sta/Elev= 30
9749.0222047.3959797.2462059.5119812.3432061.6319826.0532064.6649844.3072064.211
9851.4752063.0429860.5062060.0879864.1862058.1979876.897 2045.249889.608 2042.87
9892.9042040.9149910.027 2025.079914.3432019.0169926.6432003.9849938.9441998.053
9951.2441985.6399963.5451971.0059975.8451958.391 9978.721956.9199996.2361944.016
   100011942.89710012.231943.18510036.371950.42710048.441957.44710120.991976.136
10205.811982.46810214.321983.68110228.231987.19710241.211988.79610250.971991.408
#Mann= 3 , 0 , 0
9749.022    0.04       09749.022    0.04       010250.97    0.04       0
#XS Ineff= 2 , 0
       0                               0
Bank Sta=9749.022,10250.97
Exp/Cntr=0.3,0.1

Type RM Length L Ch R = 1 , 21805.4,249.653100,249.653100,249.653100
XS GIS Cut Line= 6
700083.709853875769460.754967652 700159.25857469769496.567900614
700231.763705365769521.485420001700296.877568553769536.152962704
700459.576496265769561.958359333700564.098716525769596.088626202
#Sta/Elev= 30
9749.0451996.3279758.3671995.7039772.9591995.9859795.1231998.7259806.0861999.227
9817.0481999.499 9828.011998.7779838.8141993.4229849.5021986.2819860.189 1977.49
9870.8761975.2219881.3551987.0449891.8261995.6129902.2972001.1569912.6972002.465
9922.9481994.186 9963.951953.217  9974.21946.6189984.3551942.2799994.4871942.318
   100011943.435 10014.7 1947.5510044.991953.44610075.281955.79610095.531958.781
10115.891964.55810126.061968.34810146.511973.16510177.591976.49110250.961981.905
#Mann= 3 , 0 , 0
9749.045    0.04       09749.045    0.04       010250.96    0.04       0
#XS Ineff= 2 , 0
       0                               0
Bank Sta=9749.045,10250.96
Exp/Cntr=0.3,0.1

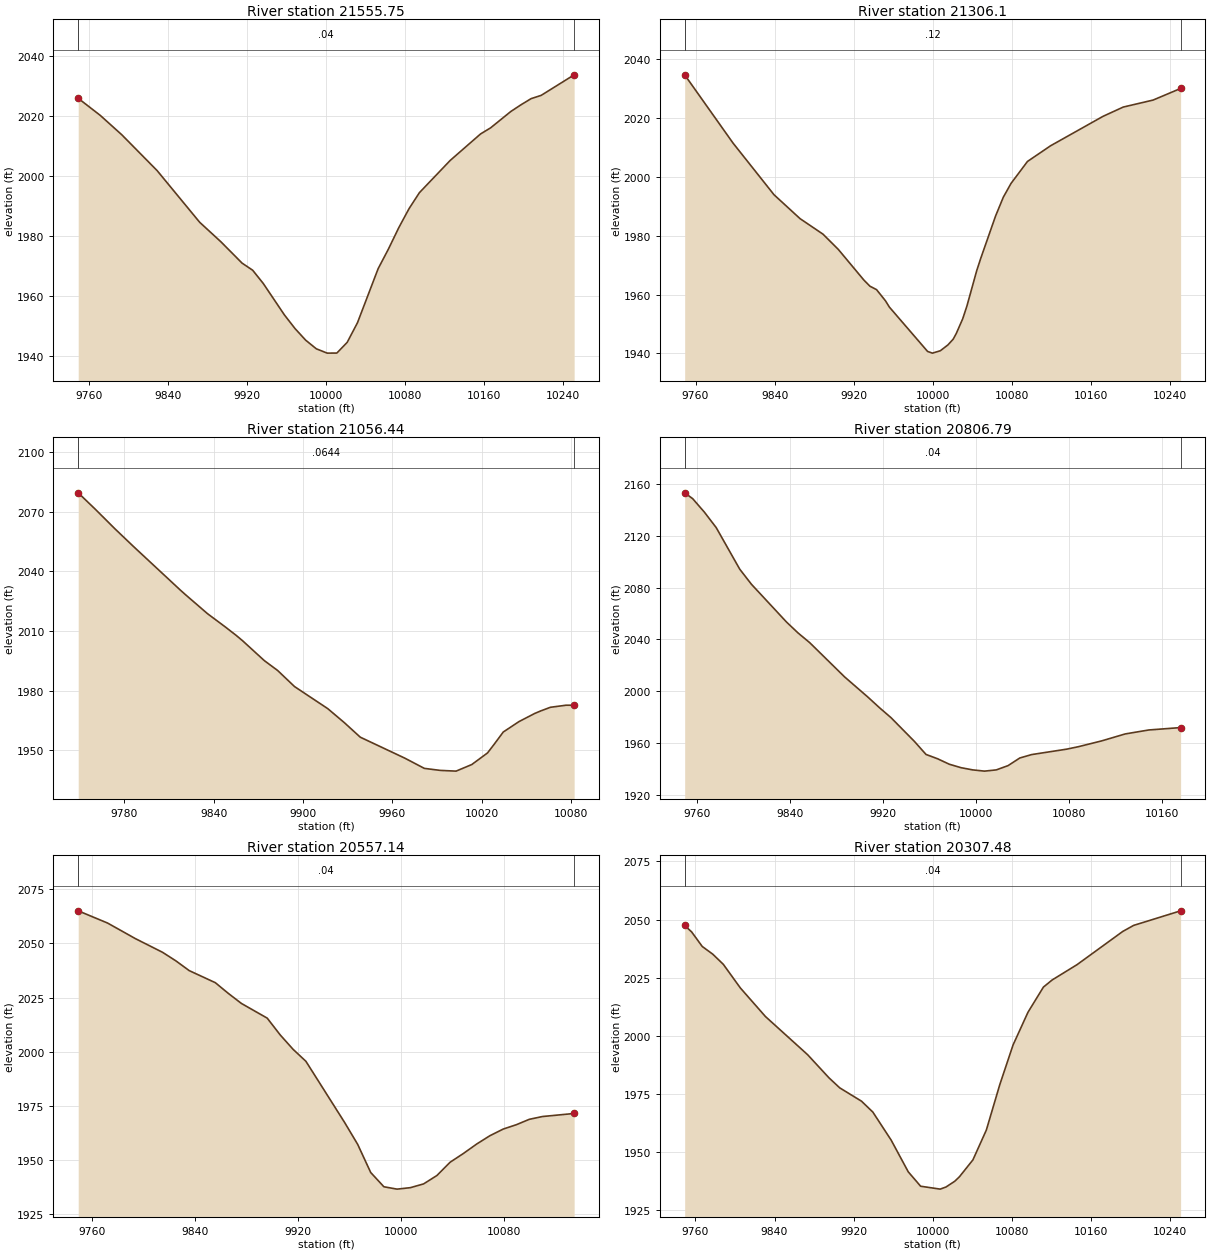
Type RM Length L Ch R = 1 ,21555.75,249.653200,249.653200,249.653200
XS GIS Cut Line= 6
700103.246708372769684.765065995  700142.2607913769704.881463743
700182.541231588769723.083120334700327.249213862769779.293814253
700444.183233329769814.047168529700577.563605368769843.256765981
#Sta/Elev= 30
9749.0422025.8089771.3752020.1219793.2242013.6499828.8632001.765 9871.961984.559
9893.4161978.0719914.8721970.965  9925.61968.5949936.3281964.1839957.7841953.696
9968.5121949.162 9979.241945.3199989.9671942.457   100011941.01110010.791941.034
10021.241944.59210031.681951.14310052.571969.11310063.021975.66810073.461982.764
10083.911989.12610094.351994.41110125.462005.12410156.172013.93710166.412015.982
10186.882021.42910197.12 2023.6510207.36 2025.6910217.592026.79310250.932033.622
#Mann= 3 , 0 , 0
9749.042    0.04       09749.042    0.04       010250.93    0.04       0
#XS Ineff= 2 , 0
       0                               0
Bank Sta=9749.042,10250.93
Exp/Cntr=0.3,0.1

Type RM Length L Ch R = 1 , 21306.1,249.653100,249.653100,249.653100
XS GIS Cut Line= 6
700021.609923301769788.838589852700092.653913718769865.635805621
700200.436667147769997.377594592700241.517121839770035.447341576
 700307.92230937770069.322464523700402.784871022770082.881758555
#Sta/Elev= 30
9749.0172034.638    97982011.4379839.4091993.9179865.7431985.8029888.9981980.522
9904.4661975.3549930.2821964.9659936.445 1962.869943.189 1961.689952.2611957.865
9956.0971955.778 9994.821940.6959999.7241940.12210007.761940.93910015.381942.908
10020.781944.88610023.871946.80810030.371951.78510034.591956.095 10044.61968.204
10048.641972.34810063.591986.66810071.481993.10110079.251997.75610095.882005.211
10119.262010.54110172.342020.53910192.81 2023.69   102232026.06410250.862030.009
#Mann= 3 , 0 , 0
9749.017    0.12       09749.017    0.12       010250.86    0.12       0
#XS Ineff= 2 , 0
       0                               0
Bank Sta=9749.017,10250.86
Exp/Cntr=0.3,0.1

Type RM Length L Ch R = 1 ,21056.44,249.653100,249.653100,249.653100
XS GIS Cut Line= 6
699842.554933339769875.876480877699887.296010122 769932.88711998
699921.026425929769987.172464997699937.474789322770019.991099961
699952.002833445770054.583801439 699992.23412501770170.081282866
#Sta/Elev= 30
9749.0792079.4549760.677 2071.119773.3892061.6099786.1012052.5229817.8312030.408
 9821.552027.9339835.8112018.7169847.5842012.1399855.0952007.7789859.3572005.109
9874.0421995.0549882.9031990.1399894.3291982.0039916.5881970.9249927.6041963.952
 9938.451956.5569968.3731946.0029981.4441940.8729992.0991939.86110002.731939.492
10013.291942.80510023.851948.64410028.281952.96710034.411959.15910044.961964.397
10055.521968.48910059.451969.73510066.081971.60210076.641972.645   100821972.619
#Mann= 3 , 0 , 0
9749.079  0.0644       09749.079  0.0644       0   10082  0.0644       0
#XS Ineff= 2 , 0
       0                               0
Bank Sta=9749.079,10082
Exp/Cntr=0.3,0.1

Type RM Length L Ch R = 1 ,20806.79,249.653200,249.653200,249.653200
XS GIS Cut Line= 6
699548.212738646770225.035225788699597.665293634770233.216260162
699641.871121501770237.629528952699728.542347256770238.332566124
699913.471674521770216.391701024699971.607695951770203.909240839
#Sta/Elev= 30
9749.0362152.9589755.916 2148.479766.0522138.0249776.1882126.159 9796.462094.115
9806.5322082.4959836.6812053.4449846.7182044.9469856.7252037.4989886.7472011.137
9906.7521995.6199916.7551987.4279926.7571979.6849946.817 1961.489956.8521951.392
9966.8871948.0289976.9431943.8339987.0341941.1659997.124 1939.4710007.241938.522
10017.371939.46610027.491942.74710037.621948.62610047.741951.25810077.971955.447
10088.021957.32810108.111961.80910128.351967.16210148.691970.22610176.121972.075
#Mann= 3 , 0 , 0
9749.036    0.04       09749.036    0.04       010176.12    0.04       0
#XS Ineff= 2 , 0
       0                               0
Bank Sta=9749.036,10176.12
Exp/Cntr=0.3,0.1

Type RM Length L Ch R = 1 ,20557.14,249.653100,249.653100,249.653100
XS GIS Cut Line= 6
699957.643953939770576.087384801699986.060323508770496.273686318
699994.977742329770416.615087396699989.411064367770354.942067177
699959.256035204770217.977427102699976.120915956770213.123731687
#Sta/Elev= 30
9749.1312065.0289771.9552059.3799793.6022052.1719814.5872045.8899824.9592041.934
9835.3012037.4349855.5812031.8589865.721 2026.89 9875.852022.268 9895.882015.484
9905.895 2007.799915.9092001.118 9925.921995.5519956.0341967.2589966.1251957.196
9976.2161944.2399986.4441937.6549996.6721936.56410006.981937.23710017.281938.977
10027.571942.84110037.871948.98110048.171953.02110058.471957.37210068.771961.229
10079.061964.28710089.211966.28410099.351968.78610109.481970.06910134.15 1971.49
#Mann= 3 , 0 , 0
9749.131    0.04       09749.131    0.04       010134.15    0.04       0
#XS Ineff= 2 , 0
       0                               0
Bank Sta=9749.131,10134.15
Exp/Cntr=0.3,0.1

Type RM Length L Ch R = 1 ,20307.48,249.653200,249.653200,249.653200
XS GIS Cut Line= 6
 700115.47620844770541.650772129700176.526653619770381.943872109
700225.012729888770309.314382438700278.194037871770251.642220121
700318.073597456770218.414948084700419.121820778770168.849097724
#Sta/Elev= 30
9749.0652047.4499756.1552044.6469766.8142038.4239777.4742035.0939788.1342030.741
9805.4352020.5429830.7732008.2749873.4351991.8559895.0981981.882 9905.931977.583
9928.021 1971.839939.4691967.1459958.021 1955.079975.2781941.452 9987.82 1935.25
 10007.61934.00310013.491934.91910022.35  1937.410027.09 1939.3310040.691946.568
 10054.31959.418 10067.91978.95710081.36 1996.0610096.452010.11910112.072020.944
10120.962024.01510146.082030.58810192.28 2044.8610203.282047.46610250.872053.745
#Mann= 3 , 0 , 0
9749.065    0.04       09749.065    0.04       010250.87    0.04       0
#XS Ineff= 2 , 0
       0                               0
Bank Sta=9749.065,10250.87
Exp/Cntr=0.3,0.1