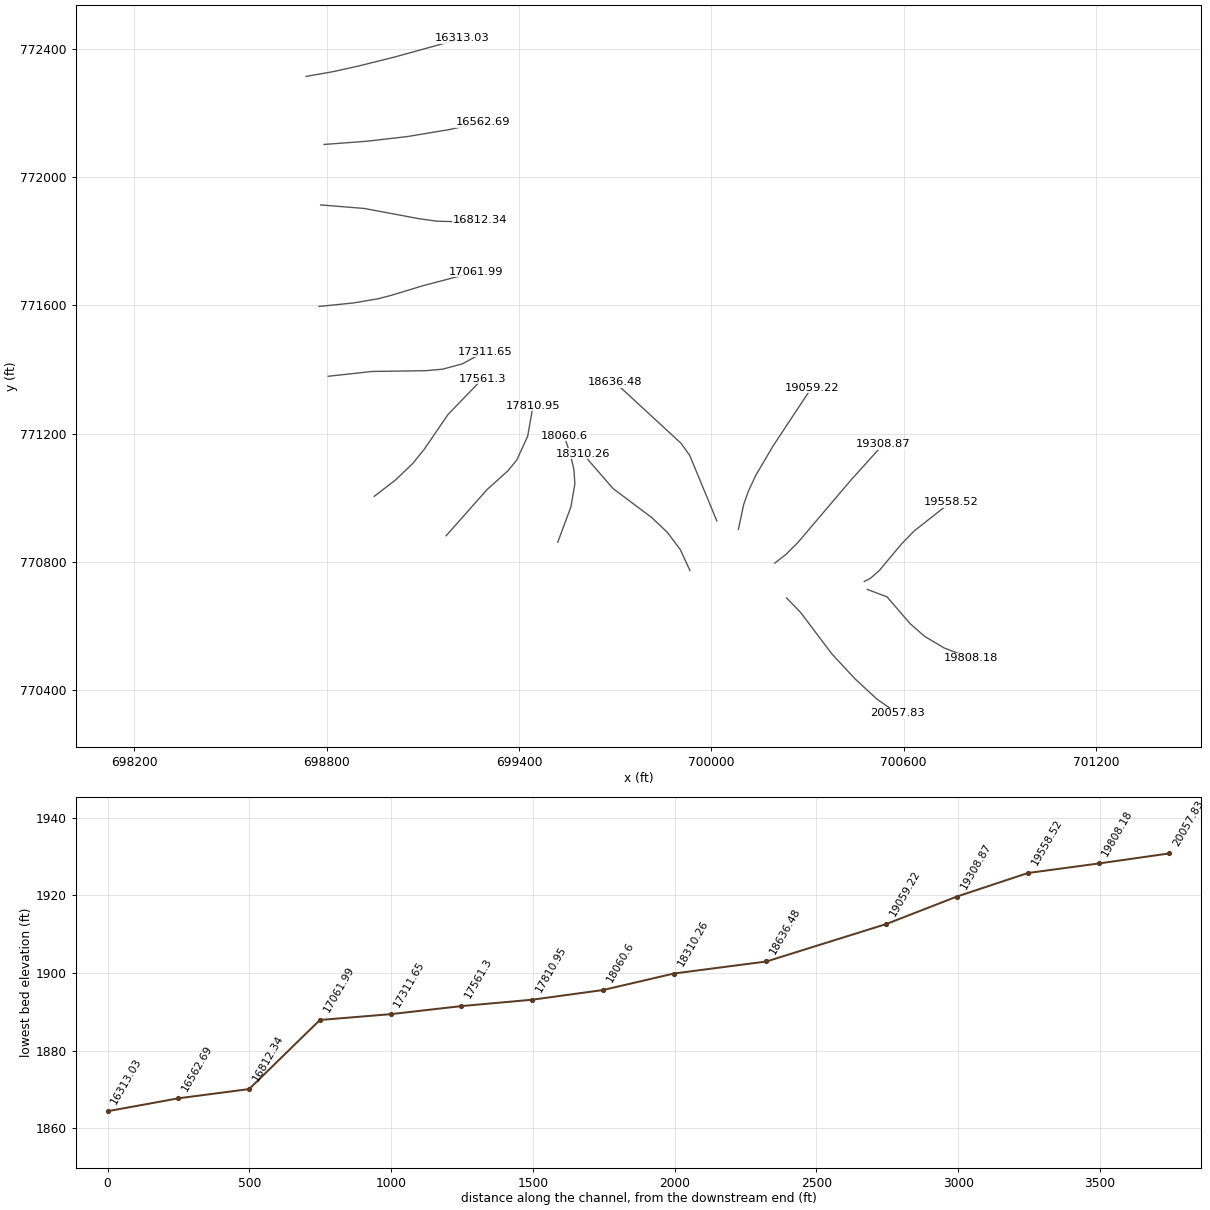
HEC-RAS study 14441_ras.prj: 14441

--- 14441_ras.g01 (geometry) --- (continued)

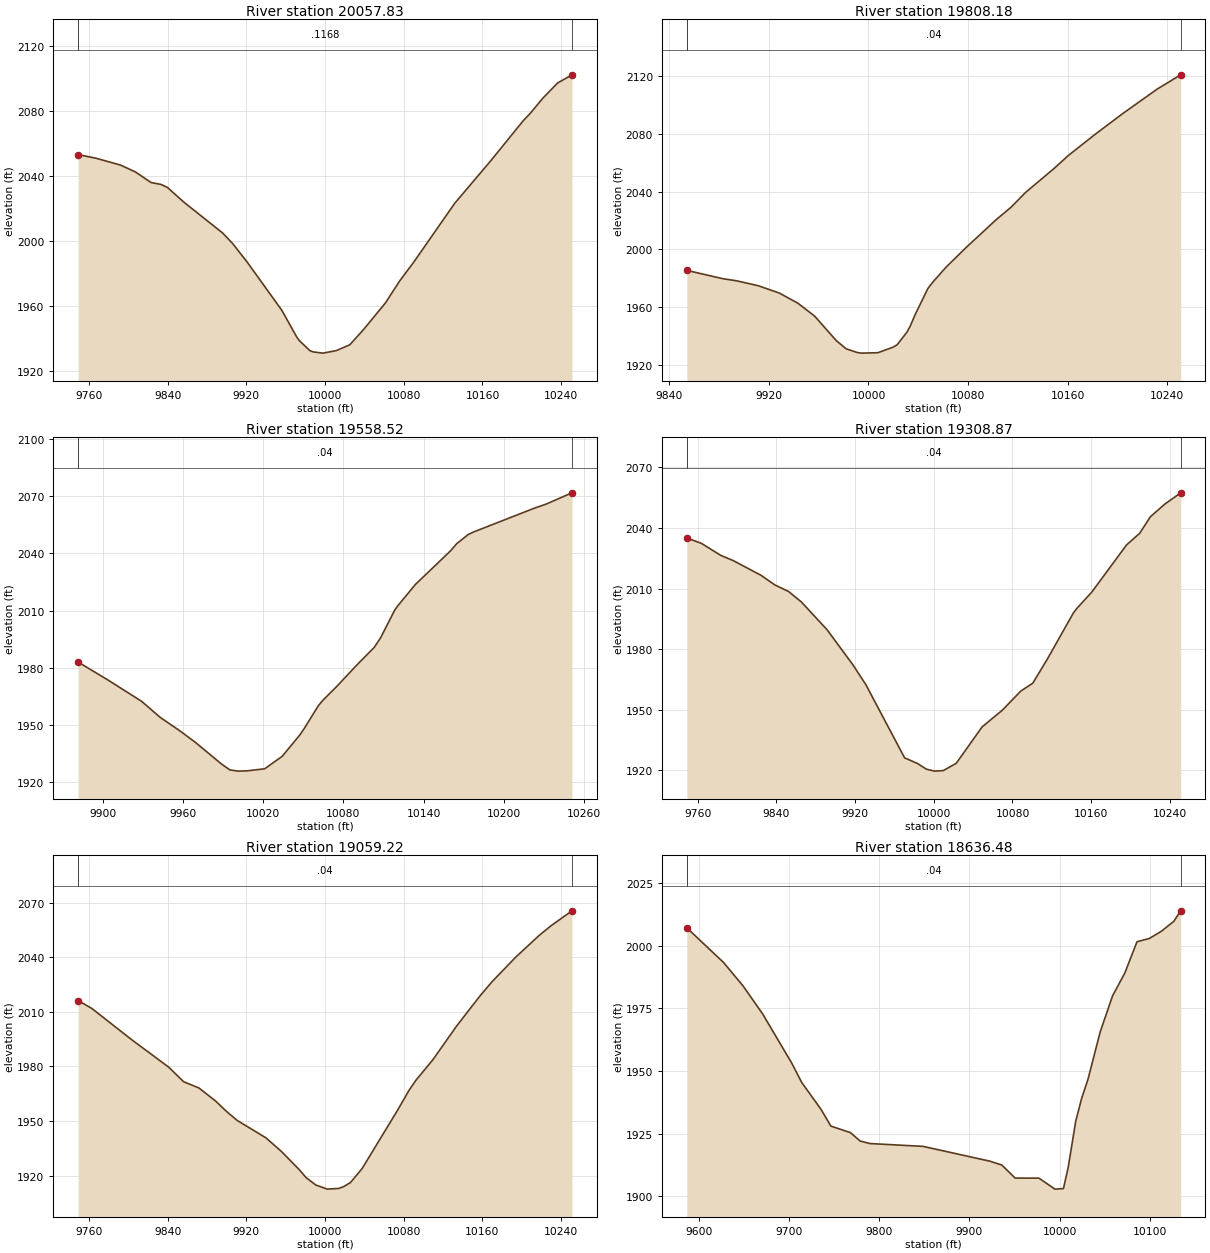
Type RM Length L Ch R = 1 ,20057.83,249.653100,249.653100,249.653100
XS GIS Cut Line= 6
700234.450716388770687.228701308700278.719042658770641.429733391
 700375.64807309770512.854798484700447.070683397770435.696548668
700515.302745507770372.603624075700579.810311181770327.061052638
#Sta/Elev= 30
9749.0582053.2029767.1062050.9869792.2922046.7079807.2572042.5239823.2562035.967
9833.3972034.8069839.8682032.937 9856.482023.9089896.0142004.8299906.3151998.221
 9921.061986.7849956.1511957.1519971.1531940.831 9973.841938.5359984.4021932.433
9987.8291931.5739997.8481930.78710011.521932.35310025.211935.93910038.891945.152
 10061.31961.65710075.951975.35610090.141986.87410131.792023.15210168.312049.304
 10201.4 2074.0610209.012078.92810221.41    208810236.362097.33410250.972102.384
#Mann= 3 , 0 , 0
9749.058  0.1168       09749.058  0.1168       010250.97  0.1168       0
#XS Ineff= 2 , 0
       0                               0
Bank Sta=9749.058,10250.97
Exp/Cntr=0.3,0.1

Type RM Length L Ch R = 1 ,19808.18,249.653100,249.653100,249.653100
XS GIS Cut Line= 6
 700486.77563372770713.472546506700548.046067771 770690.47680515
700619.966967727770606.918717634700665.282172881770567.303330599
700725.519712863770531.429695325700809.196356934770498.896241545
#Sta/Elev= 30
9854.0241985.4849883.0341979.7129893.8241978.3139911.4391974.8589928.4461969.759
9943.2431962.7669956.6151953.9149974.1161936.8549981.9691931.2199990.7941928.652
9994.4641928.18910007.561928.47410019.981932.38910023.021933.98210030.641942.413
 10033.41946.64810037.631955.129 10047.81973.03110051.531977.18810062.431987.808
10077.772000.76610102.512020.54810114.462029.13910126.392039.59510149.122056.053
10160.482064.96810182.332079.83410204.162093.97910232.082111.07610250.932120.921
#Mann= 3 , 0 , 0
9854.024    0.04       09854.024    0.04       010250.93    0.04       0
#XS Ineff= 2 , 0
       0                               0
Bank Sta=9854.024,10250.93
Exp/Cntr=0.3,0.1

Type RM Length L Ch R = 1 ,19558.52,249.653200,249.653200,249.653200
XS GIS Cut Line= 6
 700477.02759416770738.612227488700496.442529103770748.626075171
700523.669695019770772.391837362700592.673165982770855.012588079
700632.739101368770896.209052621700747.547326737770986.483916748
#Sta/Elev= 30
9881.6051982.9899903.4691973.7659929.0941962.3779943.0641953.9159957.4321947.016
 9969.041940.9879988.7741929.5119995.0161926.406   100011925.72910008.051925.887
10021.141926.95410034.221933.49510047.31 1944.6210050.661948.02810061.251960.055
   100651963.182 10075.2  1970.310089.151980.781 10103.11990.70710107.76 1995.63
10118.372010.23410120.872012.68310133.822023.70310160.232041.42810164.732045.107
10173.342049.94810177.322051.25610223.05 2063.8310231.432065.85510250.942071.828
#Mann= 3 , 0 , 0
9881.605    0.04       09881.605    0.04       010250.94    0.04       0
#XS Ineff= 2 , 0
       0                               0
Bank Sta=9881.605,10250.94
Exp/Cntr=0.3,0.1

Type RM Length L Ch R = 1 ,19308.87,249.653100,249.653100,249.653100
XS GIS Cut Line= 6
700197.913832982 770795.79556716700233.424922584 770823.63732063
700269.509860341770859.570340241700370.453189105770978.356905047
 700437.62092712771057.342603786700535.675385209771165.926456314
#Sta/Elev= 30
9749.0672035.1099763.9852032.4029783.4862026.4969796.4142023.8549824.4672016.612
9838.6392011.8169852.2422008.6779865.3662003.4649891.614 1989.669917.8611972.289
9930.9851962.4939970.3571926.2599983.4811923.4549992.5651920.637   100011919.677
10009.721919.95210022.851923.541 10049.11941.55210069.761949.87410088.481959.327
10100.641963.21310115.691975.35210141.95 1998.0210145.54 2000.2910160.462008.218
10195.842031.60210209.322037.43210220.142045.60610235.062051.96310250.992057.451
#Mann= 3 , 0 , 0
9749.067    0.04       09749.067    0.04       010250.99    0.04       0
#XS Ineff= 2 , 0
       0                               0
Bank Sta=9749.067,10250.99
Exp/Cntr=0.3,0.1

Type RM Length L Ch R = 1 ,19059.22,422.733800,422.733800,422.733800
XS GIS Cut Line= 6
700084.329372704 770901.18692964700101.153042544  770980.0465873
700115.284190528771019.689414939700138.712449969771069.864846955
  700192.8872905771161.842688321700312.622866764771342.828373243
#Sta/Elev= 30
9749.0532016.2089763.0822011.8129803.8711994.5249841.2061979.568 9856.24 1971.61
9871.8351968.1499888.7321961.0319899.7691955.3329910.8051950.2989940.1311940.695
9955.9821933.1419973.8361923.2669980.8251918.8959990.6371914.84310002.321912.583
10014.121912.97810019.111914.00210025.911916.21710037.771923.93910073.741955.941
10085.731967.14910092.181972.25410109.711983.72310133.692002.12910157.672018.844
10169.662026.46410193.642039.92710217.622051.95310229.612057.24510250.992065.476
#Mann= 3 , 0 , 0
9749.053    0.04       09749.053    0.04       010250.99    0.04       0
#XS Ineff= 2 , 0
       0                               0
Bank Sta=9749.053,10250.99
Exp/Cntr=0.3,0.1

Type RM Length L Ch R = 1 ,18636.48,326.225600,326.225600,326.225600
XS GIS Cut Line= 4
700017.078239411  770927.3330414699932.505990148771131.633661449
699905.585609138771169.296524391699699.369906098771359.624708071
#Sta/Elev= 30
9586.4882007.0289627.2551993.2169648.9011983.8789670.5471972.7729703.0151953.047
9713.8381945.5049735.4841934.6579746.307 1928.059767.9531925.4589778.7761922.107
9789.599  1921.19848.6151919.9679922.7351914.0779936.0271912.5269950.7711907.339
9977.1681907.3169995.0041902.93610004.381903.16310009.751911.78110017.991929.943
10024.49 1938.98 10031.61946.67810045.211965.63110058.821979.87810072.431989.001
10086.032001.50610099.642002.79210112.962005.64910126.862009.64610134.522013.815
#Mann= 3 , 0 , 0
9586.488    0.04       09586.488    0.04       010134.52    0.04       0
#XS Ineff= 2 , 0
       0                               0
Bank Sta=9586.488,10134.52
Exp/Cntr=0.3,0.1

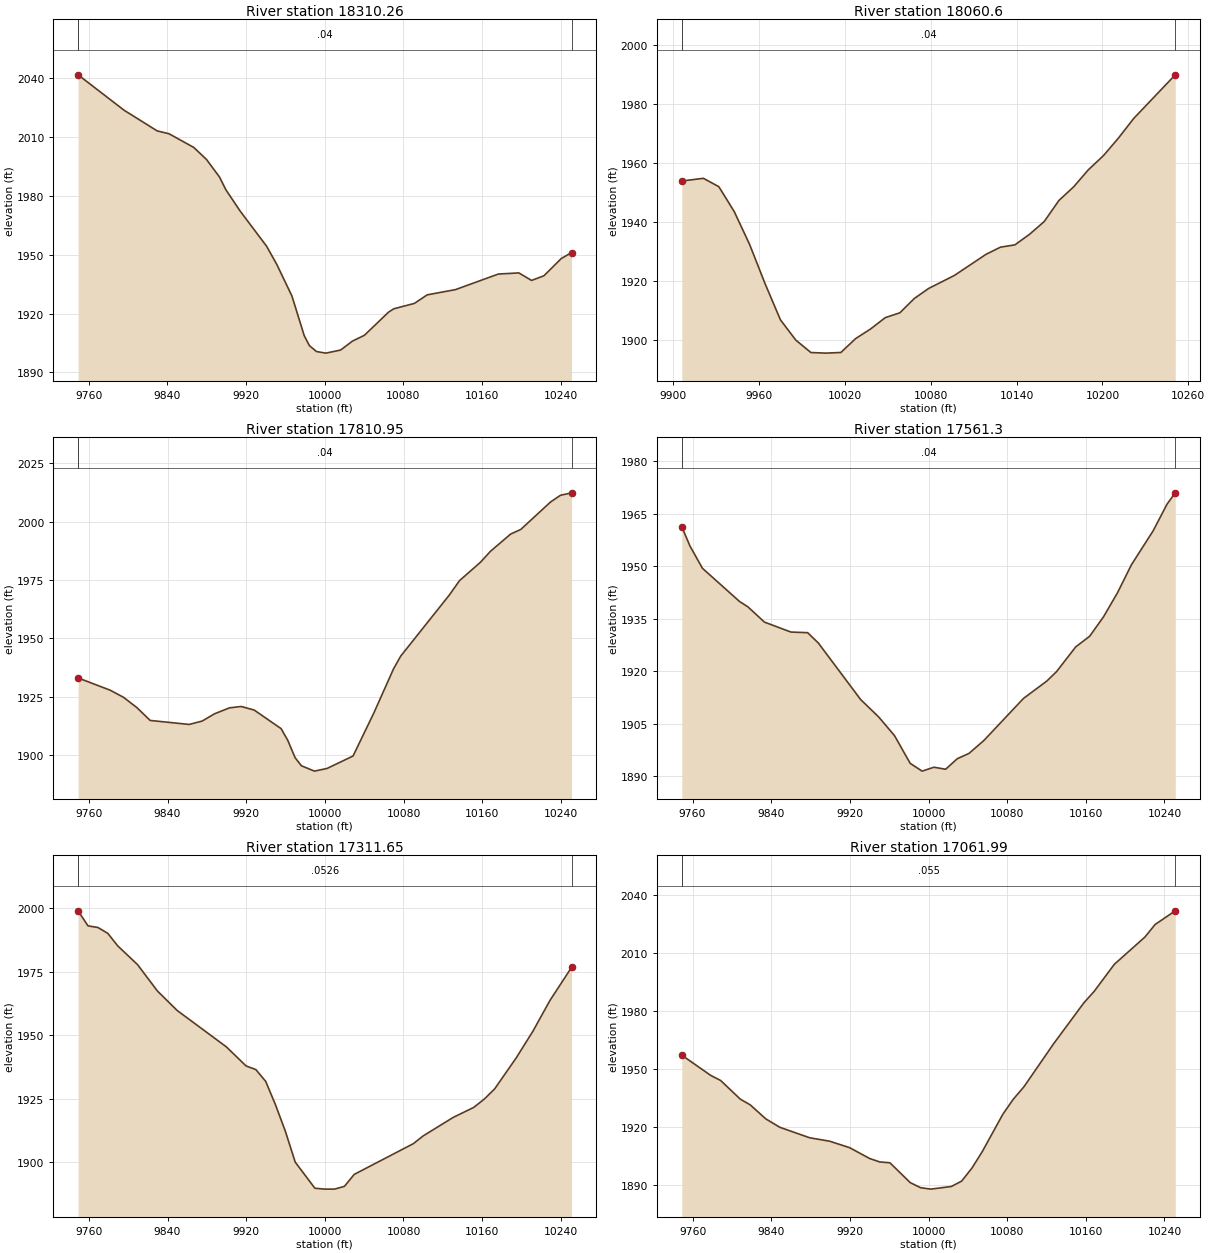
Type RM Length L Ch R = 1 ,18310.26,249.653200,249.653200,249.653200
XS GIS Cut Line= 6
699933.118095986770772.784156757699903.609827221770837.092042962
699863.011868664770891.372045068699813.693867893770938.006052093
699693.548350064771028.110592229 699598.69162013771137.345055736
#Sta/Elev= 30
9749.0942041.6069795.8822023.5719829.5362013.0459841.5932011.5859866.7322004.625
9879.6331998.5299892.9281989.5469899.311 1983.159913.6111972.4139940.8051954.307
9951.2011945.0129966.6081928.9039979.0591908.7879984.3091903.674 9991.511900.655
   100011899.833   100161901.38610028.151905.961 10040.31908.92310064.931920.748
10070.251922.432 10091.1 1925.1510104.191929.52610132.831932.173 10176.51940.117
10197.361940.69810210.281936.86510222.851939.22410240.531948.03310250.941951.032
#Mann= 3 , 0 , 0
9749.094    0.04       09749.094    0.04       010250.94    0.04       0
#XS Ineff= 2 , 0
       0                               0
Bank Sta=9749.094,10250.94
Exp/Cntr=0.3,0.1

Type RM Length L Ch R = 1 , 18060.6,249.653100,249.653100,249.653100
XS GIS Cut Line= 6
699520.874489869770860.970635496699561.899165442770971.352975449
699574.231201545771042.784886526699571.355971304771086.978860404
699560.862801269771132.054011761699540.882709349771192.620567531
#Sta/Elev= 30
9906.0471953.956 9921.15 1954.879931.915 1952.04 9942.681943.6039953.4451932.444
 9964.211919.1829974.9751906.8789985.7221900.0059996.2781895.78510006.771895.584
10017.231895.80510027.63 1900.5510037.931903.75710048.241907.61810058.461909.264
10068.531914.10510078.591917.527 10096.51921.91510118.731929.11210128.791931.526
10138.85  1932.310149.081935.88410159.341940.21210169.611947.35610179.88 1951.97
10190.221957.77810200.75 1962.5710211.281968.56110221.811975.133 10250.91989.967
#Mann= 3 , 0 , 0
9906.047    0.04       09906.047    0.04       0 10250.9    0.04       0
#XS Ineff= 2 , 0
       0                               0
Bank Sta=9906.047,10250.9
Exp/Cntr=0.3,0.1

Type RM Length L Ch R = 1 ,17810.95,249.653100,249.653100,249.653100
XS GIS Cut Line= 6
699172.622180754770881.025028308699299.947105725771024.847335769
699364.947325801771083.222839009699392.805293737771117.199890004
699426.990041712 771191.31906307 699443.59481976771286.164349996
#Sta/Elev= 30
9749.0341933.0069781.6451927.7599795.247 1924.719808.8491920.2979822.3221914.801
9861.9961913.087 9875.221914.5319887.735 1917.649903.0171920.1929914.8941920.781
9928.1181919.2539955.5321911.2819962.3811906.1849969.706 1898.879976.1321895.389
9989.3941893.08910002.251894.23610028.671899.56510049.891918.07210069.851936.917
10077.161942.37610126.381968.41910137.031974.725 10158.21982.54910168.46 1987.27
10188.961994.64210199.211996.60110229.53 2008.38 10239.62011.24110250.842012.297
#Mann= 3 , 0 , 0
9749.034    0.04       09749.034    0.04       010250.84    0.04       0
#XS Ineff= 2 , 0
       0                               0
Bank Sta=9749.034,10250.84
Exp/Cntr=0.3,0.1

Type RM Length L Ch R = 1 , 17561.3,249.653200,249.653200,249.653200
XS GIS Cut Line= 6
698948.359906389771004.075218429699015.591085623771055.799351535
699068.152892816771106.165758853699103.727892492771150.043674701
699178.988711829 771260.00725286699286.403224467 771370.90960682
#Sta/Elev= 30
9749.0771961.2359757.4551955.6949770.0721949.3749807.9231939.8649816.1921938.393
9833.1571934.0039860.0261931.1669877.0721930.9849887.9621928.0329930.9821911.888
9949.3641906.9169965.4651901.5739981.3851893.6699993.5291891.44710005.561892.562
10017.431891.98210029.311894.99910041.191896.50510056.321900.19510096.54 1912.19
10120.39 1917.1810130.261919.86810149.731926.92310163.911929.95910178.091935.546
10192.271942.40310206.451950.39810228.531960.09110242.631967.68510250.971970.921
#Mann= 3 , 0 , 0
9749.077    0.04       09749.077    0.04       010250.97    0.04       0
#XS Ineff= 2 , 0
       0                               0
Bank Sta=9749.077,10250.97
Exp/Cntr=0.3,0.1

Type RM Length L Ch R = 1 ,17311.65,249.653100,249.653100,249.653100
XS GIS Cut Line= 6
698805.005481072771378.623828018698941.011883645771393.550072801
699110.042367066771396.140361395699160.990579765 771400.58449907
699222.865800709771417.150385677 699293.63963172771455.541078916
#Sta/Elev= 30
9749.0311999.0099759.1081993.0859769.1911992.4519779.2741990.1289789.3571985.202
9809.5231977.8089829.6851967.4419849.7541959.7669899.8791945.4039919.8811937.899
9929.8831936.4589939.8841931.7969949.885 1922.519959.8861912.1229969.8881899.997
 9989.891889.7199999.8921889.36410009.891889.37710019.891890.44410029.891895.173
10090.031907.28210100.07 1910.3510130.641917.63810151.411921.55710161.941924.767
10172.571928.78510194.561941.01610211.691951.61410229.011963.728 10250.91976.711
#Mann= 3 , 0 , 0
9749.031  0.0526       09749.031  0.0526       0 10250.9  0.0526       0
#XS Ineff= 2 , 0
       0                               0
Bank Sta=9749.031,10250.9
Exp/Cntr=0.3,0.1

Type RM Length L Ch R = 1 ,17061.99,249.653200,249.653200,249.653200
XS GIS Cut Line= 6
698775.765783553 771596.33291688698884.496430428771607.419683105
698960.274860085771620.341027848 699001.89905879 771631.11094971
699099.245632369771660.772563771 699264.61036962 771704.30053426
#Sta/Elev= 30
9749.0421957.0829778.4281946.639 9788.48 1944.039808.5831934.3539818.6351931.424
9834.483 1924.179848.7911919.8079879.136  1914.49899.4251912.6329919.7131909.302
9940.0891903.6969950.4191901.9129960.7481901.477 9981.44 1891.229991.8751888.616
10002.321887.86410023.231889.23410033.691892.00210044.151898.70810054.611907.176
10075.531926.47410085.91 1934.1110097.171940.81910127.171962.91810158.121984.181
10168.441989.99110189.072004.06510220.15 2018.1210230.572024.63710250.992031.675
#Mann= 3 , 0 , 0
9749.042   0.055       09749.042   0.055       010250.99   0.055       0
#XS Ineff= 2 , 0
       0                               0
Bank Sta=9749.042,10250.99
Exp/Cntr=0.3,0.1

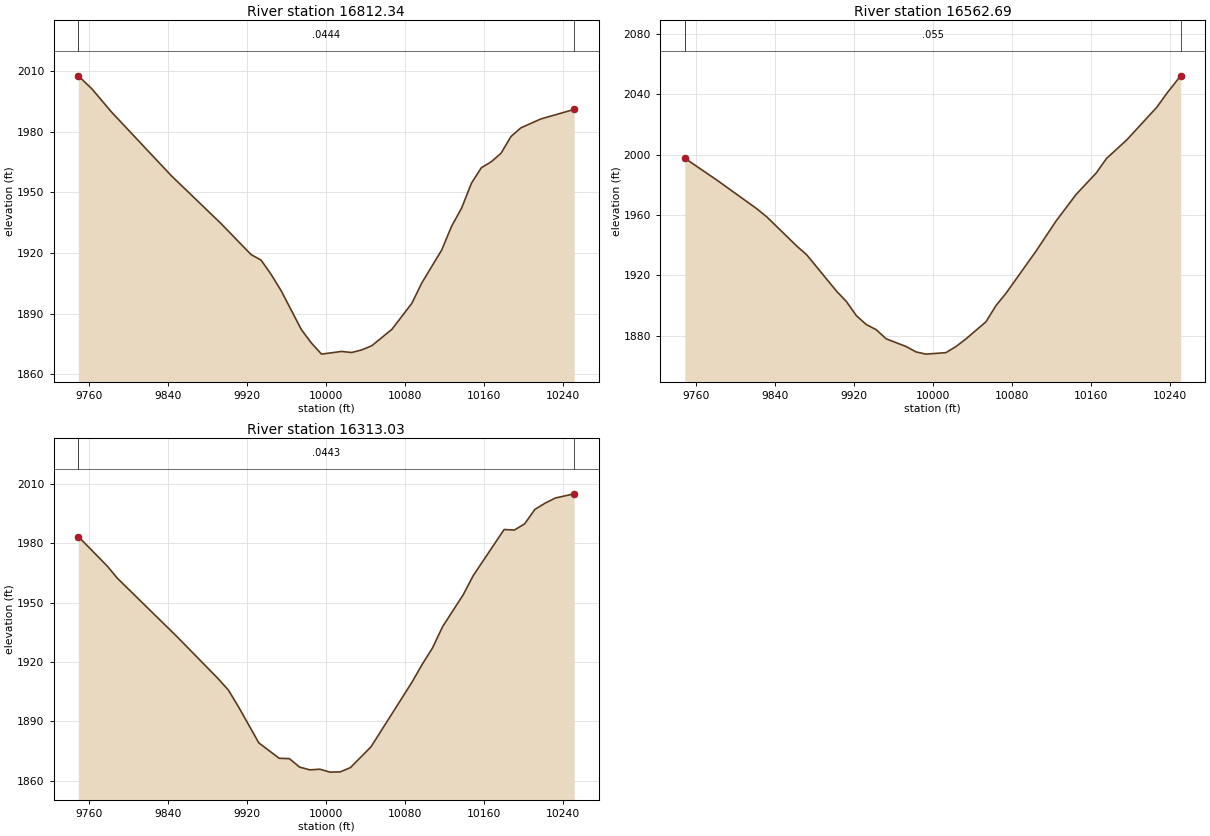
Type RM Length L Ch R = 1 ,16812.34,249.653100,249.653100,249.653100
XS GIS Cut Line= 6
698781.135841291771913.084953999698917.064659142771902.071937954
699088.961892077 771869.94117654699144.717625574771862.312689014
699215.236784443771860.393540699699278.693866447771866.467150766
#Sta/Elev= 30
 9749.022007.5229762.907 2001.01 9782.941989.4689843.1271958.2089893.4811934.547
9923.8821919.2379934.0161916.4859944.178 1909.459954.3761901.3399974.7711882.201
9984.969 1875.549995.1671870.05810015.541871.39110025.731870.86110035.921872.147
10046.111874.20910066.431882.29510086.611895.13910096.78 1905.2710116.891921.516
10126.911933.27210136.921942.10410146.941954.44810156.951962.11210166.951965.048
10176.951969.29410186.951977.536   101971981.81510217.091986.20410250.941990.934
#Mann= 3 , 0 , 0
 9749.02  0.0444       0 9749.02  0.0444       010250.94  0.0444       0
#XS Ineff= 2 , 0
       0                               0
Bank Sta=9749.02,10250.94
Exp/Cntr=0.3,0.1

Type RM Length L Ch R = 1 ,16562.69,249.653100,249.653100,249.653100
XS GIS Cut Line= 6
698791.919630424772101.693975286698926.095307292772111.813873301
699040.769253574772125.014523547 699056.83896718772127.096704775
699180.805112567772147.871311835699288.455138437772170.868660553
#Sta/Elev= 30
9749.0121997.5519782.1861982.734  9822.31963.8669832.3281958.4779862.4141939.289
9872.4421933.5159902.5981909.4669912.6641902.494 9922.731893.1799932.7961887.278
9942.8621883.8529952.9281877.8229973.0611872.7249983.1271869.1429993.193 1867.68
10013.351868.65410023.481872.67610033.621877.745 10053.91889.11110064.041899.859
10074.181908.00110104.591935.96810124.871955.90510145.19 1973.5510165.641987.825
10175.871997.33410196.322009.59210226.992031.42210237.222040.73210250.982052.161
#Mann= 3 , 0 , 0
9749.012   0.055       09749.012   0.055       010250.98   0.055       0
#XS Ineff= 2 , 0
       0                               0
Bank Sta=9749.012,10250.98
Exp/Cntr=0.3,0.1

Type RM Length L Ch R = 1 ,16313.03,249.653200,249.653200,249.653200
XS GIS Cut Line= 6
698735.939142671772313.995563945 698819.52234994772328.647259501
 698896.21198706772345.604327107  698982.1974331772366.916425662
 699011.72300545772374.351720121699223.369784022772432.713507586
#Sta/Elev= 30
9749.0131983.4729778.5171968.4419788.669 1962.349849.722 1932.469890.6881911.546
 9900.931905.8549911.1711897.395 9931.771879.1359952.3761871.3479962.6791871.172
9972.9821866.9189983.2851865.5029993.5881865.82810003.891864.351 10014.21864.485
10024.511866.64910045.221877.07810086.711909.76410097.091918.80610107.461927.027
10117.831937.94910138.581953.98810148.951963.83310180.071987.04110190.451986.773
10200.821989.88210211.191997.19110221.562000.36910231.942002.97510250.992005.091
#Mann= 3 , 0 , 0
9749.013  0.0443       09749.013  0.0443       010250.99  0.0443       0
#XS Ineff= 2 , 0
       0                               0
Bank Sta=9749.013,10250.99
Exp/Cntr=0.3,0.1