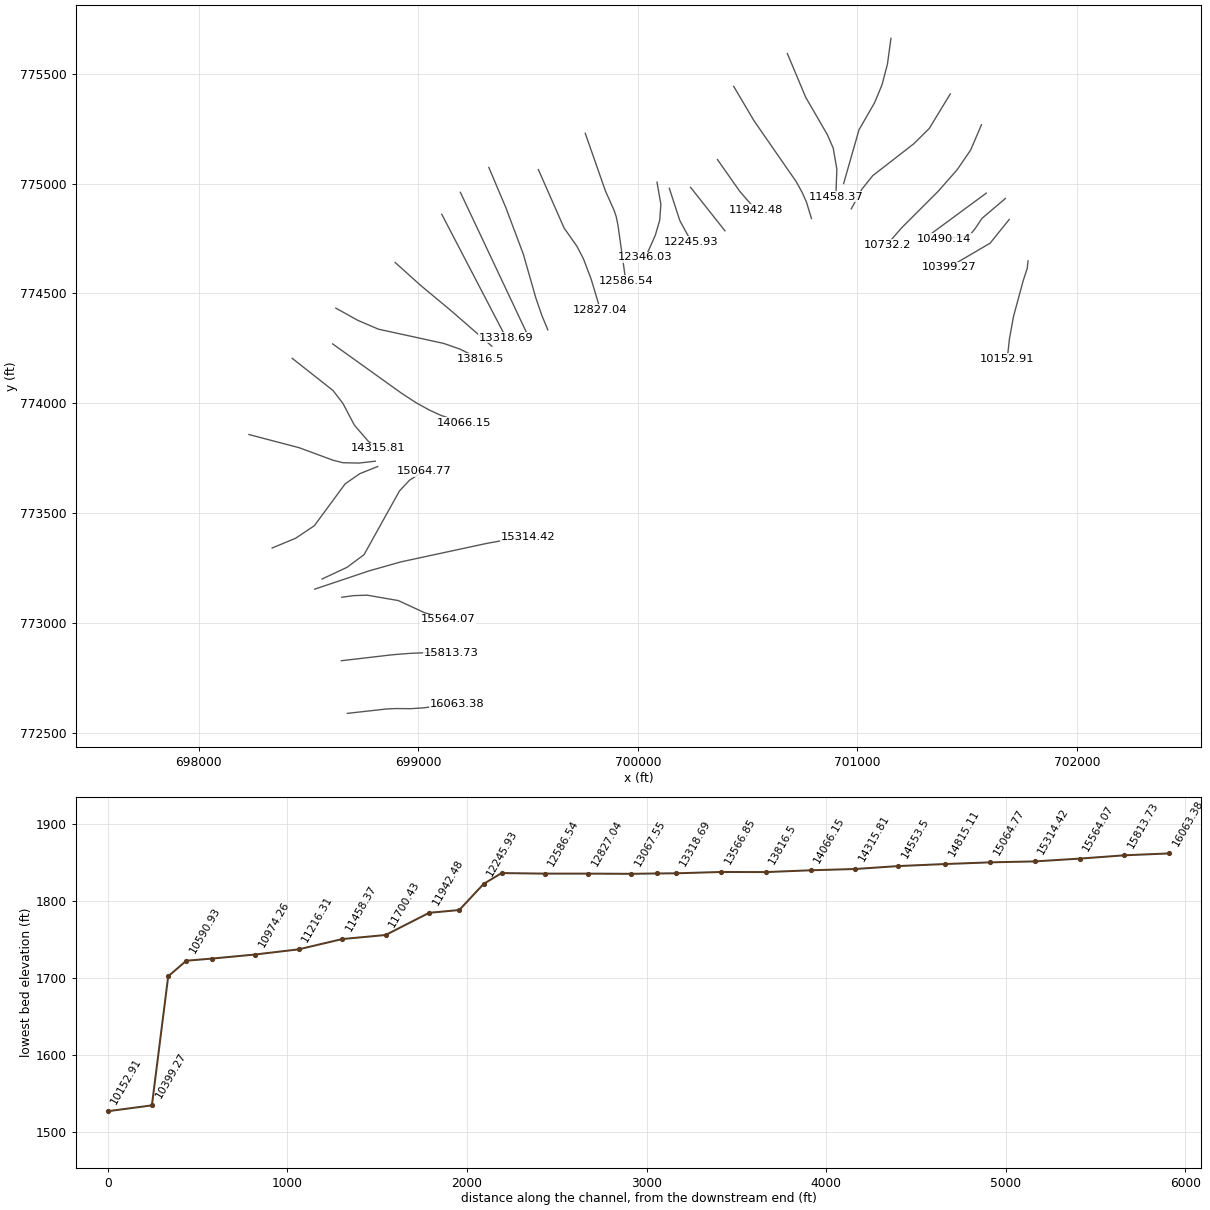
HEC-RAS study 14441_ras.prj: 14441

--- 14441_ras.g01 (geometry) --- (continued)

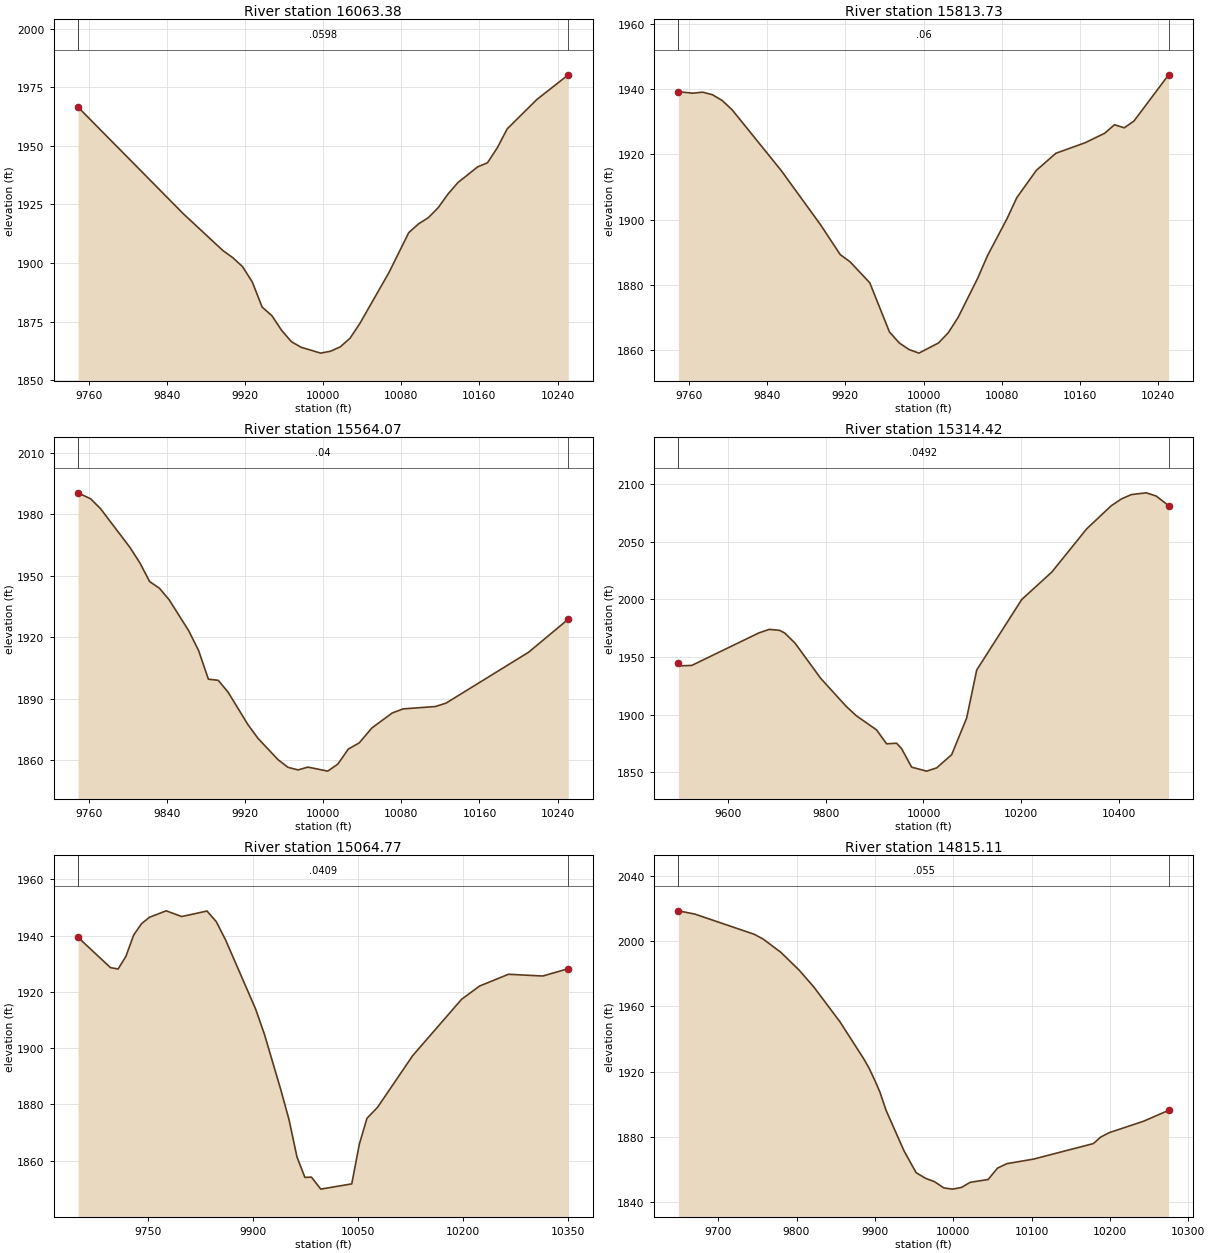
Type RM Length L Ch R = 1 ,16063.38,249.653100,249.653100,249.653100
XS GIS Cut Line= 6
698677.665306306772587.843883299698855.009913777772607.809671884
698898.792039006772609.843880773698965.299645047772609.234843037
699023.889296456 772612.95165569699177.090519239772632.346789718
#Sta/Elev= 30
9749.0141966.506 9857.151920.8739897.3471905.3069907.3931902.2829917.4381898.463
9927.4841891.8469937.4951881.1869947.5051877.5129957.5161871.2129967.5271866.403
9977.5321864.0259997.533 1861.5410007.531862.35710017.531864.22210027.531867.915
10037.541874.18710067.591896.11810087.631912.96910097.661916.70610107.741919.365
10112.851921.51310117.821923.633 10127.91929.48210137.981934.32110158.141941.021
10168.221942.767 10178.31949.17210188.381957.22610218.621969.71710250.971980.299
#Mann= 3 , 0 , 0
9749.014  0.0598       09749.014  0.0598       010250.97  0.0598       0
#XS Ineff= 2 , 0
       0                               0
Bank Sta=9749.014,10250.97
Exp/Cntr=0.3,0.1

Type RM Length L Ch R = 1 ,15813.73,249.653200,249.653200,249.653200
XS GIS Cut Line= 6
698650.358593257 772827.60654767698875.942705115772854.003608125
698898.720202132772856.107886108698959.859792959772860.983709409
699040.348080372772864.464422691699150.434564501772864.094610779
#Sta/Elev= 30
9749.0021939.1599763.7441938.6789773.8121939.003 9783.881938.2139793.9481936.424
9804.0161933.6089854.3581914.9749894.631 1898.379914.7671889.2399924.8351887.043
9944.9721880.6349965.1081865.5819975.1761862.1969985.2211860.1849995.2641859.079
10015.33 1862.1910025.361865.32610035.391869.99210055.461881.99710065.48 1888.91
 10085.51900.23810095.511906.69410115.531915.05210135.541920.28510165.551923.514
10185.55 1926.4210195.551929.02310205.551928.08210215.551930.17110250.981944.307
#Mann= 3 , 0 , 0
9749.002    0.06       09749.002    0.06       010250.98    0.06       0
#XS Ineff= 2 , 0
       0                               0
Bank Sta=9749.002,10250.98
Exp/Cntr=0.3,0.1

Type RM Length L Ch R = 1 ,15564.07,249.653100,249.653100,249.653100
XS GIS Cut Line= 6
698652.260028979773116.580795547698705.884079225773124.104487187
698767.882873725773126.048327573698909.302485392773101.654459695
699029.601258276773046.106479674699134.411016824773015.587165416
#Sta/Elev= 30
9749.0781990.3629761.9431987.4579772.0411982.6779802.3351963.6839812.3621956.258
9822.3821947.1169832.4031943.8739842.4131938.2049862.4131923.1239872.4511913.578
9882.5031899.5859892.5561899.0329902.6091893.2989923.0091877.4239933.2591870.773
9953.7581860.3869964.0081856.6419974.2581855.3869984.4731856.75710004.671854.793
10015.071858.24210025.691865.52210036.911868.56410049.911875.84510070.651883.103
10081.891885.11810114.911886.26110125.791887.92110210.291912.71110250.911928.809
#Mann= 3 , 0 , 0
9749.078    0.04       09749.078    0.04       010250.91    0.04       0
#XS Ineff= 2 , 0
       0                               0
Bank Sta=9749.078,10250.91
Exp/Cntr=0.3,0.1

Type RM Length L Ch R = 1 ,15314.42,249.653100,249.653100,249.653100
XS GIS Cut Line= 6
698529.038455954773153.629334641698776.567073798773236.802945572
698922.828203772773278.048536235699312.951321563773362.061958124
699413.986132588773380.365392595 699500.14644145773393.073183111
#Sta/Elev= 30
9499.0291944.9289505.3181942.4469526.4171942.7759663.5591970.9449684.6581974.008
9705.7571973.1839716.3071970.8859737.4051962.1379789.8381931.6219841.9291907.335
9862.6321899.1969904.0371886.9259924.5981874.8389945.069 1875.359955.3051870.623
9975.7761854.60410006.461851.16710026.911853.968 10057.6 1865.4410088.281897.247
10108.741938.75310200.791999.88810262.162023.63910333.62 2061.1710383.792081.169
10404.762087.10810425.022090.83810455.35 2092.3410475.562089.54710500.982081.275
#Mann= 3 , 0 , 0
9499.029  0.0492       09499.029  0.0492       010500.98  0.0492       0
#XS Ineff= 2 , 0
       0                               0
Bank Sta=9499.029,10500.98
Exp/Cntr=0.3,0.1

Type RM Length L Ch R = 1 ,15064.77,249.653200,249.653200,249.653200
XS GIS Cut Line= 6
698562.266137541773199.639308457698676.457389013773253.169742256
698753.622925812773310.779591217698914.867757021773600.750925282
698960.973095727773649.986934013699027.032530916773691.485118445
#Sta/Elev= 30
9649.1611939.3649695.6311928.6239706.5051928.1349717.5561932.5719728.7881940.214
9740.019 1944.239751.2511946.4999775.352  1948.89797.5091946.7679833.7631948.723
9847.0831944.9279860.4041938.431 9903.351913.9199915.9441904.9419939.4671885.188
9951.1861874.5839962.5391861.3699973.8931854.0959983.2811854.196  9996.6 1849.93
10040.961851.79410051.851865.93910062.751875.09810077.841878.982 10128.21897.359
10198.17 1917.3710223.921922.08210265.321926.26110314.471925.64310350.921928.241
#Mann= 3 , 0 , 0
9649.161  0.0409       09649.161  0.0409       010350.92  0.0409       0
#XS Ineff= 2 , 0
       0                               0
Bank Sta=9649.161,10350.92
Exp/Cntr=0.3,0.1

Type RM Length L Ch R = 1 ,14815.11,261.618300,261.618300,261.618300
XS GIS Cut Line= 6
698335.137238917773341.046520478698441.568104442773385.155473045
 698527.13126446773442.362550933698667.584863095 773633.12453437
 698733.99225114773679.273840793698815.414942139773711.934259021
#Sta/Elev= 30
9649.1512018.7249670.2612016.7129746.2352004.2729757.2362001.4319780.0581993.205
9803.5021982.2119822.0371971.9569855.302 1950.649885.719 1927.879892.415 1922.22
9900.097 1914.429906.3321907.4989914.2651896.1779937.356 1871.119952.6591857.858
9964.4771854.4469976.2961852.293 9987.911848.5149999.2161847.75410010.491848.786
10021.791851.94310044.561853.66710056.581860.671 10068.61863.41910102.211866.166
10178.921875.739 10188.21879.71410199.141882.44810242.91 1889.4610274.971896.152
#Mann= 3 , 0 , 0
9649.151   0.055       09649.151   0.055       010274.97   0.055       0
#XS Ineff= 2 , 0
       0                               0
Bank Sta=9649.151,10274.97
Exp/Cntr=0.3,0.1

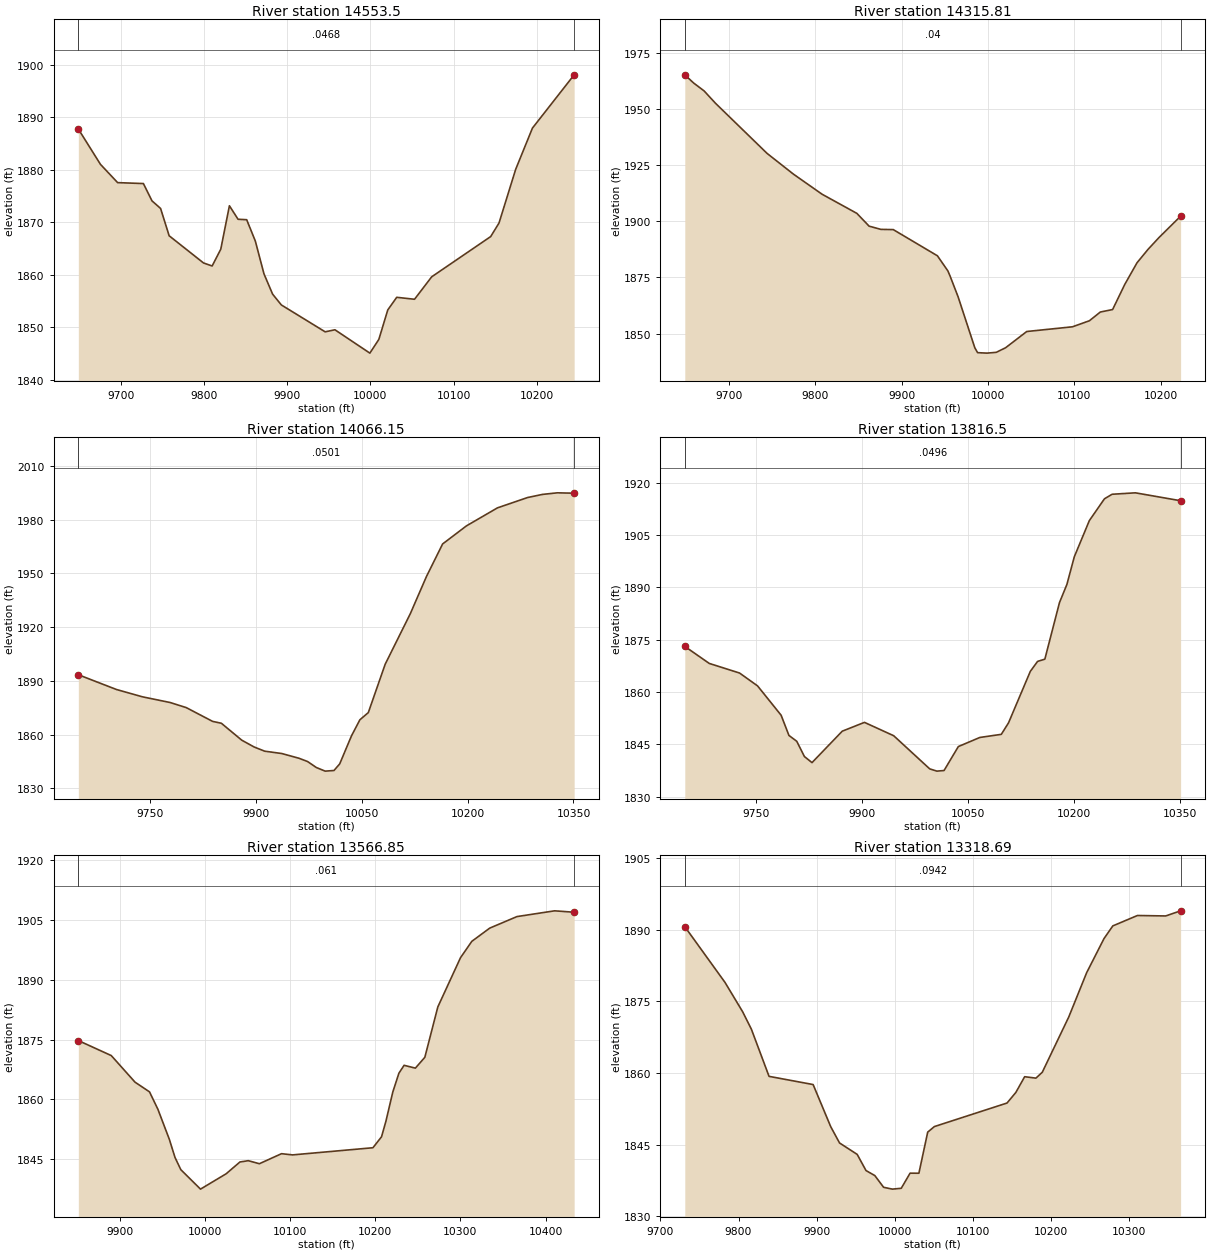
Type RM Length L Ch R = 1 , 14553.5,237.688000,237.688000,237.688000
XS GIS Cut Line= 6
698229.238005849773857.633023418698457.329369448773797.874125468
698612.226877081773740.666538477698657.292052373773729.340898847
 698730.82507125773727.676740649698804.770181624773736.328501841
#Sta/Elev= 30
9649.2561887.7789675.8351881.0549696.4691877.571 9727.421877.3949737.737  1874.1
9748.0541872.6589758.3721867.452 9799.641862.2769809.9971861.7019820.3751864.898
9830.7531873.166 9841.131870.5989851.508 1870.519861.8861866.4439872.2641860.204
9882.6421856.3399893.1321854.2859945.7541849.1659957.5051849.5549999.4621845.109
10010.231847.71410020.981853.33410031.741855.73710053.121855.36410073.741859.639
10144.58  1867.310154.591869.87610174.621880.10310194.761887.95210244.871898.097
#Mann= 3 , 0 , 0
9649.256  0.0468       09649.256  0.0468       010244.87  0.0468       0
#XS Ineff= 2 , 0
       0                               0
Bank Sta=9649.256,10244.87
Exp/Cntr=0.3,0.1

Type RM Length L Ch R = 1 ,14315.81,249.653100,249.653100,249.653100
XS GIS Cut Line= 6
698426.421207348774204.653462978698612.076205674774058.388933897
698657.340372924773999.505920066698709.518945899773900.325943899
698773.055895999773826.665213739698816.002351046773795.866760954
#Sta/Elev= 30
9649.0891965.1749659.3891961.5129671.396 1958.039684.5971952.5289744.3911930.201
9774.9321920.9689808.0181912.0469848.2981903.5289862.4771897.842 9876.051896.402
9890.4571896.3039941.568 1884.659953.7131877.914 9956.261875.6099965.5151866.415
9984.871 1843.739988.0981841.5469998.8551841.33410009.681841.68210020.561843.734
10045.011850.95310097.951853.048 10117.51855.72710130.221859.62410144.43 1860.73
10158.481871.88710172.671881.53210185.451887.51110198.231892.80510223.171902.277
#Mann= 3 , 0 , 0
9649.089    0.04       09649.089    0.04       010223.17    0.04       0
#XS Ineff= 2 , 0
       0                               0
Bank Sta=9649.089,10223.17
Exp/Cntr=0.3,0.1

Type RM Length L Ch R = 1 ,14066.15,249.653200,249.653200,249.653200
XS GIS Cut Line= 6
698610.688379311 774270.33586967698923.477350479774046.211100854
698990.380575519774002.618347159699050.545724763  773969.2473746
699105.192347882773944.293660774699207.915319849773909.961545119
#Sta/Elev= 30
9649.0111893.4249703.0881885.1769739.7421881.1119779.0061877.9249801.8341875.079
9839.0891867.3999851.5071866.3569880.4151856.9049898.0141853.0919912.7771850.783
9937.0821849.4629961.3871846.8259973.5391845.0029985.9921841.6549998.4511839.645
 10010.91839.98710019.021843.67110035.671859.292 10047.6 1868.2910059.541872.304
10083.411899.28710118.981927.47410141.851948.22910164.721966.39310198.391976.465
10242.361986.53510285.051992.29810306.12 1994.0410327.011994.92210350.941994.716
#Mann= 3 , 0 , 0
9649.011  0.0501       09649.011  0.0501       010350.94  0.0501       0
#XS Ineff= 2 , 0
       0                               0
Bank Sta=9649.011,10350.94
Exp/Cntr=0.3,0.1

Type RM Length L Ch R = 1 , 13816.5,249.653100,249.653100,249.653100
XS GIS Cut Line= 6
 698625.13337233774433.325186274698724.613120602774377.915958016
698819.357375185774337.379275924699116.219903013774272.586913543
699190.340675853774246.657334188699281.873717812774201.461657241
#Sta/Elev= 30
9649.0431873.0729683.651 1868.199726.5911865.4339752.0451861.7549785.4321853.331
9796.4671847.5429807.5011845.8779818.3921841.4969829.1341839.7569871.9541848.766
9903.4041851.2919944.7791847.4619995.7521837.962 10005.91837.31510016.031837.486
 10036.3 1844.36 10066.71846.96510097.111847.85910107.381851.17610138.191865.915
10148.461868.76710158.741869.40810179.461885.62810189.951890.83210200.43 1898.75
10221.711909.11710243.111915.37610253.941916.68110286.931917.09310350.951914.825
#Mann= 3 , 0 , 0
9649.043  0.0496       09649.043  0.0496       010350.95  0.0496       0
#XS Ineff= 2 , 0
       0                               0
Bank Sta=9649.043,10350.95
Exp/Cntr=0.3,0.1

Type RM Length L Ch R = 1 ,13566.85,248.160200,248.160200,248.160200
XS GIS Cut Line= 6
698895.460913062774640.843165085699005.228042394774542.267540693
699006.740164936774540.958539069 699019.75502497774529.732988507
699149.723063618774421.672507107699335.654966682774259.941289529
#Sta/Elev= 30
9851.4671874.7719890.1451871.001 9918.051864.3199935.0451861.8869944.9311857.497
9958.3721849.9419964.9781845.4149971.8121842.342 9994.911837.45710025.011841.309
10041.231844.27510051.02  1844.610064.021843.83710090.031846.35710103.041846.055
10197.381847.85210207.461850.59810212.611854.50510220.711861.84910227.851866.566
10233.971868.55610247.221867.84710258.33 1870.5710273.56 1883.2110300.231895.591
10313.49 1899.6910334.511903.012 10366.51905.909 10410.71907.35410433.641906.997
#Mann= 3 , 0 , 0
9851.467   0.061       09851.467   0.061       010433.64   0.061       0
#XS Ineff= 2 , 0
       0                               0
Bank Sta=9851.467,10433.64
Exp/Cntr=0.3,0.1

Type RM Length L Ch R = 1 ,13318.69,108.986900,108.986900,108.986900
XS GIS Cut Line= 2
699107.468606025774860.581182837699400.524161607774298.081182852
#Sta/Elev= 30
9731.2581890.5989782.6541878.9519805.2051872.8219816.4811869.1429839.0331859.297
9895.4111857.5849917.9631848.7649929.2391845.366 9951.791842.9829963.0661839.601
9974.3421838.5539985.6181836.0989996.8931835.71910008.171835.89910019.441839.054
10030.721839.043   100421847.63710050.561848.80110143.481853.72210154.751855.939
10166.031859.22510180.421858.92410188.581860.16110222.411871.70510245.351880.983
10267.511888.10310278.791890.75710310.281892.92910346.441892.83510365.521893.907
#Mann= 3 , 0 , 0
9731.258  0.0942       09731.258  0.0942       010365.52  0.0942       0
#XS Ineff= 2 , 0
       09907.219        10071.21       0
Bank Sta=9731.258,10365.52
Exp/Cntr=0.3,0.1

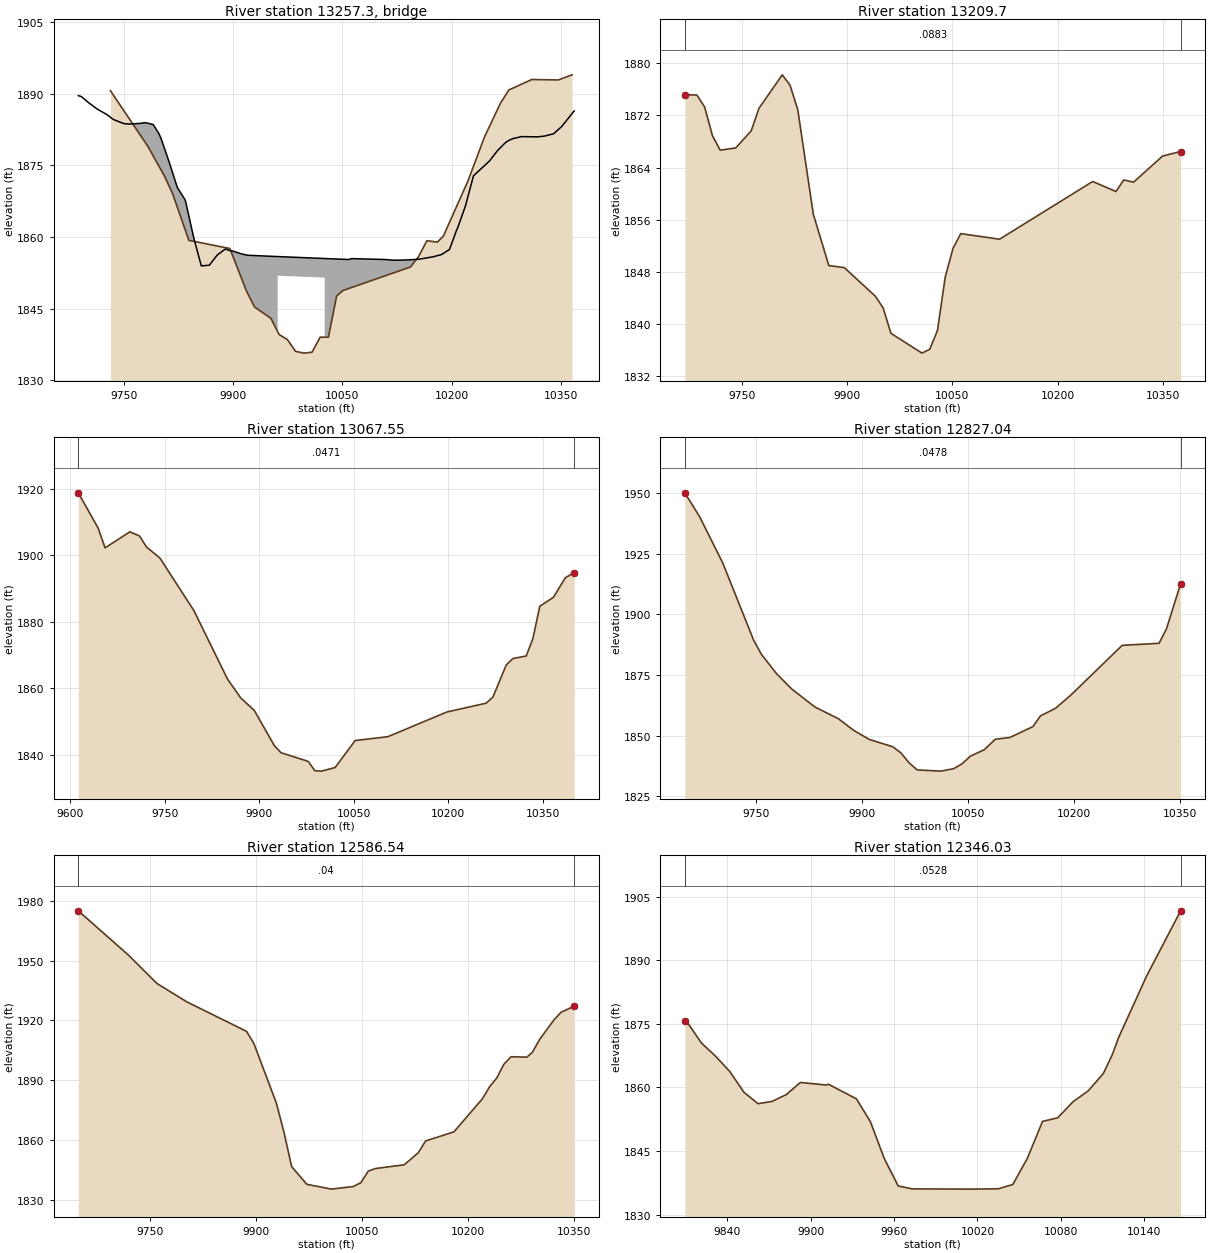
Type RM Length L Ch R = 3 , 13257.3,,,
BEGIN DESCRIPTION:
END DESCRIPTION:
Bridge Culvert--1,0,-1,-1, 0
Deck Dist Width WeirC Skew NumUp NumDn MinLoCord MaxHiCord MaxSubmerge Is_Ogee
45.471150,18.044600,2.6,0, 55, 55, , , 0.95, 0, 0,0,,
 9687.17 9691.17 9702.16 9713.16 9725.98 9735.15 9746.15 9750.02 9757.14 9774.06
 9779.14 9790.13 9798.10 9801.13 9812.13 9823.12 9834.12 9846.18 9856.11 9867.11
 9878.11 9889.10 9894.26 9900.10 9911.09 9919.73 9960.96 9960.9610025.6010025.60
10058.7810062.5510109.0310120.0310134.6810153.0210158.7210175.0110186.0110197.00
10206.8010208.0010218.9910229.9910251.9810262.9810273.9810278.9210284.9710295.97
10317.9610327.0110339.9610350.9510368.33
 1889.55 1889.37 1887.98 1886.74 1885.63 1884.59 1883.91 1883.70 1883.61 1883.78
 1883.92 1883.51 1881.55 1880.47 1875.58 1870.37 1867.70 1859.54 1853.97 1854.09
 1856.25 1857.48 1857.21 1857.03 1856.48 1856.18 1855.91 1855.91 1855.50 1855.50
 1855.29 1855.48 1855.29 1855.15 1855.18 1855.32 1855.44 1855.87 1856.33 1857.37
 1861.42 1861.78 1866.49 1872.79 1875.89 1878.06 1879.74 1880.23 1880.60 1880.99
 1880.94 1881.08 1881.58 1883.06 1886.35
  889.55  889.37  887.98  886.74  885.63  884.59  883.91  883.70  883.61  883.78
  883.92  883.51  881.55  880.47  875.58  870.37  867.70  859.54  853.97  854.09
  856.25  857.48  857.21  857.03  856.48  856.18  855.91 1851.91 1851.50  855.50
  855.29  855.48  855.29  855.15  855.18  855.32  855.44  855.87  856.33  857.37
  861.42  861.78  866.49  872.79  875.89  878.06  879.74  880.23  880.60  880.99
  880.94  881.08  881.58  883.06  886.35
 9687.17 9691.17 9702.16 9713.16 9725.98 9735.15 9746.15 9750.02 9757.14 9774.06
 9779.14 9790.13 9798.10 9801.13 9812.13 9823.12 9834.12 9846.18 9856.11 9867.11
 9878.11 9889.10 9894.26 9900.10 9911.09 9919.73 9953.31 9953.3110017.9410017.94
10058.7810062.5510109.0310120.0310134.6810153.0210158.7210175.0110186.0110197.00
10206.8010208.0010218.9910229.9910251.9810262.9810273.9810278.9210284.9710295.97
10317.9610327.0110339.9610350.9510368.33
 1889.55 1889.37 1887.98 1886.74 1885.63 1884.59 1883.91 1883.70 1883.61 1883.78
 1883.92 1883.51 1881.55 1880.47 1875.58 1870.37 1867.70 1859.54 1853.97 1854.09
 1856.25 1857.48 1857.21 1857.03 1856.48 1856.18 1855.96 1855.96 1855.55 1855.55
 1855.29 1855.48 1855.29 1855.15 1855.18 1855.32 1855.44 1855.87 1856.33 1857.37
 1861.42 1861.78 1866.49 1872.79 1875.89 1878.06 1879.74 1880.23 1880.60 1880.99
 1880.94 1881.08 1881.58 1883.06 1886.35
  889.55  889.37  887.98  886.74  885.63  884.59  883.91  883.70  883.61  883.78
  883.92  883.51  881.55  880.47  875.58  870.37  867.70  859.54  853.97  854.09
  856.25  857.48  857.21  857.03  856.48  856.18  855.96 1851.96 1851.55  855.55
  855.29  855.48  855.29  855.15  855.18  855.32  855.44  855.87  856.33  857.37
  861.42  861.78  866.49  872.79  875.89  878.06  879.74  880.23  880.60  880.99
  880.94  881.08  881.58  883.06  886.35
BR Coef=-1 , 0 , 0 ,, 0 ,,,0.8,0,1,0,
WSPro=,,,, 1 ,,,, 0 ,,,, 0 ,,,,-1 ,-1 ,-1 , 0 , 0 , 0 , 0 , 0
BC Design=,, 0 ,, 0 ,,,,,,

Type RM Length L Ch R = 1 , 13209.7,142.154200,142.154200,142.154200
XS GIS Cut Line= 2
699192.190828264774960.581182837699493.579717159774321.692293942
#Sta/Elev= 30
9668.9111875.1779686.139 1875.139697.1961873.2869708.2531868.909 9719.311866.672
9741.4231867.0069763.5371869.6379774.594 1873.099807.7641878.2289818.8211876.642
9829.8781872.8829851.9921856.8519874.1051848.9669896.2191848.6469940.4461844.259
9951.5031842.462 9962.56 1838.5810006.791835.53210017.841836.113 10028.91839.001
10039.961847.20710051.011851.58410062.071853.86410117.361853.00710250.041861.862
10283.211860.32510294.271862.09910308.331861.76310349.551865.76310375.321866.463
#Mann= 3 , 0 , 0
9668.911  0.0883       09668.911  0.0883       010375.32  0.0883       0
#XS Ineff= 2 , 0
       09901.009        10070.12       0
Bank Sta=9668.911,10375.32
Exp/Cntr=0.3,0.1

Type RM Length L Ch R = 1 ,13067.55,240.505500,240.505500,240.505500
XS GIS Cut Line= 6
699321.868882537775073.829444066699400.444017112774887.982585073
699478.921736419774678.889985338699536.909460753774476.036576599
699563.840107411774398.553232342699590.348373324774334.554420963
#Sta/Elev= 30
9612.6771918.749 9644.211908.1169655.1481902.1979694.4461907.0129709.8391905.789
9720.7411902.4919742.2871899.1269796.1511883.3559849.5871862.7349870.8731857.011
9892.1591853.3179924.088 1842.689934.7311840.5839977.6051838.0049988.3681835.186
9999.159 1835.0610020.581836.15710052.281844.24810104.291845.41210197.891852.837
 10260.51855.50110271.091857.31310292.261866.98810302.851868.91410324.021869.688
10334.691874.97810345.521884.62210367.161887.33110386.141893.21210400.121894.758
#Mann= 3 , 0 , 0
9612.677  0.0471       09612.677  0.0471       010400.12  0.0471       0
#XS Ineff= 2 , 0
       0                               0
Bank Sta=9612.677,10400.12
Exp/Cntr=0.3,0.1

Type RM Length L Ch R = 1 ,12827.04,240.505500,240.505500,240.505500
XS GIS Cut Line= 6
699547.367326719775064.253644135699664.505788112774798.220611417
 699722.70303078774715.256941539699752.607593896774658.127211057
699787.825528081774564.973259499 699829.56712464774425.758750992
#Sta/Elev= 30
9649.0651950.0319670.0341940.2029702.707 1921.18 9746.271889.4579757.1611883.604
9778.9431875.4989800.7251869.0929833.3981861.7249866.1721856.9699888.2131852.118
9910.2541848.3779943.4791845.3599955.009 1842.839966.5391838.7759978.0681835.811
10011.391835.31610029.591836.31310041.471838.31310053.271841.481 10072.71844.093
 10088.51848.43610109.371849.20210141.791853.66510152.59  1858.110173.811861.199
10194.991866.50210268.221887.15610320.421888.01310330.861893.91710350.95 1912.56
#Mann= 3 , 0 , 0
9649.065  0.0478       09649.065  0.0478       010350.95  0.0478       0
#XS Ineff= 2 , 0
       0                               0
Bank Sta=9649.065,10350.95
Exp/Cntr=0.3,0.1

Type RM Length L Ch R = 1 ,12586.54,240.505500,240.505500,240.505500
XS GIS Cut Line= 6
 699760.80455095775229.616438095699852.720625888774967.067744593
699892.052320841774878.864215858699902.055475591774849.481526669
699910.253056965774808.697947516699945.384379874774556.737548176
#Sta/Elev= 30
9649.0251974.9739719.8761952.787 9760.221938.5469802.5131929.3149887.1011914.502
9897.6741908.2899929.4371878.4229940.2181863.7499950.998 1846.629972.559 1837.73
10007.481835.32410038.511836.65410049.081838.59910059.481844.37710069.681845.648
10110.311847.53210130.471853.65110140.541859.47510180.861864.09210221.171880.724
10231.251886.72210241.341891.07510251.46 1897.9610261.591901.76410284.081901.548
10291.951904.05310302.081910.46610322.321920.24110332.451924.09210350.931927.112
#Mann= 3 , 0 , 0
9649.025    0.04       09649.025    0.04       010350.93    0.04       0
#XS Ineff= 2 , 0
       0                               0
Bank Sta=9649.025,10350.93
Exp/Cntr=0.3,0.1

Type RM Length L Ch R = 1 ,12346.03,100.102700,100.102700,100.102700
XS GIS Cut Line= 5
 700087.65139094775006.914471954700105.195195794774906.914784431
700099.932054281774833.815597668700080.049075514774765.394758821
700035.019976407774664.225484312
#Sta/Elev= 30
9809.4261875.7739811.3691875.2829821.5221870.4459831.6751867.3429841.8271863.758
 9851.981858.8779862.1331856.1769872.286 1856.739882.4381858.3149892.5911861.183
9910.9521860.5899912.8721860.7549932.924 1857.32 9942.951851.9699952.9761843.236
9963.0021836.7739973.028 1836.0910014.251836.02910035.081836.10610045.491837.123
10055.921843.28510066.871852.00310077.821852.85410088.761856.62610099.711859.197
10110.651863.30410117.091867.754 10121.61871.76510141.691886.23410166.231901.655
#Mann= 3 , 0 , 0
9809.426  0.0528       09809.426  0.0528       010166.23  0.0528       0
#XS Ineff= 2 , 0
       0                               0
Bank Sta=9809.426,10166.23
Exp/Cntr=0.3,0.1

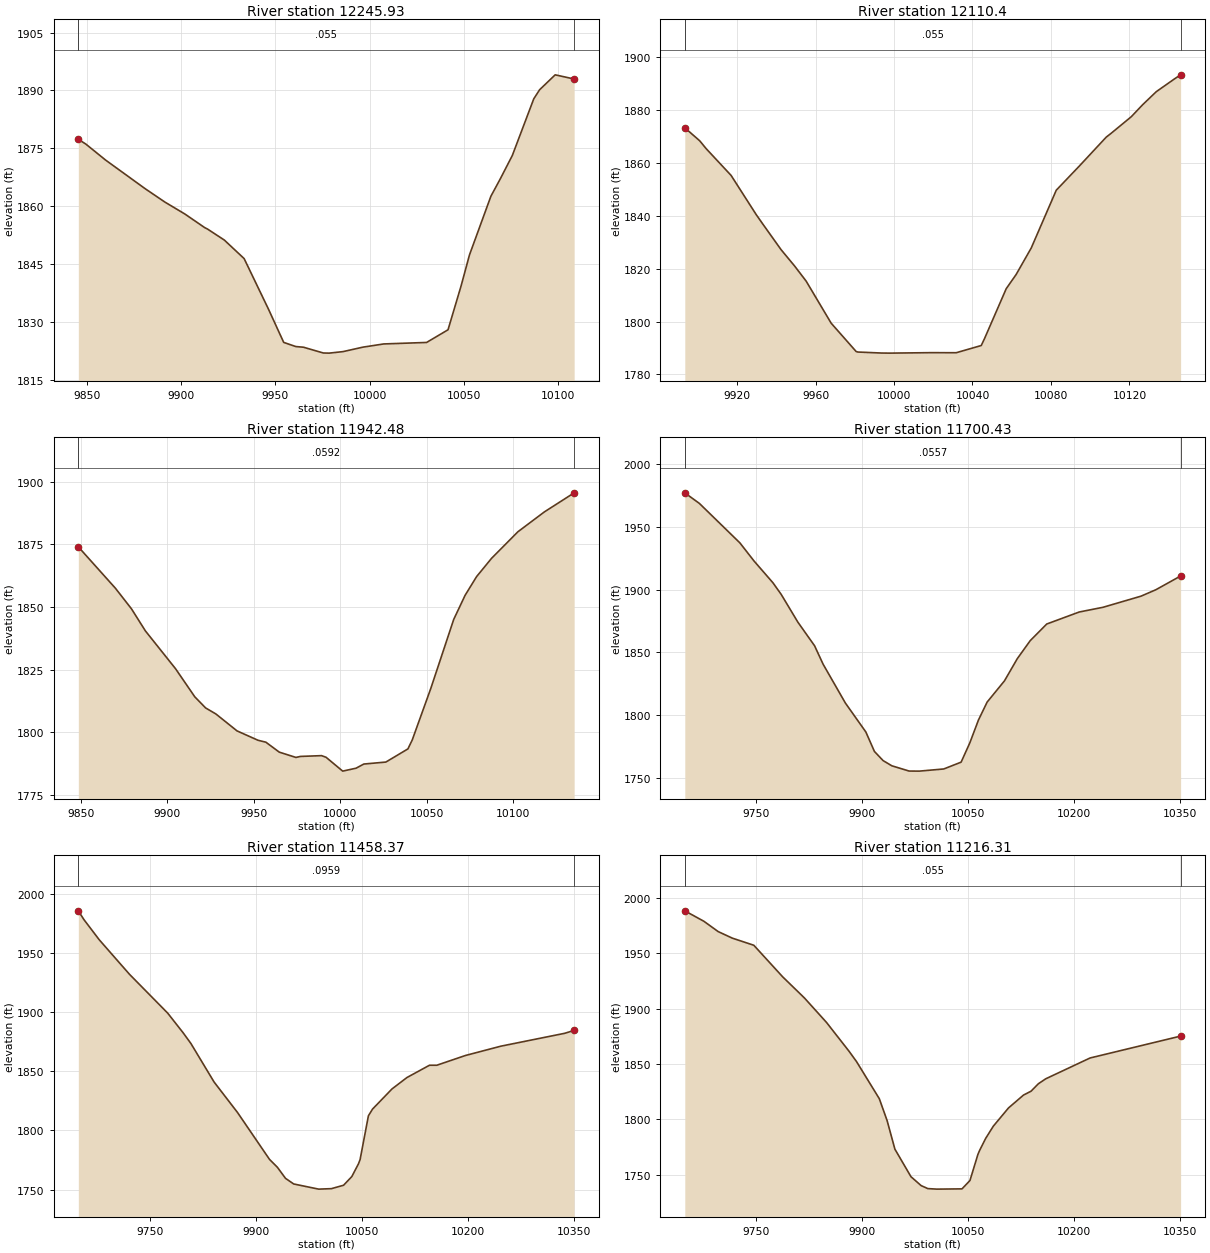
Type RM Length L Ch R = 1 ,12245.93,135.526100,135.526100,135.526100
XS GIS Cut Line= 4
700143.791566342774978.844384223700179.463969499774868.903207317
 700191.74463287774831.476423681700243.791253865774736.155084118
#Sta/Elev= 30
9845.209 1877.359849.2511876.0819859.7641871.9399880.7911864.5239891.3041861.052
9901.8171857.992 9912.331854.4799913.9281854.0729922.8441851.2279933.3571846.427
9946.3291833.2959954.3831824.7199960.7931823.6459964.9011823.4689975.4261821.978
 9978.551821.939 9985.951822.3329996.4751823.48610007.561824.31810030.351824.705
10041.741827.98810048.711839.39810053.14 1847.3810064.531862.59210069.581867.144
10075.921873.14810087.321887.82610090.441890.18710098.711894.04510108.791892.961
#Mann= 3 , 0 , 0
9845.209   0.055       09845.209   0.055       010108.79   0.055       0
#XS Ineff= 2 , 0
       0                               0
Bank Sta=9845.209,10108.79
Exp/Cntr=0.3,0.1

Type RM Length L Ch R = 1 , 12110.4,167.917700,167.917700,167.917700
XS GIS Cut Line= 2
700240.282492906774983.522732198700397.007149369774785.277737617
#Sta/Elev= 30
9893.3671873.3429900.9731868.4239904.2311865.4739916.9791855.3099929.7261840.536
9933.2231836.8219942.4741827.1949949.3471821.0349955.2211815.3229967.9681799.412
9980.7161788.6789981.5971788.4949993.4631788.1169997.721 1788.0810018.961788.257
10031.711788.23110044.451790.955 10046.11793.521 10057.21812.47510062.221817.803
10069.951827.868 10082.71849.73310094.471858.88410108.191869.82610110.591871.209
10120.941877.54310126.721882.06610133.691887.01810142.841891.78710146.081893.384
#Mann= 3 , 0 , 0
9893.367   0.055       09893.367   0.055       010146.08   0.055       0
#XS Ineff= 2 , 0
       0                               0
Bank Sta=9893.367,10146.08
Exp/Cntr=0.3,0.1

Type RM Length L Ch R = 1 ,11942.48,242.056600,242.056600,242.056600
XS GIS Cut Line= 3
700362.704465151775110.132750949700464.093354075 774965.68830645
700536.315576316 774882.35497314
#Sta/Elev= 30
9848.4941873.9849869.8951857.506  9879.2 1849.289887.3011840.4219904.7071825.357
9915.8531814.1329922.1131809.698 9928.071807.2839940.2881800.5279952.5061796.772
9956.925 1796.049964.7231792.0499974.3311789.9499976.9411790.3459989.1581790.657
9991.737 1790.0210001.381784.47910009.141785.65510013.591787.30410026.351788.096
10039.111793.35110041.621796.94510052.351817.51110065.581845.00910072.16 1854.63
10078.811862.10410087.431869.372 10102.71879.99610117.971887.90510135.241895.545
#Mann= 3 , 0 , 0
9848.494  0.0592       09848.494  0.0592       010135.24  0.0592       0
#XS Ineff= 2 , 0
       0                               0
Bank Sta=9848.494,10135.24
Exp/Cntr=0.3,0.1

Type RM Length L Ch R = 1 ,11700.43,242.056500,242.056500,242.056500
XS GIS Cut Line= 6
700436.914722251775443.065642392700529.203319559775286.830920573
700722.626462684775007.563869057700749.533810891774958.429930678
700768.542833396774915.109894481 700791.14762306774841.197891191
#Sta/Elev= 30
9649.0191976.8749669.7281968.4289727.0441937.0859746.9431922.7519773.7691905.414
9785.5521896.1069809.1171874.0699832.7411855.3389844.8431840.6639876.3271809.839
9905.3531786.7929917.4821771.328 9929.751764.0759942.0181759.9589966.5531755.767
9980.9921755.70210015.641757.416 10040.21762.84210052.481778.10110064.76 1796.34
10077.041810.57210101.591827.46410119.681845.036   101381859.377 10161.41872.609
10207.411882.16310240.961885.89210294.971894.76510315.871899.84910350.941910.785
#Mann= 3 , 0 , 0
9649.019  0.0557       09649.019  0.0557       010350.94  0.0557       0
#XS Ineff= 2 , 0
       0                               0
Bank Sta=9649.019,10350.94
Exp/Cntr=0.3,0.1

Type RM Length L Ch R = 1 ,11458.37,242.056600,242.056600,242.056600
XS GIS Cut Line= 6
700681.309799124775592.389146698700764.712427181775393.616782222
700862.705437152 775224.39670908700889.994036527775162.371775622
700906.681197144775065.975355268700901.995195474774941.476810242
#Sta/Elev= 30
9649.0451985.6659656.9871978.2399678.4811961.3179721.4711932.0049775.4821899.239
9797.3991882.5639808.3571873.5489841.2311840.933 9874.411815.1669919.6551775.556
9930.9671768.7789942.2781759.5479953.872 1754.789989.1941750.41610007.211750.812
10024.44 1753.6810036.171761.04310045.551771.77810047.891775.41610059.611812.293
10060.321813.06610065.511818.08810093.081835.12610114.181844.74210146.091855.135
10156.41 1855.1310197.011863.38610247.191871.26210337.321882.10810350.871884.586
#Mann= 3 , 0 , 0
9649.045  0.0959       09649.045  0.0959       010350.87  0.0959       0
#XS Ineff= 2 , 0
       0                               0
Bank Sta=9649.045,10350.87
Exp/Cntr=0.3,0.1

Type RM Length L Ch R = 1 ,11216.31,242.056600,242.056600,242.056600
XS GIS Cut Line= 6
701153.016585378 775661.89339012701136.990759559775544.105370231
 701112.33081513775450.457693667701078.708154169775369.103881601
 701007.41863497775245.143713707700937.542171829775000.700358595
#Sta/Elev= 30
9649.0841988.2239676.1431978.7899696.2661969.5119716.3891963.567  9746.81957.152
9787.6411928.6579818.461 1909.589849.7111887.4979881.3951861.6779892.0671852.295
9924.4431818.6879935.4671798.945 9946.491773.1779969.2651748.2959983.5841740.288
9993.0881737.57210005.841737.092 10041.51737.32810052.751744.876   100641768.404
10066.24 1771.7710074.941782.82410085.821793.90410107.311810.34710128.561821.973
10139.191825.44310149.681832.22110160.141836.67610222.761855.42410350.961875.184
#Mann= 3 , 0 , 0
9649.084   0.055       09649.084   0.055       010350.96   0.055       0
#XS Ineff= 2 , 0
       0                               0
Bank Sta=9649.084,10350.96
Exp/Cntr=0.3,0.1

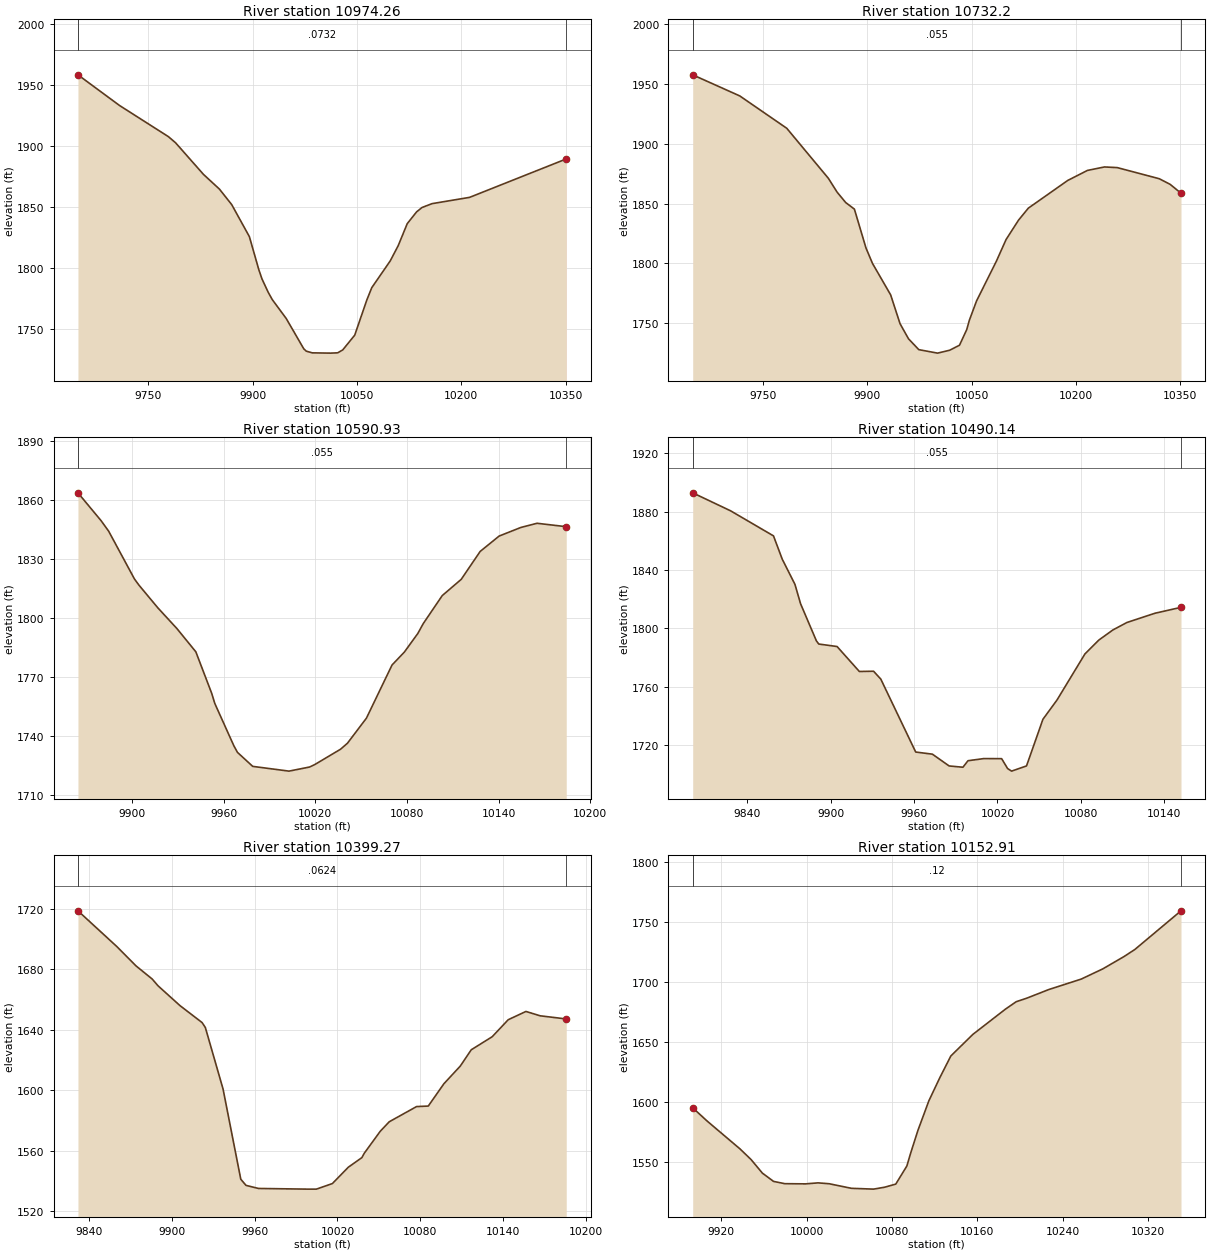
Type RM Length L Ch R = 1 ,10974.26,242.056500,242.056500,242.056500
XS GIS Cut Line= 6
701423.266415953775408.792379902701327.173905949775251.046109632
 701256.62087711775181.427387573701070.170100231775036.552552048
 701020.94494234774975.433037881700972.600866931774885.621771674
#Sta/Elev= 30
9649.0821958.3539708.7521933.2739779.0431907.7339789.3241902.7489829.5141876.786
9852.4011864.777 9870.111852.0219895.4751825.8339908.9591798.9219913.5081791.313
9922.4431780.3359928.4151774.2279948.4191758.7749973.681 1733.929977.2461732.016
9985.8271730.63610012.371730.40610022.411730.65710029.691733.053 10046.91745.134
10064.35 1774.0410071.391784.01410097.941805.96910109.351818.37810122.341836.423
10135.811846.09510143.631849.68810158.061852.84110211.96 1857.9810350.911889.454
#Mann= 3 , 0 , 0
9649.082  0.0732       09649.082  0.0732       010350.91  0.0732       0
#XS Ineff= 2 , 0
       0                               0
Bank Sta=9649.082,10350.91
Exp/Cntr=0.3,0.1

Type RM Length L Ch R = 1 , 10732.2,141.269200,141.269200,141.269200
XS GIS Cut Line= 6
701565.140303308775268.397531653701516.325758646 775153.93970921
701454.478874567775063.480047763701369.037364128774966.383023787
701202.524024623774799.855299704701134.993551691774722.462076104
#Sta/Elev= 30
9649.0581957.4689716.7031939.8559784.2621912.8359844.057 1871.089856.5321859.585
9869.0071850.8099881.4831845.3359898.1251812.9089907.5031799.9959933.6121773.733
9947.0931749.6899959.2381737.0829974.063 1727.9910001.031725.08510018.451727.505
10032.591731.69210042.981744.75210046.731752.51710057.121768.712 10085.41801.611
10099.541819.95410117.451836.14310131.591846.17110188.16 1869.2710216.451877.633
10240.961880.54310259.381879.98710319.681870.72210335.321866.04610350.981858.626
#Mann= 3 , 0 , 0
9649.058   0.055       09649.058   0.055       010350.98   0.055       0
#XS Ineff= 2 , 0
       0                               0
Bank Sta=9649.058,10350.98
Exp/Cntr=0.3,0.1

Type RM Length L Ch R = 1 ,10590.93,100.787400,100.787400,100.787400
XS GIS Cut Line= 2
701587.189310193774956.926218882701329.585789889774767.368911475
#Sta/Elev= 30
9864.5431863.5399879.6771849.4319884.6661844.0699901.538 1819.859904.5081816.697
9916.9241805.1469929.3391794.6999941.7551782.8869952.1561761.7929954.171  1756.7
9966.5861735.3349969.0281731.8619979.002 1724.7610002.771722.34810016.25 1724.43
10019.651725.67510036.521733.44910041.081736.517 10053.5 1749.2310070.261776.182
10078.331782.74210087.141792.16810090.74 1797.2310103.16 1811.4110115.571819.636
10127.991833.808 10140.41841.59810154.631845.96710165.24 1848.0910184.371846.367
#Mann= 3 , 0 , 0
9864.543   0.055       09864.543   0.055       010184.37   0.055       0
#XS Ineff= 2 , 0
       0                               0
Bank Sta=9864.543,10184.37
Exp/Cntr=0.3,0.1

Type RM Length L Ch R = 1 ,10490.14,90.869700,90.869700,90.869700
XS GIS Cut Line= 6
701674.092658877774932.638478518701567.378675699774841.885988519
  701537.2798599774796.737764865701517.213982731774771.655418381
701506.725001484774762.990607783701396.362676948 774750.22141321
#Sta/Elev= 30
9800.8541892.866 9828.081880.5499858.9521863.3629865.2981847.3019874.3881830.144
9878.4261816.8719889.8241791.3939891.5531789.234 9904.681787.5419920.6961770.439
9930.934  1770.69936.1321765.2119961.2331715.2339973.2521713.768 9985.271705.693
  9995.21704.814 9998.851709.28310010.231710.74510023.041710.68810027.321703.928
10030.191702.14910040.931705.71110052.731737.672 10062.81750.80910082.931782.438
   100931792.01110103.06  1798.910113.131804.00510133.261810.33310152.031814.398
#Mann= 3 , 0 , 0
9800.854   0.055       09800.854   0.055       010152.03   0.055       0
#XS Ineff= 2 , 0
       09958.211        10040.92       0
Bank Sta=9800.854,10152.03
Exp/Cntr=0.3,0.1

Type RM Length L Ch R = 1 ,10399.27,246.368500,246.368500,246.368500
XS GIS Cut Line= 3
701691.422280073774836.869519234701604.318131387774728.787408054
701418.708767444774620.249254212
#Sta/Elev= 30
9831.929 1718.729860.017 1695.179874.037 1682.289885.7031673.6419889.9731669.133
9905.9091656.0099921.8461644.8639924.2331641.5929937.0761600.8929949.9191541.249
9953.7191537.1729962.7631535.1439998.0551534.702 10004.71534.70610016.291538.378
10027.871549.20710037.671555.53510039.461558.51310051.041573.01410057.481579.231
10077.29 1589.2810085.791589.632 10097.11604.37710108.961616.03810116.911626.826
10132.131635.49510143.721646.71910156.541652.18710166.881649.30410185.761647.226
#Mann= 3 , 0 , 0
9831.929  0.0624       09831.929  0.0624       010185.76  0.0624       0
#XS Ineff= 2 , 0
       0  9936.2         10037.1       0
Bank Sta=9831.929,10185.76
Exp/Cntr=0.3,0.1

Type RM Length L Ch R = 1 ,10152.91,246.368600,246.368600,246.368600
XS GIS Cut Line= 6
701777.384803534774648.367994776 701773.62138067774614.731500111
701754.712818672774556.620595307701710.978007876774394.811018616
701692.585578055774292.973827914701682.582857171774202.056166145
#Sta/Elev= 30
9893.2091594.9049906.6331583.9179937.4551560.6969947.9711551.7179958.4871540.466
9969.0031533.5379979.5191531.644    99991531.48210010.681532.318 10021.11531.592
10041.921527.78310062.741527.09910073.151528.69910083.561531.29510093.98 1546.42
10097.421556.85210104.291575.97210114.591600.73810124.891620.05910135.191638.088
10155.791656.05110186.281677.06910196.441683.309 10206.61686.34910226.92 1693.44
10257.411702.18210277.551710.65410297.671721.03110307.731726.89710350.931759.076
#Mann= 3 , 0 , 0
9893.209    0.12       09893.209    0.12       010350.93    0.12       0
#XS Ineff= 2 , 0
       0                               0
Bank Sta=9893.209,10350.93
Exp/Cntr=0.3,0.1