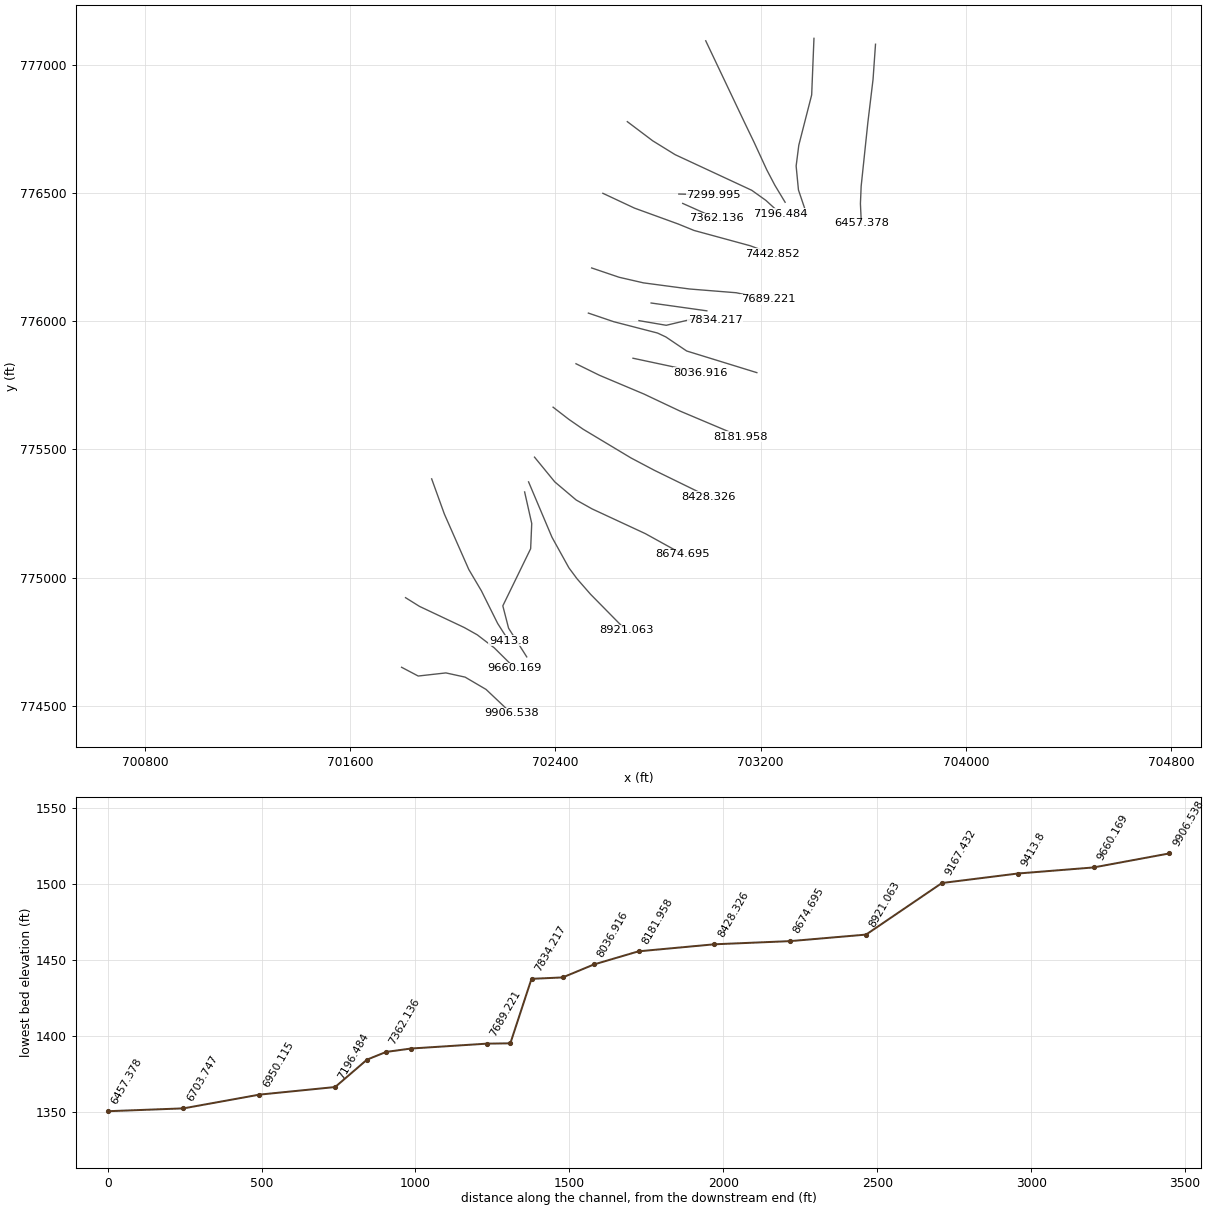
HEC-RAS study 14441_ras.prj: 14441

--- 14441_ras.g01 (geometry) --- (continued)

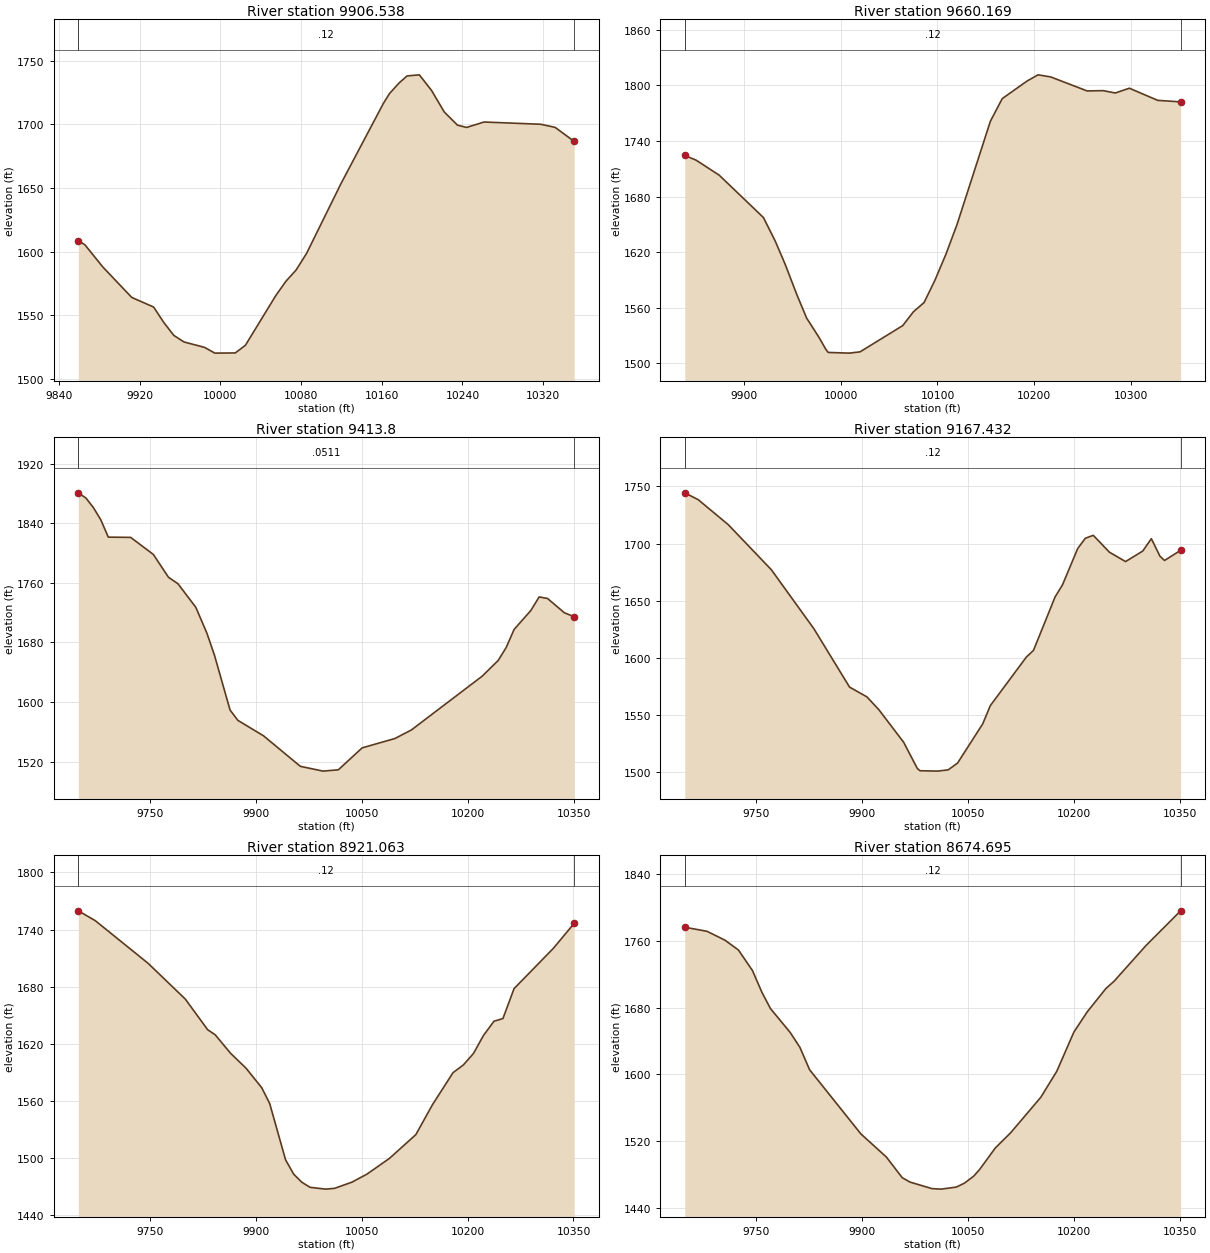
Type RM Length L Ch R = 1 ,9906.538,246.368500,246.368500,246.368500
XS GIS Cut Line= 6
701799.998835058774650.441942122701864.849332971774616.320228159
701972.849189714774628.481862174702047.661746885774612.045558853
702129.389708961774564.095558018702228.137309786774470.685029263
#Sta/Elev= 30
  9859.31608.7959865.8341605.441 9883.561588.0459912.2431564.1079933.9521556.565
9943.9531544.4959953.9531534.2859964.0571529.1359984.4341524.8769994.6231520.366
 10014.91520.51810024.921526.55210055.041565.59810065.111576.86110075.181585.687
10085.531598.70710119.711653.62210161.491716.25410167.671724.19110177.531732.791
10185.18  1738.110197.271738.96610209.371726.74810222.041709.74410235.171699.403
10244.161697.64610261.43  1701.910317.631700.13610331.941697.67410350.751686.669
#Mann= 3 , 0 , 0
  9859.3    0.12       0  9859.3    0.12       010350.75    0.12       0
#XS Ineff= 2 , 0
       0                               0
Bank Sta=9859.3,10350.75
Exp/Cntr=0.3,0.1

Type RM Length L Ch R = 1 ,9660.169,246.368600,246.368600,246.368600
XS GIS Cut Line= 6
701815.420249999774921.860515708701869.807636516774887.916208196
 702044.38130925774805.441793346702095.020666645774777.034112323
702161.248116121 774726.30676837702241.395977863774646.926994045
#Sta/Elev= 30
9839.2691724.4279850.9631719.3399874.7441703.1679920.3931657.453 9932.611631.952
  9942.71607.3749955.1881573.4799965.0071548.9099977.7661528.1189984.7981515.289
9987.263 1511.8710009.141511.12110020.151512.518 10064.21540.84810075.211555.768
10086.221565.75410097.26 1589.4610108.721617.79910120.191649.87410154.591761.282
10166.871785.78110192.551804.76910203.831811.42310216.891809.13910254.521794.016
10270.851794.36610283.571791.82710298.071796.96610327.291783.86710350.931782.255
#Mann= 3 , 0 , 0
9839.269    0.12       09839.269    0.12       010350.93    0.12       0
#XS Ineff= 2 , 0
       0                               0
Bank Sta=9839.269,10350.93
Exp/Cntr=0.3,0.1

Type RM Length L Ch R = 1 ,  9413.8,246.368500,246.368500,246.368500
XS GIS Cut Line= 6
701917.287150941775385.191264402701966.706236093775248.218143605
702062.145895032775031.653332941702111.311284979774948.400367434
702174.645641804774821.217399035702218.156948552774753.300103062
#Sta/Elev= 30
9649.0271880.9959659.783 1873.989670.3371861.1629680.8911844.6579691.4461821.473
9723.1081821.1319755.2241798.1929776.6771767.5119789.9631758.948 9815.291727.275
9830.9641692.6439841.8881662.3629863.807  1589.29874.8821575.3279911.1261554.581
9963.3181513.5479995.5951507.11410017.09 1508.9110050.781538.32710097.231550.955
10120.46 1562.4110220.691634.67310243.321655.73410254.63  1673.110265.951697.561
10289.491722.77210301.371741.15310313.241739.03110336.991719.91310350.891714.555
#Mann= 3 , 0 , 0
9649.027  0.0511       09649.027  0.0511       010350.89  0.0511       0
#XS Ineff= 2 , 0
       0                               0
Bank Sta=9649.027,10350.89
Exp/Cntr=0.3,0.1

Type RM Length L Ch R = 1 ,9167.432,246.368600,246.368600,246.368600
XS GIS Cut Line= 6
702279.787614886775334.183976872702307.510661704 775211.09901441
 702303.26356627775112.789880852702194.757302428774889.959609386
702217.240158845774802.796182055702287.969123902774690.984755015
#Sta/Elev= 30
9649.2651744.3389668.1711738.3859710.8351716.4319771.7141677.0419831.8261625.501
9882.3461574.3819907.0091565.7829923.9051554.5269958.9271526.0619978.2051503.219
9981.949 1501.2110006.561500.85410021.921501.96610035.191507.92410070.71 1542.16
10081.481558.13510132.551600.70410142.591606.51910173.141653.28810183.561663.762
10205.091695.56410215.871704.57610227.151707.156   102501692.39510272.84  1684.2
10297.131693.39410309.311704.21310321.481688.89610327.991685.15710350.721694.041
#Mann= 3 , 0 , 0
9649.265    0.12       09649.265    0.12       010350.72    0.12       0
#XS Ineff= 2 , 0
       0                               0
Bank Sta=9649.265,10350.72
Exp/Cntr=0.3,0.1

Type RM Length L Ch R = 1 ,8921.063,246.368500,246.368500,246.368500
XS GIS Cut Line= 6
702295.157970424 775373.38444839702386.403415971775157.557602112
 702452.49467447775038.189201955702484.143146289774995.548097437
702536.830638206774935.146990271702675.588597667774794.214236486
#Sta/Elev= 30
9649.0361759.6479673.0411749.2919747.7711704.4629800.536 1666.77 9832.121634.567
9842.9261629.1669864.539 1609.799886.2581594.2729908.6981573.5359919.9181556.981
 9942.431497.6829953.9531482.5469965.4761474.1239976.9991468.801    9999 1466.88
10011.86 1467.7210036.331474.19610057.661482.65410089.521499.25510126.811524.187
10150.371555.66810179.481589.40410193.961597.40510208.451609.60810222.471628.391
10237.421643.46510250.131646.32610265.881677.78410321.351720.06410350.961746.418
#Mann= 3 , 0 , 0
9649.036    0.12       09649.036    0.12       010350.96    0.12       0
#XS Ineff= 2 , 0
       0                               0
Bank Sta=9649.036,10350.96
Exp/Cntr=0.3,0.1

Type RM Length L Ch R = 1 ,8674.695,246.368600,246.368600,246.368600
XS GIS Cut Line= 6
702318.345147928775469.848044138 702397.28433938775373.446000138
702480.826068083775302.724676641702542.783624903775268.057897703
702750.359093053775171.645188169702897.106040656775090.594360657
#Sta/Elev= 30
9649.0861776.3649680.5821771.4689705.9341760.8559725.0081749.0869744.9231724.387
9758.2951698.3229770.3041678.9749798.1721650.4039811.9611632.563 9825.751605.634
9898.3591528.7339934.414 1501.089956.8741476.2999967.9361470.998    99991463.196
10012.041462.58110033.491465.04410044.871469.69510058.141478.18710066.751486.431
10088.631511.86910110.531530.23210153.011572.57810175.711603.81510199.921650.787
10218.75 1674.9210245.231702.94110256.561711.45610301.591754.08910350.99 1796.01
#Mann= 3 , 0 , 0
9649.086    0.12       09649.086    0.12       010350.99    0.12       0
#XS Ineff= 2 , 0
       0                               0
Bank Sta=9649.086,10350.99
Exp/Cntr=0.3,0.1

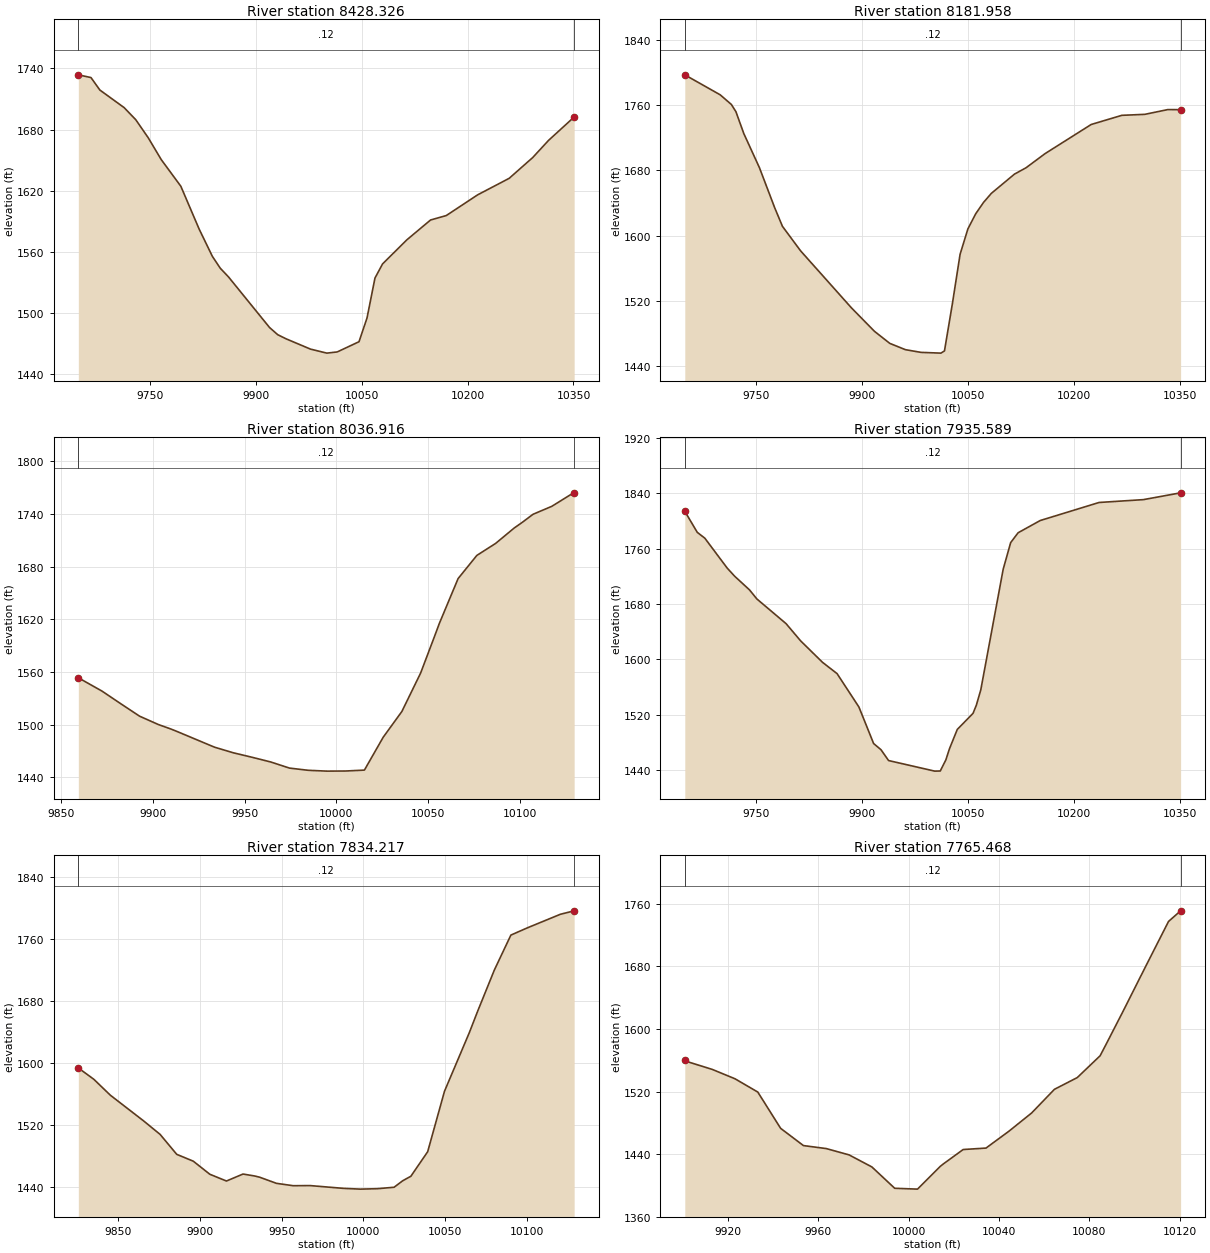
Type RM Length L Ch R = 1 ,8428.326,246.368500,246.368500,246.368500
XS GIS Cut Line= 6
702390.830971842775664.579074431702452.068155136775617.328027437
702507.820766804775578.752874423702694.302119753775466.851576539
702784.974701467775418.872922354702997.643600624775314.886457507
#Sta/Elev= 30
9649.0231733.7719666.9191731.081 9679.551718.8119713.8121701.6149730.4621689.601
9748.0371671.9069766.4161650.5159794.1671624.3349820.0171582.3799838.8141555.491
9849.8861543.9359861.6971535.2719919.805 1485.589931.3871478.557 9942.971474.591
9977.7181464.42810000.891460.48710015.631461.674 10046.4 1471.6910057.721494.981
10069.031534.27510079.77 1548.1110114.281571.82910147.681591.21310169.941595.576
10214.471615.96410258.991632.12310292.39 1652.5910314.651669.32710350.991692.349
#Mann= 3 , 0 , 0
9649.023    0.12       09649.023    0.12       010350.99    0.12       0
#XS Ineff= 2 , 0
       0                               0
Bank Sta=9649.023,10350.99
Exp/Cntr=0.3,0.1

Type RM Length L Ch R = 1 ,8181.958,145.042100,145.042100,145.042100
XS GIS Cut Line= 6
702480.044149689775834.067565957702571.691680799775789.012870353
702745.401935546775715.793905999702800.831011701775689.544590433
702884.762619251775649.923277737703121.690561355775549.907615745
#Sta/Elev= 30
9649.0361797.211 9699.131772.7079714.9221760.8939721.4161751.9929732.5591725.223
9754.7491683.2099776.4531633.8599787.3051611.3519812.9831581.3129884.9731511.371
9917.5291482.6359939.233 1467.839961.3541460.0969983.4821456.78110011.651455.859
10016.671458.56610027.731515.73510038.78 1577.1310049.841608.283 10060.91626.787
10071.961640.72910083.021651.81310115.781675.43910132.191683.241 10159.21700.633
10224.331736.27410267.741747.52810300.311748.73810332.871754.57810350.991754.478
#Mann= 3 , 0 , 0
9649.036    0.12       09649.036    0.12       010350.99    0.12       0
#XS Ineff= 2 , 0
       0                               0
Bank Sta=9649.036,10350.99
Exp/Cntr=0.3,0.1

Type RM Length L Ch R = 1 ,8036.916,101.326500,101.326500,101.326500
XS GIS Cut Line= 2
702702.311352938775855.555994943702966.950620562775799.125562876
#Sta/Elev= 30
9859.2011553.4899872.1751538.233  9882.41523.8759892.625 1509.76 9902.851500.268
9909.8181495.0679913.0741492.3349933.5241474.4669943.7491468.0959953.9741462.997
9964.1981457.6259974.4231450.6689984.6481448.1359994.873  1447.2 10005.11447.338
10015.321448.36410025.551485.68310035.771515.116   10046 1558.8410053.671601.045
10056.221615.35910066.451666.38310076.671692.763 10086.91706.39310097.121724.044
10101.621730.63810107.351739.61510117.571748.645 10127.81761.86110129.791764.034
#Mann= 3 , 0 , 0
9859.201    0.12       09859.201    0.12       010129.79    0.12       0
#XS Ineff= 2 , 0
       0                               0
Bank Sta=9859.201,10129.79
Exp/Cntr=0.3,0.1

Type RM Length L Ch R = 1 ,7935.589,101.371800,101.371800,101.371800
XS GIS Cut Line= 6
702528.392419237776031.569225482702627.617411516775997.867381833
702797.968257072775953.802072581702830.611176399 775938.50330247
702911.706166348775883.756703645703185.286913519775799.376642456
#Sta/Elev= 30
9649.1221814.0639666.7941783.6019677.4351775.236  9709.31731.7969719.7751720.153
9740.726 1700.489751.2011687.3319792.479  1651.79813.0961626.8269844.022 1595.86
9864.6391579.5229895.5651531.2979916.3921478.5039926.8281469.5899937.5321453.951
10002.841438.66510010.681438.83410018.621454.95310023.751471.08610034.771498.863
10057.061522.11910061.711533.83310068.011555.88210099.75 1730.3310110.321768.746
 10120.91783.033 10152.21800.69810235.481826.75810298.171830.87110350.881840.704
#Mann= 3 , 0 , 0
9649.122    0.12       09649.122    0.12       010350.88    0.12       0
#XS Ineff= 2 , 0
       0                               0
Bank Sta=9649.122,10350.88
Exp/Cntr=0.3,0.1

Type RM Length L Ch R = 1 ,7834.217,68.749000,68.749000,68.749000
XS GIS Cut Line= 4
702725.661876529776002.145393163702832.036484092775983.983874798
702959.815738291776014.469280645703023.381052613776006.037147105
#Sta/Elev= 30
9825.6081594.1059835.0811579.5229845.2261558.9089865.515 1525.85 9875.661508.338
9885.8051482.6469895.9491473.7999906.0941456.8989916.239 1448.199926.384  1457.2
9933.522 1454.689936.5691453.1119946.8491445.199 9957.131442.1369967.4111442.308
9987.9721438.6929998.2531437.73110008.531438.28410018.811440.13410024.081448.515
10029.091454.33310039.381486.01610049.661563.98610064.891639.83910070.121668.178
 10080.21720.61810090.291765.59510100.381774.95710120.561792.44510129.011796.916
#Mann= 3 , 0 , 0
9825.608    0.12       09825.608    0.12       010129.01    0.12       0
#XS Ineff= 2 , 0
       09928.224                       0
Bank Sta=9825.608,10129.01
Exp/Cntr=0.3,0.1

Type RM Length L Ch R = 1 ,7765.468,76.247700,76.247700,76.247700
XS GIS Cut Line= 2
702773.011549413776070.899712712702990.301144153776040.414306864
#Sta/Elev= 27
9900.9451560.0299902.9531557.4259913.0511548.3439923.1491536.3349933.2471519.348
9943.3451473.0059943.4081472.8519953.443 1450.929963.5411447.0949973.6391439.031
9983.7371423.6049993.8351396.34110003.931395.25110014.031424.42310015.381427.507
10024.13 1445.8810034.231447.72610044.321469.14610054.421492.57310064.521522.847
10074.621537.83810084.721565.69410087.36 1580.2710094.811622.15410104.911680.078
10115.011737.44710120.361751.024
#Mann= 3 , 0 , 0
9900.945    0.12       09900.945    0.12       010120.36    0.12       0
#XS Ineff= 2 , 0
       0                               0
Bank Sta=9900.945,10120.36
Exp/Cntr=0.3,0.1

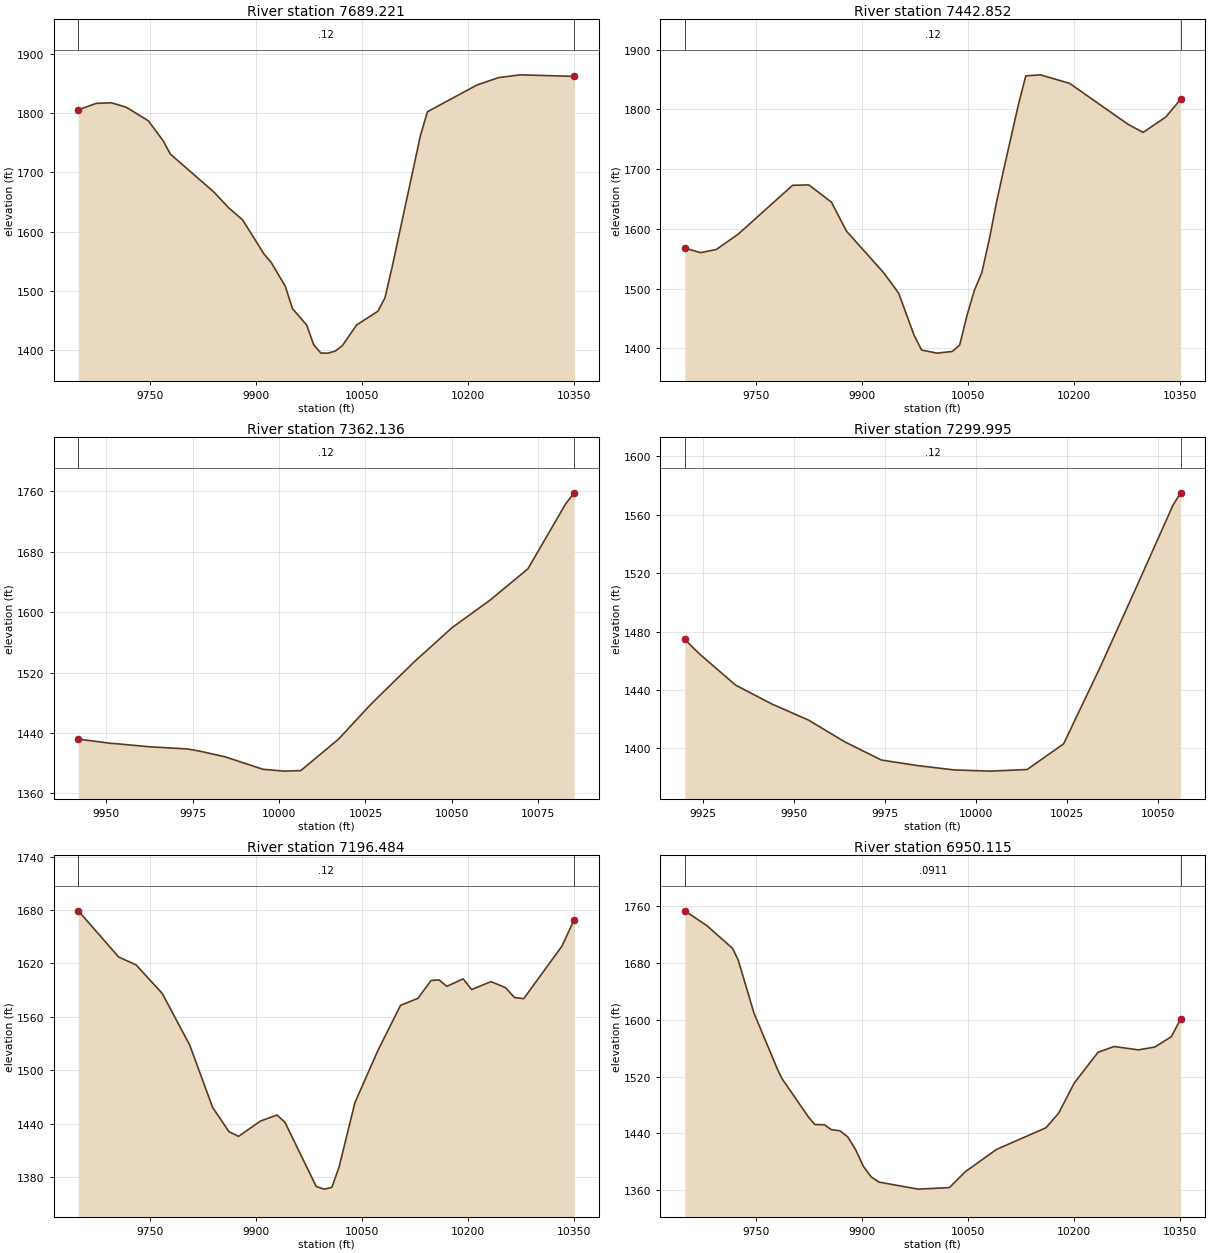
Type RM Length L Ch R = 1 ,7689.221,246.368600,246.368600,246.368600
XS GIS Cut Line= 6
702541.191773442776207.575788958702648.417960333 776171.21606427
702743.123045012776149.454546849 702923.15383012776125.509494419
703105.077048041776110.908034676703229.414141764776084.648867445
#Sta/Elev= 30
 9649.041805.4099674.3781816.2579695.6631817.2869716.9351809.7559748.2841786.732
9769.0921753.1979779.4031730.5819841.016 1666.699861.4021640.6799881.6221619.771
9911.9511562.0349922.022 1548.089942.1051507.6039952.1461470.1549972.2291442.517
 9982.271409.0819992.3771395.122 10002.51395.03610012.651398.47310022.791407.615
10043.071442.64710073.131465.68210083.151488.39410093.17 1539.8610133.251761.594
10143.271802.21510213.63 1847.3910244.011859.72610274.491864.41510350.931861.797
#Mann= 3 , 0 , 0
 9649.04    0.12       0 9649.04    0.12       010350.93    0.12       0
#XS Ineff= 2 , 0
       0                               0
Bank Sta=9649.04,10350.93
Exp/Cntr=0.3,0.1

Type RM Length L Ch R = 1 ,7442.852,80.716300,80.716300,80.716300
XS GIS Cut Line= 6
702584.949240755776498.653942612702708.372475402776440.836364489
 702878.50906561776379.020679674702940.627874678776353.742227909
703159.340407869776294.181483969703244.430247697776262.966304885
#Sta/Elev= 30
9649.0291567.7979671.4471560.0969693.8081565.5429724.7911591.2729801.6731672.954
  9824.6 1673.629856.6671644.7049877.8711596.256 9930.881526.0329948.4051497.811
9952.0841491.3329973.4141422.4859984.2091396.97710006.081391.81610027.521394.595
10038.131405.18210048.591455.25310059.05 1497.1610069.511526.74110079.971581.613
10090.431645.15110100.781700.98410121.451808.71210131.781856.22710152.451857.993
10193.791843.67710276.811774.89510297.931761.60510329.961787.30510350.951817.076
#Mann= 3 , 0 , 0
9649.029    0.12       09649.029    0.12       010350.95    0.12       0
#XS Ineff= 2 , 0
       0                               0
Bank Sta=9649.029,10350.95
Exp/Cntr=0.3,0.1

Type RM Length L Ch R = 1 ,7362.136,62.140500,62.140500,62.140500
XS GIS Cut Line= 2
702896.232013255776459.248037726703027.233152568776400.775426194
#Sta/Elev= 21
9941.9321431.9729951.5331426.2719952.3541426.1259962.4841421.8599973.4351418.968
9976.888 1416.249984.3861408.5529995.3371392.04510001.421389.58510006.291390.257
10017.241432.04610025.961475.15810028.191485.49310039.14 1534.4510050.09 1579.74
10050.491581.08210061.041616.02810071.991657.49910075.031681.31410082.941743.731
10085.39 1758.24
#Mann= 3 , 0 , 0
9941.932    0.12       09941.932    0.12       010085.39    0.12       0
#XS Ineff= 2 , 0
       0                               0
Bank Sta=9941.932,10085.39
Exp/Cntr=0.3,0.1

Type RM Length L Ch R = 1 ,7299.995,103.511700,103.511700,103.511700
XS GIS Cut Line= 2
702881.051623732776495.793419912703017.112892866776492.420000017
#Sta/Elev= 17
9920.0311474.596 9923.981464.8739933.9841443.3319943.9871430.3759952.0421421.553
 9953.991419.4289963.9931404.4789973.9961392.1129983.9991388.2849994.0021385.326
10004.011384.51910014.011385.62310024.011403.16510034.011455.42310044.021510.558
10054.021566.38810056.131574.894
#Mann= 3 , 0 , 0
9920.031    0.12       09920.031    0.12       010056.13    0.12       0
#XS Ineff= 2 , 0
       0                               0
Bank Sta=9920.031,10056.13
Exp/Cntr=0.3,0.1

Type RM Length L Ch R = 1 ,7196.484,246.368600,246.368600,246.368600
XS GIS Cut Line= 6
702680.241775521776778.060092789  702779.4538349776703.244959285
702866.702753631776649.370179098703165.501619272776510.386079685
 703220.63111243776470.990158534703277.761090952776418.880817945
#Sta/Elev= 30
9649.0241679.1739706.1671627.2969730.8391618.3939767.8251586.3679806.7941528.203
9839.1481458.2289862.3251430.9869875.8861425.755 9906.931442.9989930.3021449.706
9941.3991441.7729985.786 1369.429996.883 1366.4610007.961368.42910018.191391.448
10040.521463.51910072.82 1521.7810105.121572.96410129.721580.84110148.431600.934
10159.571601.55110170.711594.32210193.721602.724 10205.81590.74410233.181599.601
10253.781592.86410266.461581.74410279.511580.47110333.651639.49810350.921669.151
#Mann= 3 , 0 , 0
9649.024    0.12       09649.024    0.12       010350.92    0.12       0
#XS Ineff= 2 , 0
       0                               0
Bank Sta=9649.024,10350.92
Exp/Cntr=0.3,0.1

Type RM Length L Ch R = 1 ,6950.115,246.368500,246.368500,246.368500
XS GIS Cut Line= 6
702985.988387263777093.377259355703136.997339759 776775.43461538
703174.718122598776697.200148626703224.075109395776590.058952815
703255.606878188776530.044671206703295.542748572776463.804039637
#Sta/Elev= 30
9649.0161753.8399680.4351732.8349716.5981700.9489724.7241684.1619746.8681609.903
9780.0841530.7729786.4841517.4669824.3721462.7379833.0741452.5379846.5161452.257
9856.3691445.358 9868.661443.7279879.7331435.0929890.8051417.1489901.8771393.508
9912.9491378.6439924.021 1371.339979.3811361.43910023.691363.60110045.891385.822
10090.281417.42110160.23 1447.9110178.361468.67210200.381511.03910234.121554.445
10256.721562.52410291.181557.80110314.531561.81610337.88 1576.3710350.961601.476
#Mann= 3 , 0 , 0
9649.016  0.0911       09649.016  0.0911       010350.96  0.0911       0
#XS Ineff= 2 , 0
       0                               0
Bank Sta=9649.016,10350.96
Exp/Cntr=0.3,0.1

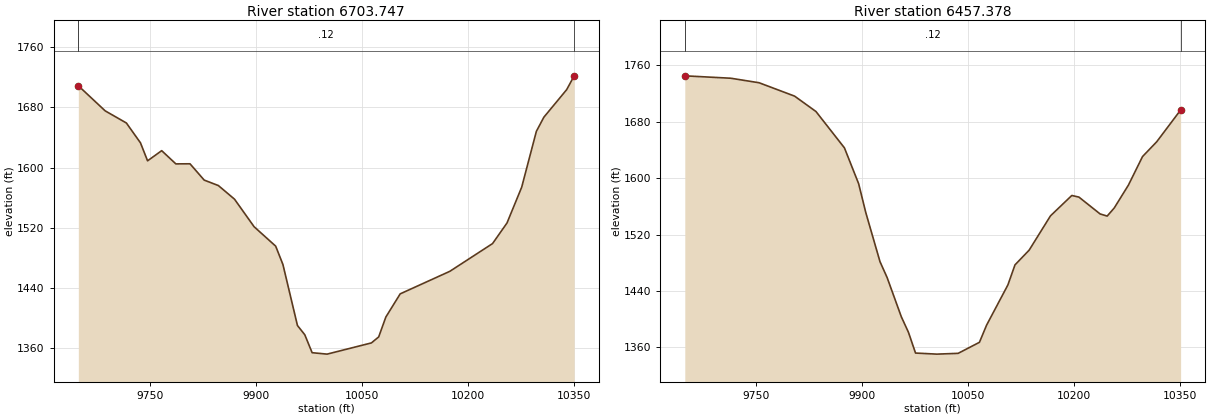
Type RM Length L Ch R = 1 ,6703.747,246.368600,246.368600,246.368600
XS GIS Cut Line= 6
703408.033512979 777102.96774561703399.106506465776882.342424662
703348.936989747776686.385843407703338.512981181776605.068733709
703347.553614189776511.777823854703380.238284012776415.184555428
#Sta/Elev= 30
9649.0351708.5569687.0141675.2649717.0221659.1589737.0271632.7629747.0291608.935
9767.033 1622.419787.0721604.8669807.1171604.9929827.1941583.3579847.3261576.084
9870.133    15589897.8541521.4729928.4061495.6739938.6491471.3249959.2031390.408
9969.5961378.098 9979.991354.28710001.171352.40210063.871367.28210074.191375.233
10084.341401.64510104.641432.38510174.941462.31810235.361499.11410255.811526.442
10276.591573.89510297.381648.05910308.021666.852 10340.31703.42310350.871721.734
#Mann= 3 , 0 , 0
9649.035    0.12       09649.035    0.12       010350.87    0.12       0
#XS Ineff= 2 , 0
       0                               0
Bank Sta=9649.035,10350.87
Exp/Cntr=0.3,0.1

Type RM Length L Ch R = 1 ,6457.378,246.368500,246.368500,246.368500
XS GIS Cut Line= 6
703648.072737806777079.979913161703638.351621377776942.125838101
703618.352959724776776.034493407703592.071178599  776526.1181362
703589.207842156776458.388482179703592.795378087776381.151694507
#Sta/Elev= 30
9649.0121745.0599714.0871741.6559754.2251735.229 9804.481716.2629834.6961694.467
9874.9851642.955 9895.131592.1059905.2021551.2879925.3461481.5949935.4191459.109
 9955.561403.4389965.6061381.5499975.6511352.02910005.79 1350.5110035.961351.604
10066.141367.26610076.191391.48810106.371448.53710116.421476.99510136.541497.974
10166.711546.55810196.891575.42610206.941573.14710236.961549.24810246.971546.219
10256.981557.756   102771590.06810297.021630.60510317.041651.51510350.931696.593
#Mann= 3 , 0 , 0
9649.012    0.12       09649.012    0.12       010350.93    0.12       0
#XS Ineff= 2 , 0
       0                               0
Bank Sta=9649.012,10350.93
Exp/Cntr=0.3,0.1