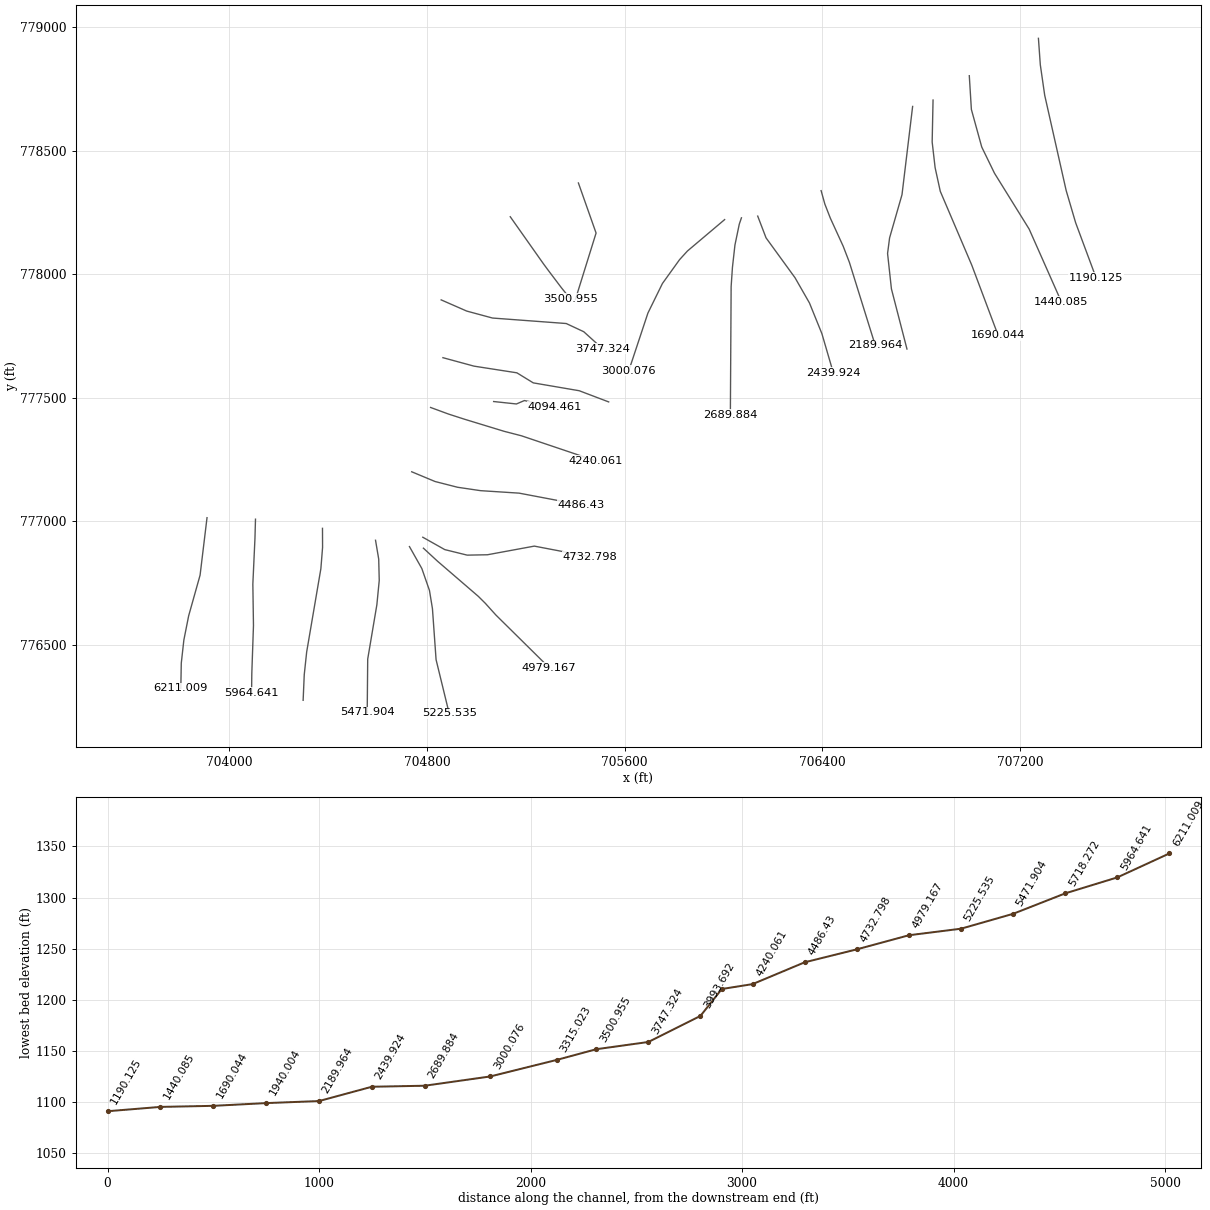
HEC-RAS study 14441_ras.prj: 14441

--- 14441_ras.g01 (geometry) --- (continued)

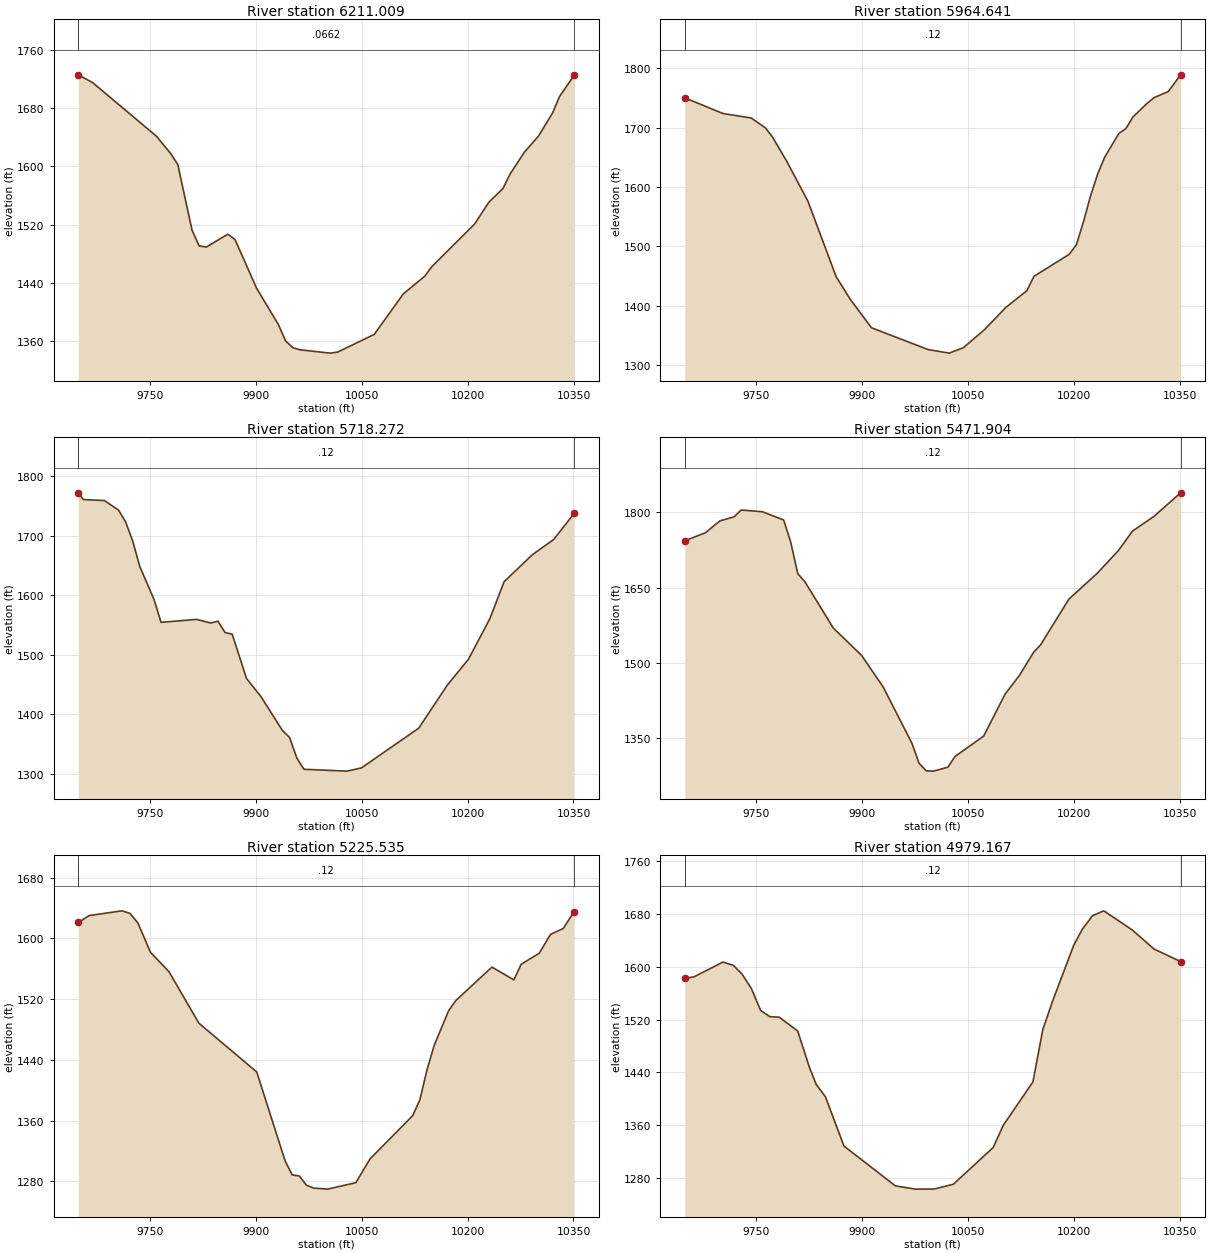
Type RM Length L Ch R = 1 ,6211.009,246.368600,246.368600,246.368600
XS GIS Cut Line= 6
703909.410166695777015.098153604703881.299168241776782.413850903
703835.056048536 776617.81108218703815.628064885776519.792585317
703805.215630448776426.439928474703803.324208054776324.360184163
#Sta/Elev= 30
9649.0561725.8489669.2331715.2089759.589 1641.489779.759 1617.679789.8441602.632
9810.0141512.2699820.1221490.6279830.2571488.9999860.6631506.6829870.7991499.465
9901.403 1432.39 9932.151382.6719942.3991360.0499952.6481350.6529962.897 1347.76
10005.411343.18910016.21 1344.6310068.041369.03710108.981424.52110139.431449.012
10149.581462.252   102101520.67110230.121550.51710250.241569.67310260.251589.454
10280.27 1619.2310300.291641.45810320.29 1673.2110330.291696.11610350.931725.218
#Mann= 3 , 0 , 0
9649.056  0.0662       09649.056  0.0662       010350.93  0.0662       0
#XS Ineff= 2 , 0
       0                               0
Bank Sta=9649.056,10350.93
Exp/Cntr=0.3,0.1

Type RM Length L Ch R = 1 ,5964.641,246.368500,246.368500,246.368500
XS GIS Cut Line= 6
704105.585152783777009.081538696704103.440818981776931.756980526
704094.884609685776746.191163079 704097.41628056776578.391910834
704090.680541079776384.846966306704089.745223393776307.498601686
#Sta/Elev= 30
9649.0271750.1319703.1291723.7259743.1561716.1719763.1771699.5069773.1881684.116
9793.2091643.4619823.2411576.1689863.2831448.6289883.3041410.4579913.3351362.518
9993.3421325.82410023.351319.74510043.351328.87210073.351359.33310103.371396.623
10133.391425.11610143.391449.27710193.421486.44110203.43 1502.5310213.441541.198
10223.44 1584.7210233.451621.40110243.451650.00610263.471689.98410273.471698.274
10283.471717.83310303.471740.82810313.48 1750.5110333.481760.76510350.981788.944
#Mann= 3 , 0 , 0
9649.027    0.12       09649.027    0.12       010350.98    0.12       0
#XS Ineff= 2 , 0
       0                               0
Bank Sta=9649.027,10350.98
Exp/Cntr=0.3,0.1

Type RM Length L Ch R = 1 ,5718.272,246.368600,246.368600,246.368600
XS GIS Cut Line= 6
704376.746871265776972.010137225704377.109175279776894.678959149
704370.189275199776808.553492806704312.730789652776471.569972551
704302.920668873 776379.55792706 704298.40393124776275.924193403
#Sta/Elev= 30
9649.0581772.4739656.0681761.2039686.069 1759.479706.0691743.2569716.0691723.472
9726.0691691.172  9736.1 1648.349756.1651593.1539766.197 1554.529816.3851559.478
9836.5981553.4229846.7041556.4989856.8111537.3329866.9171534.576 9887.131460.102
9907.4341429.8419937.9571372.6999948.1321360.7029958.3061326.3079968.4811307.248
10029.541304.14810049.891309.56910130.971376.43910171.361448.78810201.53 1492.81
 10231.71560.87110251.791622.87710291.831668.34610321.861693.79810350.961737.774
#Mann= 3 , 0 , 0
9649.058    0.12       09649.058    0.12       010350.96    0.12       0
#XS Ineff= 2 , 0
       0                               0
Bank Sta=9649.058,10350.96
Exp/Cntr=0.3,0.1

Type RM Length L Ch R = 1 ,5471.904,246.368500,246.368500,246.368500
XS GIS Cut Line= 6
704591.439527326776923.717581575704604.306951998776847.503623353
704606.472304514776761.169074761704596.801751748776662.342650429
704559.782821564776442.697890461704557.745311323776226.955076705
#Sta/Elev= 30
9649.0591742.969 9678.321759.2569698.6981782.7219718.8481790.8549728.9061804.389
9758.9531800.9519788.9771784.5849798.978 1740.569808.9781677.6559818.993 1661.64
9859.0881569.6639899.3911514.5689929.7921452.0439970.4961340.0169980.6721299.852
9990.8481284.73710001.031284.16410021.41 1291.8810031.591313.36310072.161353.986
10102.411437.49410122.581474.496 10142.71520.67410152.721535.75310192.821626.963
10232.831678.20610262.841723.64410282.861762.49310312.881791.39610350.951838.665
#Mann= 3 , 0 , 0
9649.059    0.12       09649.059    0.12       010350.95    0.12       0
#XS Ineff= 2 , 0
       0                               0
Bank Sta=9649.059,10350.95
Exp/Cntr=0.3,0.1

Type RM Length L Ch R = 1 ,5225.535,246.368600,246.368600,246.368600
XS GIS Cut Line= 6
704728.762813745776898.100135827704778.902731229776809.207571475
704809.758048484776720.619283417704821.833276171 776646.73542463
704836.518274077776440.371777892704889.490131048 776223.04210044
#Sta/Elev= 30
9649.0871620.9939664.4581630.0799710.9011636.3289722.1631632.9399733.4261620.356
9751.2131581.6929777.378 1556.179819.6971488.3079901.6371424.0199941.806 1306.81
9951.8161288.3049961.8271286.9679971.8381274.8689981.8491271.02710001.871269.609
10041.91 1278.08   100621309.38910122.391366.43710132.511387.09210142.671426.839
10152.821458.95610173.141504.38410183.341517.98110234.581562.16210265.611545.361
10275.961565.93210301.461580.35810317.541605.34310335.62  1613.110350.961635.407
#Mann= 3 , 0 , 0
9649.087    0.12       09649.087    0.12       010350.96    0.12       0
#XS Ineff= 2 , 0
       0                               0
Bank Sta=9649.087,10350.96
Exp/Cntr=0.3,0.1

Type RM Length L Ch R = 1 ,4979.167,246.368500,246.368500,246.368500
XS GIS Cut Line= 6
 704785.25768581776891.659284176 704842.09211462776839.191319649
705007.753614379776696.454961983705035.925561336776668.438242285
705078.151238627776621.596604347705293.764035427776408.594466344
#Sta/Elev= 30
9649.0311582.393 9662.291584.7719703.0751607.0769717.8171602.0769730.1921588.632
9743.2971566.9249756.403 1533.829769.5091524.3899782.6151523.6149808.827 1502.75
 9825.691446.9989835.038 1421.899848.1441403.0449874.3561328.4839947.1351268.152
9975.4981263.21710002.351263.41510029.331270.63110085.651326.29310099.981359.971
10141.88 1425.5410155.931505.01310169.991548.70710199.581632.31910212.161657.313
10226.221677.22110242.271684.65910282.441655.75410313.421626.73410350.99 1607.92
#Mann= 3 , 0 , 0
9649.031    0.12       09649.031    0.12       010350.99    0.12       0
#XS Ineff= 2 , 0
       0                               0
Bank Sta=9649.031,10350.99
Exp/Cntr=0.3,0.1

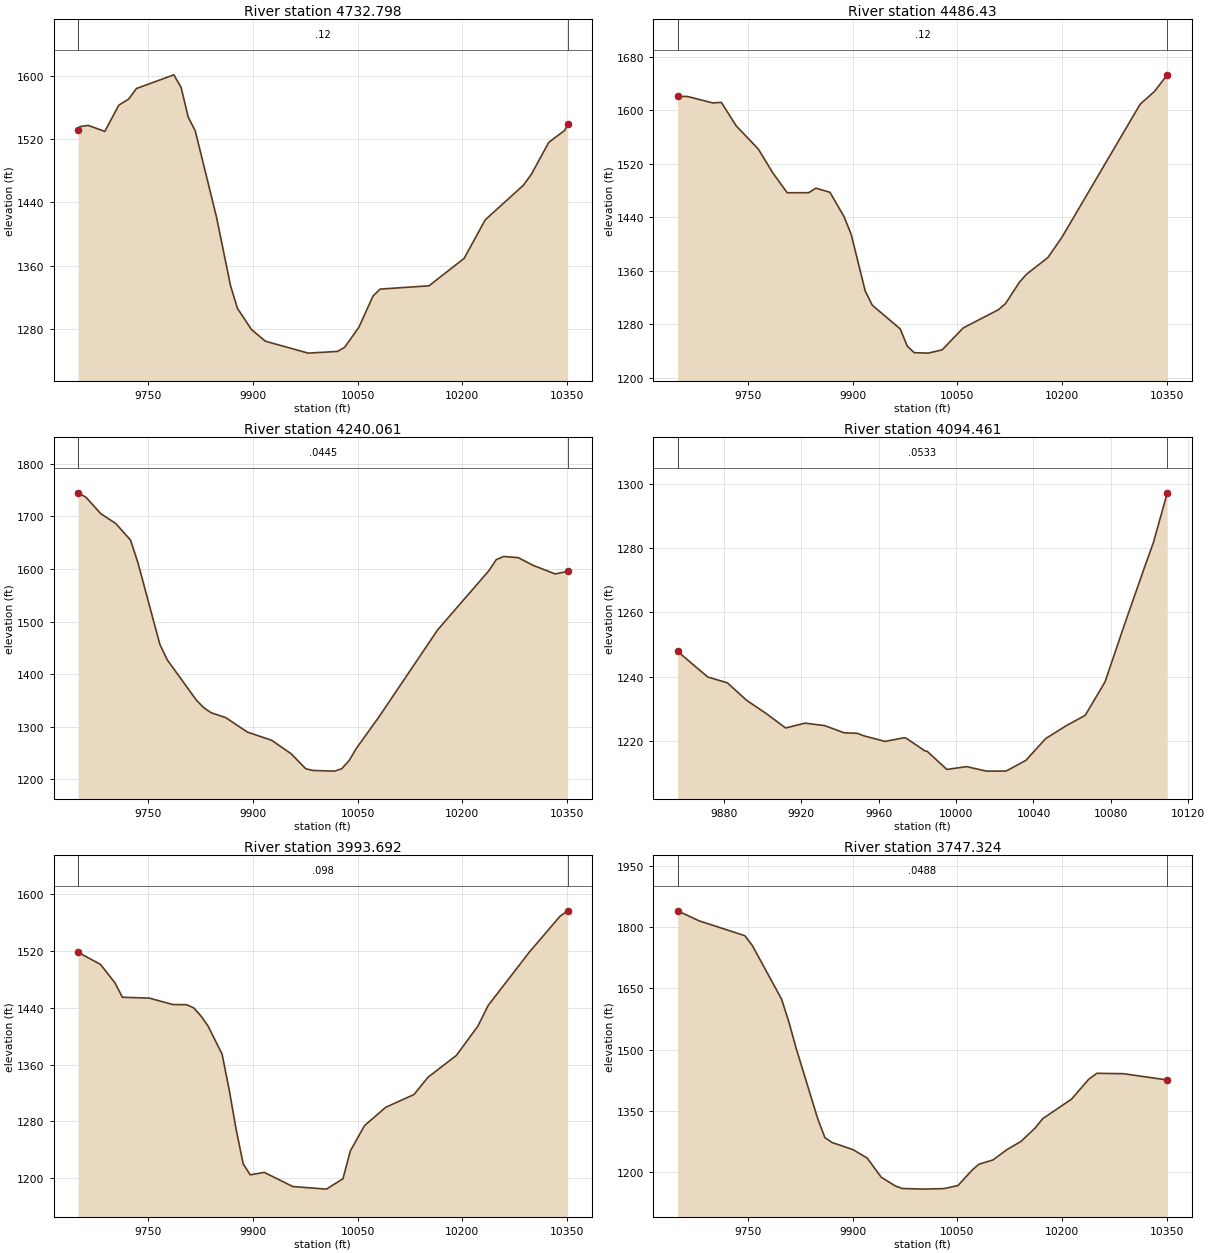
Type RM Length L Ch R = 1 ,4732.798,246.368600,246.368600,246.368600
XS GIS Cut Line= 6
704782.778604002776935.957568593704871.556285502776885.962127012
704962.483572302776863.518259593 705044.39398255 776865.04343668
705234.207928341776900.036887696705458.905670864776857.063463032
#Sta/Elev= 30
9649.2071530.8759651.8571535.4859663.7881537.0149687.6491529.4529707.6431562.553
9721.7841570.2279732.8971583.5489786.514 1600.879796.9471585.0039807.106 1547.63
9817.2651530.0059847.7041421.1769867.7231334.8499877.7321305.8659897.7751279.222
9917.8281264.4639979.077 1249.4310021.16 1251.5910031.441256.84910051.851282.294
10071.991321.50610082.071330.27210152.16 1334.4210202.521369.01110232.931417.904
 10287.51461.42210299.111475.574   103241515.73410346.811530.783 10350.91538.235
#Mann= 3 , 0 , 0
9649.207    0.12       09649.207    0.12       0 10350.9    0.12       0
#XS Ineff= 2 , 0
       0                               0
Bank Sta=9649.207,10350.9
Exp/Cntr=0.3,0.1

Type RM Length L Ch R = 1 , 4486.43,246.368500,246.368500,246.368500
XS GIS Cut Line= 6
704737.892482761777200.891426826704832.366513091777161.525601367
 704923.22611031777138.299853314705016.618759948777124.484270348
705172.634498152 777114.44528704 705422.65032918777067.051931156
#Sta/Elev= 30
 9649.06 1620.41 9662.96 1620.429699.5271610.6799711.6751611.578 9732.991576.476
9764.6561541.8539785.4851506.199 9806.131476.4699836.8891476.5789847.122 1483.31
9867.4111477.165  9887.71440.6329897.8191414.4159917.9721329.6339928.0491308.427
9968.199 1272.919978.2161247.3829988.2181237.49510008.221236.79610028.221241.676
10058.441274.43410108.871301.673   101191310.71110139.251343.08510149.381354.868
10179.771379.58310200.02 1410.0510312.171608.90410332.771628.01110350.951652.713
#Mann= 3 , 0 , 0
 9649.06    0.12       0 9649.06    0.12       010350.95    0.12       0
#XS Ineff= 2 , 0
       0                               0
Bank Sta=9649.06,10350.95
Exp/Cntr=0.3,0.1

Type RM Length L Ch R = 1 ,4240.061,145.600100,145.600100,145.600100
XS GIS Cut Line= 6
704814.295746998777461.222217155704886.887165616777434.515889625
704951.406949072777413.681352834705112.093158442777364.660943262
705182.082587165777346.555533093705482.001057608777245.489991091
#Sta/Elev= 30
9649.0261744.7149660.4321736.3169681.7431704.9539703.0531686.4959724.3641654.777
  9734.91611.8579766.4251456.3419776.9341427.1369818.8411350.2669829.2961336.169
9839.7511326.5669860.6611317.2939892.0261289.6539926.7391274.1189954.7561248.283
9975.4841220.0479985.7981216.74410016.781215.47310027.141220.06610037.551235.303
 10048.11258.78210079.761317.248 10164.61484.07710238.051596.614 10248.61617.607
10259.15 1623.7110280.261621.42410301.361606.88910333.021590.47610350.961595.281
#Mann= 3 , 0 , 0
9649.026  0.0445       09649.026  0.0445       010350.96  0.0445       0
#XS Ineff= 2 , 0
       0                               0
Bank Sta=9649.026,10350.96
Exp/Cntr=0.3,0.1

Type RM Length L Ch R = 1 ,4094.461,100.768500,100.768500,100.768500
XS GIS Cut Line= 4
705069.510338098777485.257695854705161.705818892777475.379608601
705193.974237144777489.208930731705316.462518752777463.525903955
#Sta/Elev= 30
9856.1521247.902 9871.731239.9359881.7871238.1589891.8451232.6829901.9021228.605
9911.9591224.1019922.0161225.6099932.0741224.8479942.1311222.6089948.8751222.451
9952.4591221.6439963.339 1219.939973.2971221.0799974.2181220.9369983.9821216.957
 9985.031216.8819995.2481211.21110005.47 1212.0910015.681210.691 10025.91210.716
10036.12 1214.0510046.331220.81810056.551224.67210066.771228.04610076.991238.448
 10087.21256.53910097.421274.10310101.951281.70910107.641293.90710109.131297.192
#Mann= 3 , 0 , 0
9856.152  0.0533       09856.152  0.0533       010109.13  0.0533       0
#XS Ineff= 2 , 0
       0                               0
Bank Sta=9856.152,10109.13
Exp/Cntr=0.3,0.1

Type RM Length L Ch R = 1 ,3993.692,246.368500,246.368500,246.368500
XS GIS Cut Line= 6
704864.238021712777662.724448807704990.069405115777628.483113237
705163.521342497777601.470558808705229.883375957777560.762465085
705415.971344895777528.949072664705535.093209213777483.678251522
#Sta/Elev= 30
9649.2061518.3749681.3991501.259 9702.331474.9989712.795 1454.969751.2091453.752
9784.6921444.766 9804.981444.3849815.1251439.8779825.2691428.7349835.4141414.585
 9855.63 1374.799865.7131325.1199875.796 1268.58 9885.881220.1259895.9631204.536
9916.1291208.0719956.9041188.11510005.131184.43410028.841199.06610039.441238.348
10059.891274.166 10090.21299.82910130.59 1317.7910150.781342.18810191.461373.023
10222.121414.12610236.971443.411 10295.71518.254 10339.71568.96210350.811576.785
#Mann= 3 , 0 , 0
9649.206   0.098       09649.206   0.098       010350.81   0.098       0
#XS Ineff= 2 , 0
       0                               0
Bank Sta=9649.206,10350.81
Exp/Cntr=0.3,0.1

Type RM Length L Ch R = 1 ,3747.324,246.368600,246.368600,246.368600
XS GIS Cut Line= 6
704857.117930567 777896.66416822704960.560580798777851.365981511
705064.907017312777823.179322786705363.215598947777800.994013192
 705434.12718827 777767.87921669705509.779812179777699.601471096
#Sta/Elev= 30
 9649.081839.7379679.9161815.2279745.3851778.9279756.1111754.936 9798.16 1623.34
9808.6371566.917 9819.061502.9489849.8291331.3179860.0851285.165 9870.341273.053
9900.6621255.386 9920.841234.8629940.9021188.1279960.9461166.8259970.947 1160.54
10000.951158.92110030.961160.20910050.961167.73710070.961205.18410080.971219.881
10100.991230.25110121.121255.56710141.291275.69610161.821308.90210172.151331.081
10213.591378.89710238.31 1427.6110249.841442.22810287.971441.34710350.891426.022
#Mann= 3 , 0 , 0
 9649.08  0.0488       0 9649.08  0.0488       010350.89  0.0488       0
#XS Ineff= 2 , 0
       0                               0
Bank Sta=9649.08,10350.89
Exp/Cntr=0.3,0.1

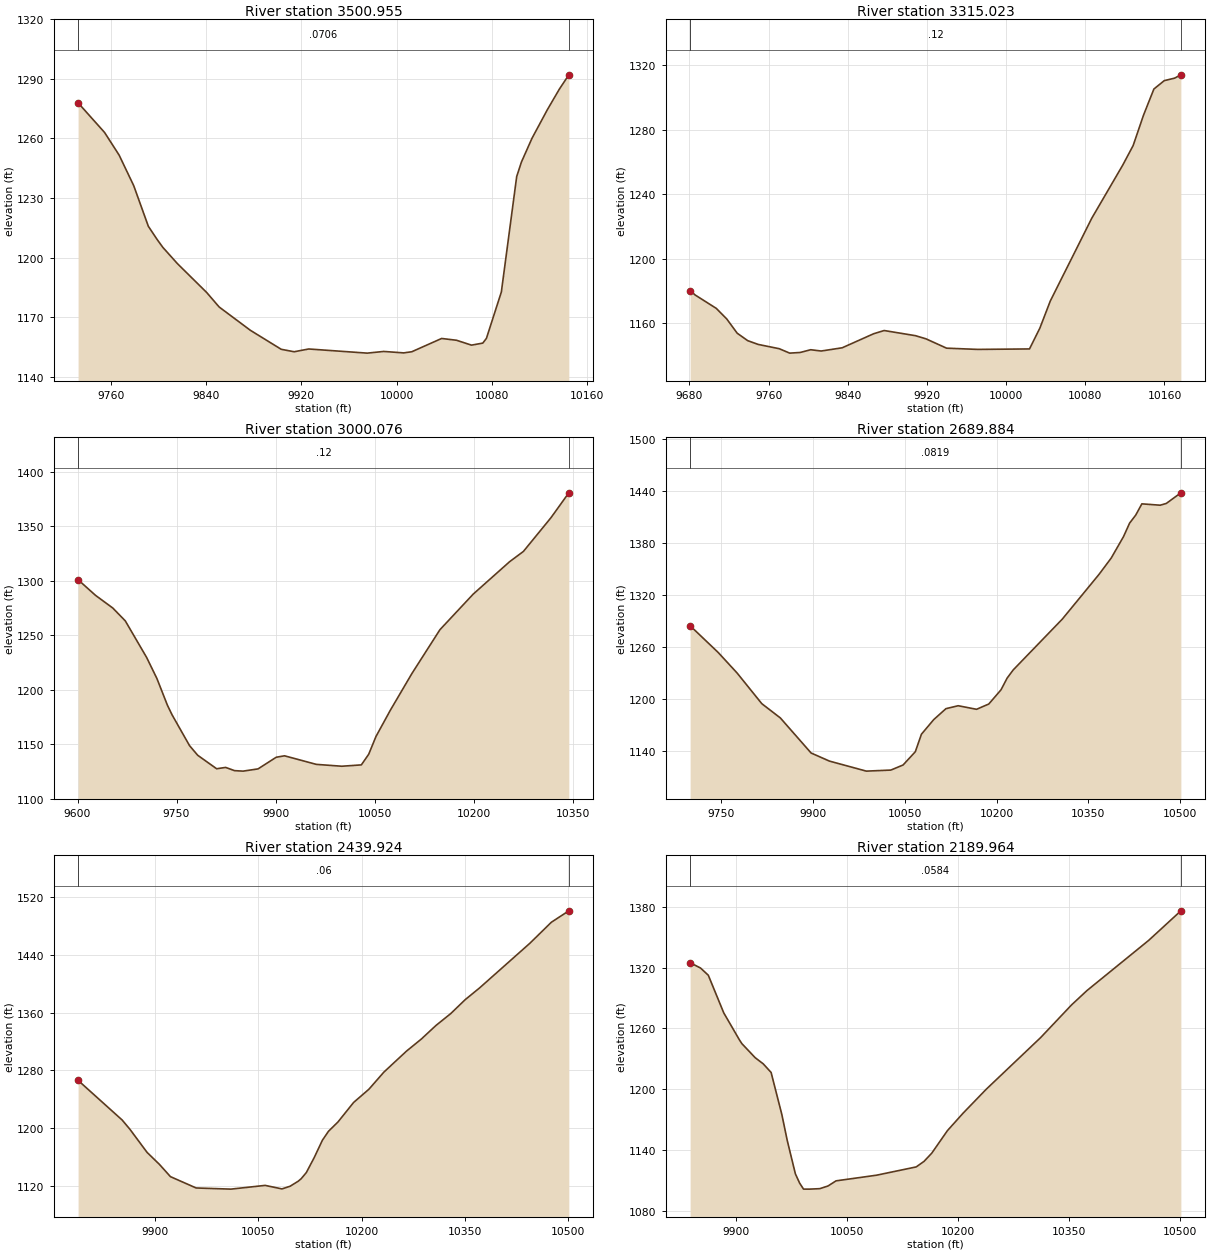
Type RM Length L Ch R = 1 ,3500.955,185.932300,185.932300,185.932300
XS GIS Cut Line= 6
 705136.75360829778233.183353898705271.297684958778042.403595539
705290.855623163778015.894005319705292.069703869778014.304663305
705344.410763769777944.973679136 705380.05584864777901.010626668
#Sta/Elev= 30
9732.6061277.9229754.8571262.9739767.0931251.554 9779.331236.1639791.5671215.753
9798.9681209.0789803.803 1205.08 9816.041196.8929840.5131182.4119851.0221175.086
9877.2231163.3469903.0761153.7929913.933 1152.55 9926.171153.9469975.2571151.859
9989.1371152.70610005.861151.98110012.661152.54710037.721159.24310050.251158.335
10062.781155.88410072.251156.90210075.311159.28310087.841182.64410100.711240.771
10104.681248.07610113.581260.08210126.461274.46110136.44 1284.7310144.471292.015
#Mann= 3 , 0 , 0
9732.606  0.0706       09732.606  0.0706       010144.47  0.0706       0
#XS Ineff= 2 , 0
       0                               0
Bank Sta=9732.606,10144.47
Exp/Cntr=0.3,0.1

Type RM Length L Ch R = 1 ,3315.023,314.947100,314.947100,314.947100
XS GIS Cut Line= 3
705412.591566712778369.883993372705484.124200732778167.208196968
705400.669461012777898.960819334
#Sta/Elev= 30
9680.7171180.2599685.8961177.4859707.1061169.239 9717.711162.6629728.315  1153.8
9738.9191149.1789749.5241146.8479770.7331144.1999781.3381141.4529791.9421141.859
9802.5471143.5589813.1511142.763 9834.361144.7619866.174 1153.489876.7791155.476
9908.4311152.2779918.904 1150.35 9939.851144.5299971.2681143.75910023.631144.052
 10034.11156.98210044.581173.69910086.471225.08110117.89 1258.1810128.34 1270.24
10138.831289.11610149.311305.32610159.781310.53810170.251312.08110176.581314.145
#Mann= 3 , 0 , 0
9680.717    0.12       09680.717    0.12       010176.58    0.12       0
#XS Ineff= 2 , 0
       0                               0
Bank Sta=9680.717,10176.58
Exp/Cntr=0.3,0.1

Type RM Length L Ch R = 1 ,3000.076,310.192200,310.192200,310.192200
XS GIS Cut Line= 6
706004.419364644778221.606585507  705853.9353608 778094.52204617
705822.092819397778059.561230778705752.710341221777963.022286999
705693.952915862 777843.34545766705616.250179545777609.197147924
#Sta/Elev= 30
9600.7971300.9099627.1391286.6159653.3611274.9549672.3161263.1629704.6661229.571
9720.2231210.2649736.1921185.7159743.1451176.9929769.7051148.6319782.0361139.809
 9810.761127.4289824.3271128.6689837.8951125.6949850.8571125.2559873.4331127.308
9901.0461138.0019913.5931139.3199961.7391131.452 10000.31129.74810029.971130.979
 10041.11140.71910052.16 1157.0710073.951181.18410106.431214.67910149.031255.031
10199.461287.70810254.551317.42310275.48 1326.8610317.331357.88410344.331380.662
#Mann= 3 , 0 , 0
9600.797    0.12       09600.797    0.12       010344.33    0.12       0
#XS Ineff= 2 , 0
       0                               0
Bank Sta=9600.797,10344.33
Exp/Cntr=0.3,0.1

Type RM Length L Ch R = 1 ,2689.884,249.959800,249.959800,249.959800
XS GIS Cut Line= 6
706072.456659249778228.802837819706063.758867672778203.245022602
706046.192906051 778118.68200385706036.102143485778028.597803009
706030.787530722777950.418204461706027.654506237777431.250688011
#Sta/Elev= 30
9699.398 1284.44 9745.151253.5749775.9591229.8819816.512 1194.23  9846.71177.786
9897.012 1137.159927.1071127.7599987.233 1116.1810027.231117.38810047.231123.276
10067.231138.64810077.231158.93210097.241175.75910117.241188.47410137.241191.867
10167.241187.73610187.241193.85310207.241210.33310217.241223.90210227.241233.389
10307.241292.06610367.241343.84510387.241362.83610407.241387.53610417.24 1403.21
10427.241412.48610437.241425.51910467.24 1423.9510477.241426.02210500.991438.279
#Mann= 3 , 0 , 0
9699.398  0.0819       09699.398  0.0819       010500.99  0.0819       0
#XS Ineff= 2 , 0
       0                               0
Bank Sta=9699.398,10500.99
Exp/Cntr=0.3,0.1

Type RM Length L Ch R = 1 ,2439.924,249.959800,249.959800,249.959800
XS GIS Cut Line= 6
706138.382519476778235.775765342706172.068739168778147.670321877
706289.418668333777986.245066368706347.745446295777884.278220414
706398.084518352777760.104351135706444.657183912777600.506204945
#Sta/Elev= 30
9788.5281266.1559852.5611211.0759863.6561198.4149888.691 1166.19 9906.751149.405
9922.6311132.4889959.8971116.79410010.391115.18310060.031120.37110084.52 1115.49
10096.321119.19110108.111126.16210112.431129.65910119.911138.22910131.291158.919
 10143.21183.02910152.021195.44510165.83 1208.4310188.461235.43810210.73 1253.85
10232.581277.72110265.34 1306.7910286.781323.458 10308.11342.40310329.431358.771
10350.49 1378.1610371.47 1394.5410444.481456.52710475.56 1485.6210500.941501.483
#Mann= 3 , 0 , 0
9788.528    0.06       09788.528    0.06       010500.94    0.06       0
#XS Ineff= 2 , 0
       0                               0
Bank Sta=9788.528,10500.94
Exp/Cntr=0.3,0.1

Type RM Length L Ch R = 1 ,2189.964,249.959800,249.959800,249.959800
XS GIS Cut Line= 6
706394.950014926 778338.78757666706410.102917158778284.366872134
706432.093374026778227.983157763706484.312420641778113.817930243
706509.480954223778048.504676177706613.873662725777713.408571744
#Sta/Elev= 30
9837.3741324.7529851.5471319.4299861.9711312.3539882.8191275.2579903.957 1248.66
9907.3811244.8149925.425 1230.919936.1581224.9359946.8921216.3889961.3941174.861
9968.7081149.229 9979.711116.2629985.3771107.2499990.7121101.207    99991101.201
10012.721101.66110023.711104.268 10034.71109.36910089.421114.946   101431123.111
10153.651128.58710164.171136.75310185.221158.87510206.261176.01910237.831199.847
 10311.41250.85410353.161283.08210374.04 1297.2610457.551346.85310500.971375.955
#Mann= 3 , 0 , 0
9837.374  0.0584       09837.374  0.0584       010500.97  0.0584       0
#XS Ineff= 2 , 0
       0                               0
Bank Sta=9837.374,10500.97
Exp/Cntr=0.3,0.1

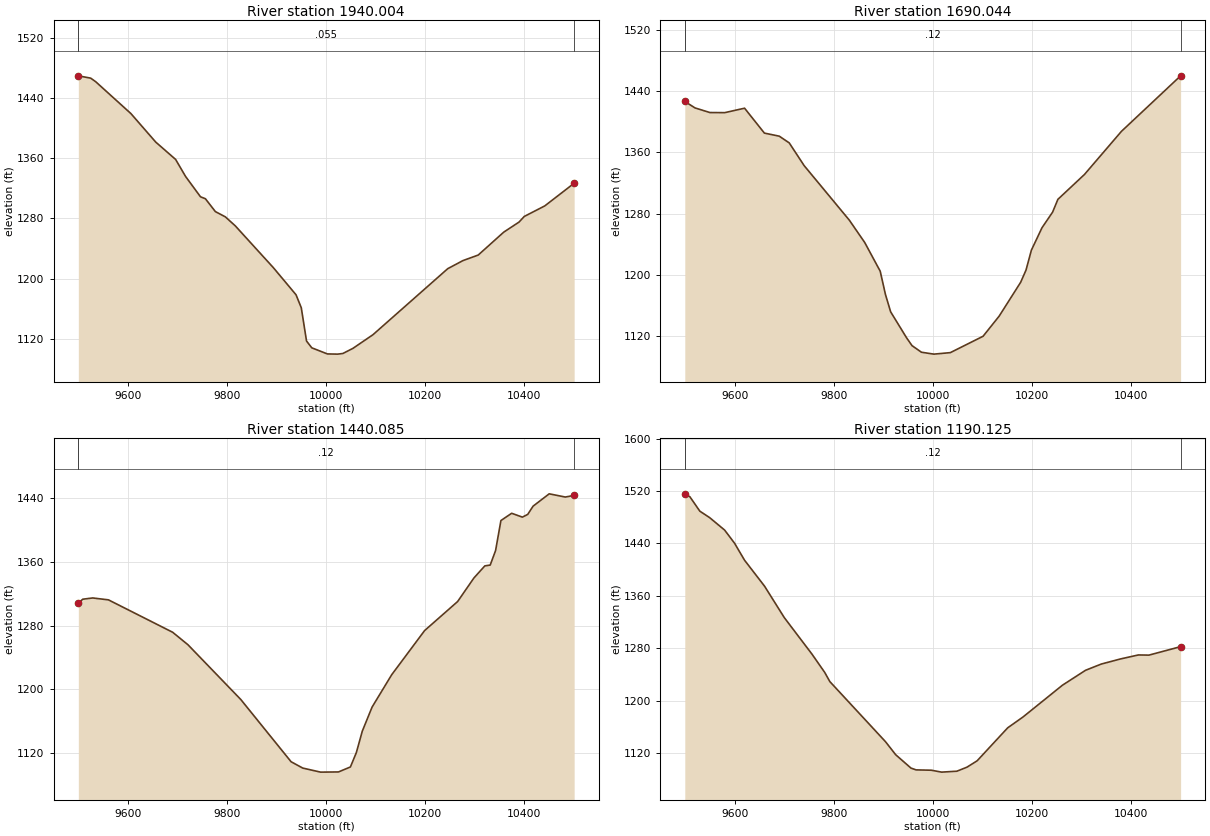
Type RM Length L Ch R = 1 ,1940.004,249.959800,249.959800,249.959800
XS GIS Cut Line= 6
706765.369109537778679.562559781706722.346417545778322.380629495
706672.153270422778147.696267456706663.944919795778084.561140491
706679.553023848777941.168566837706742.448863707777697.697102165
#Sta/Elev= 30
9499.0911470.1649524.133 1467.069534.3291462.2439605.2671419.8859655.5431381.807
9695.7031358.7059715.7671336.0379745.8631308.9739755.8951306.3029775.9591289.197
9796.0321282.2329816.1921270.1989893.5471214.1489938.9871178.2969949.5741161.017
9960.161 1116.689970.7481107.62410002.341099.46710023.141099.20610033.551100.046
10054.061106.93910094.431125.107 10245.51213.11810276.271223.89710307.071231.272
10358.591261.77910389.691275.30310400.051282.69910441.511296.765 10500.91327.009
#Mann= 3 , 0 , 0
9499.091   0.055       09499.091   0.055       0 10500.9   0.055       0
#XS Ineff= 2 , 0
       0                               0
Bank Sta=9499.091,10500.9
Exp/Cntr=0.3,0.1

Type RM Length L Ch R = 1 ,1690.044,249.959800,249.959800,249.959800
XS GIS Cut Line= 6
706848.044128256778705.558204454706844.441150283778535.745325925
706856.395546395778431.893736148706877.318063976778336.068990527
707004.697084216778037.453020024707111.598574547777752.678786997
#Sta/Elev= 30
9499.0671426.2849519.6971417.8249549.8021411.7899579.8431411.6489619.8591417.454
9659.883 1384.979689.9791380.9429710.0671372.2039740.274 1342.499831.6721271.231
9862.6181242.2329893.9441204.738 9904.441174.6359915.0011151.7679947.2331117.828
9958.2031107.6289977.2791099.00310002.431096.53310035.681098.49210101.791119.849
10134.341146.15510177.751190.286 10188.61206.29110199.421232.19710220.861261.468
 10242.3 1281.8210253.021298.55110306.631330.93710381.441387.27810500.981459.697
#Mann= 3 , 0 , 0
9499.067    0.12       09499.067    0.12       010500.98    0.12       0
#XS Ineff= 2 , 0
       0                               0
Bank Sta=9499.067,10500.98
Exp/Cntr=0.3,0.1

Type RM Length L Ch R = 1 ,1440.085,249.959800,249.959800,249.959800
XS GIS Cut Line= 6
706994.740833385778804.048179548707003.182262594778667.408704537
707045.126580669778515.350604242707096.693702119778409.364215991
 707237.03519073778183.154600458707367.629161749777888.464597495
#Sta/Elev= 30
 9499.091308.3319508.1381313.0939528.1381314.6599559.9751312.2639689.7481271.475
9720.6721255.7459827.4381186.8319929.0181108.5519952.5221100.5949988.586 1095.49
10024.781095.72410048.841101.97810060.871120.06710072.881147.051 10092.71177.384
10132.32 1218.0810198.781273.60510265.511310.15510298.481339.85410320.46 1355.01
10331.331356.03310342.171374.237   103531412.09110374.681421.21910396.351416.377
10407.19 1419.8310418.03  1430.210450.541445.69910483.051441.65510500.971443.759
#Mann= 3 , 0 , 0
 9499.09    0.12       0 9499.09    0.12       010500.97    0.12       0
#XS Ineff= 2 , 0
       0                               0
Bank Sta=9499.09,10500.97
Exp/Cntr=0.3,0.1

Type RM Length L Ch R = 1 ,1190.125,0.000000,0.000000,0.000000
XS GIS Cut Line= 6
707274.560475475 778955.30007486707282.184136367778848.132839813
707299.932582683778724.998814566707386.759213205 778339.56682994
707425.142470945778209.028690052707508.260027472777985.173040012
#Sta/Elev= 30
9499.0521515.6679509.3781511.1569529.4291489.2359549.479 1479.259579.5551460.364
9599.6061440.3419619.7311414.5029660.0611375.0219700.2661326.7449756.3491270.906
9781.9361243.1679792.1411229.3469904.6651137.6369925.2581117.7569956.147 1097.37
9966.4441094.6719997.3331094.16810017.971091.25710048.841092.65610069.321098.834
 10089.81108.536 10151.51158.78210182.551175.38310262.181223.81410308.931246.594
10340.781256.09910379.321263.82310415.57 1269.9410436.971269.69410500.981282.621
#Mann= 3 , 0 , 0
9499.052    0.12       09499.052    0.12       010500.98    0.12       0
#XS Ineff= 2 , 0
       0                               0
Bank Sta=9499.052,10500.98
Exp/Cntr=0.3,0.1